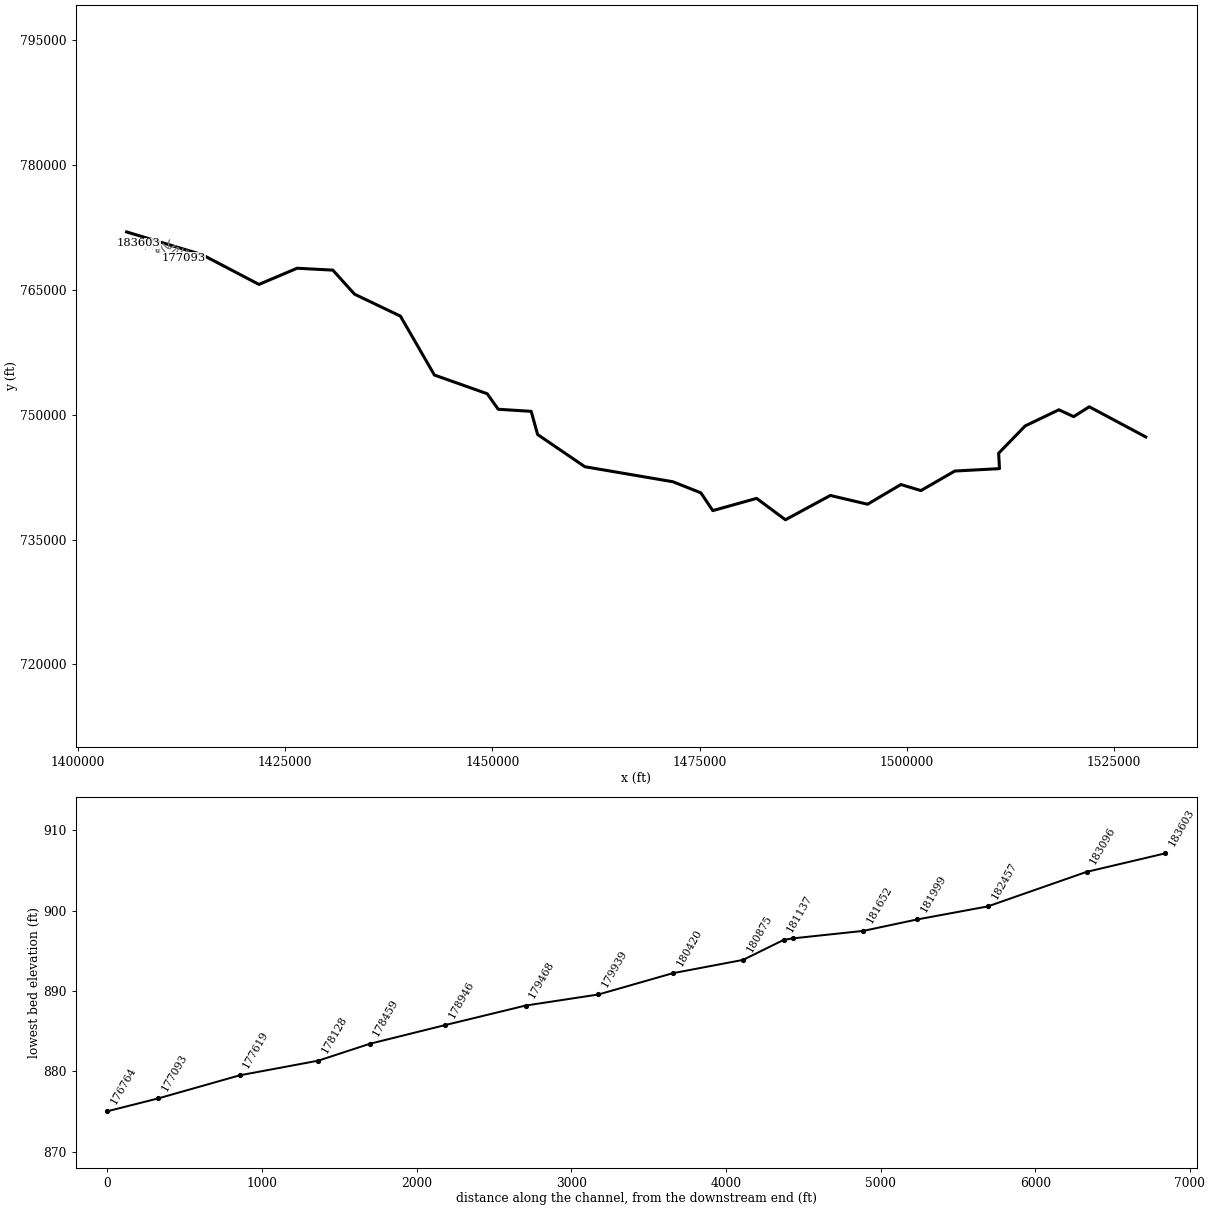
--- Fourth Creek.prj (project) ---

Proj Title=Fourth Creek Detailed Study
Current Plan=p02
Default Exp/Contr=0.3,0.1
English Units
Geom File=g01
Flow File=f02
Flow File=f01
Plan File=p02
Plan File=p01
Y Axis Title=Elevation
X Axis Title(PF)=Main Channel Distance
X Axis Title(XS)=Station
BEGIN DESCRIPTION:
Fourth Creek
END DESCRIPTION:
DSS Export Rating Curves= 0
DSS Export Rating Curve Sorted= 0
DSS Export Volume Flow Curves= 0
DXF OffsetX= 0
DXF OffsetY= 0
DXF ScaleX= 1
DXF ScaleY= 10

--- Fourth Creek.p02 (plan) ---

Plan Title=Floodway Run
Program Version=3.12
Short Identifier=Floodway
Geom File=g01
Flow File=f02
Subcritical Flow
K Sum by GR= 0
Std Step Tol= 0.01
Critical Tol= 0.01
Num of Std Step Trials= 20
Max Error Tol= 0.3
Flow Tol Ratio= 0.001
Split Flow NTrial= 30
Split Flow Tol= 0.02
Split Flow Ratio= 0.02
Log Output Level= 0
Friction Slope Method= 1
Unsteady Friction Slope Method= 2
Unsteady Bridges Friction Slope Method= 1
Parabolic Critical Depth
Global Vel Dist= 0 , 0 , 0
Global Log Level= 0
CheckData=True
Encroach Param=-1 ,10,10, 2
Encroach River=Fourth Creek
Encroach Reach=Reach-1
Encroach Node=183603
       1 4944.76  5019.5
Encroach Node=183096
       1 4933.35  5024.5
Encroach Node=182457
       1  4981.6  5039.5
Encroach Node=181999
       1 4921.86  5024.5
Encroach Node=181652
       1 4921.99  5019.5
Encroach Node=181197
       1  4960.8  5028.7
Encroach Node=181137
       1  4961.5    5027
Encroach Node=180875
       1  4972.6 5073.42
Encroach Node=180420
       1  4968.4 5189.73
Encroach Node=179939
       1  4975.8 5062.17
Encroach Node=179468
       1 4922.77 5031.18
Encroach Node=178946
       1    4890    5075
Encroach Node=178459
       1  4981.6 5113.86
Encroach Node=178128
       1  4981.6 5105.49
Encroach Node=177619
       1  4917.6 5034.83
Encroach Node=177093
       1 4953.85 5156.79
Encroach Node=176764
       1  4988.5 5089.93
Encroach Node=176493
       1 4951.37 5053.83
Encroach Node=176104
       1 4887.28  5019.5
Encroach Node=175645
       1 4895.93 5058.94
Encroach Node=175286
       1  4941.6  5024.5
Encroach Node=174742
       1 4933.37  5021.4
Encroach Node=174065
       1  4959.9  5026.4
Encroach Node=173513
       1    4951  5026.4
Encroach Node=173023
       1 4903.26  5026.4
Encroach Node=172662
       1  4964.9  5026.4
Encroach Node=172211
       1 4934.35  5025.1
Encroach Node=171545
       1 4894.05  5022.6
Encroach Node=171000
       1  4938.4  5022.6
Encroach Node=170493
       1 4852.65  5018.1
Encroach Node=170099
       1 4964.94 5157.08
Encroach Node=169649
       1  4978.4 5133.55
Encroach Node=169072
       1 4933.48  5027.6
Encroach Node=168493
       1  4931.6  5059.4
Encroach Node=168105
       1 4827.13  5022.6
Encroach Node=167525
       1 4847.02    5020
Encroach Node=167031
       1 4873.94  5022.6
Encroach Node=166437
       1    4901    5158
Encroach Node=166010
       1 4795.31  5027.6
Encroach Node=165485
       1 4864.07  5027.6
Encroach Node=165025
       1 4824.94 5071.64
Encroach Node=164563
       1 4882.91  5025.6
Encroach Node=164063
       1  4948.4 5107.53
Encroach Node=163493
       1 4797.98  5027.6
Encroach Node=162968
       1 4832.46  5030.9
Encroach Node=162379
       1    4970  5082.2
Encroach Node=161840
       1    4974  5070.9
Encroach Node=161161
       1  4964.9 5117.83
Encroach Node=160562
       1 4856.39  5083.3
Encroach Node=160014
       1 4800.55 5100.39
Encroach Node=159604
       1 4894.47 5041.95
Encroach Node=159195
       1    4974    5037
Encroach Node=159056
       1  4934.9  5060.9
Encroach Node=158916
       1  4904.9  5040.9
Encroach Node=158681
       1    4850    5060
Encroach Node=158472
       1    4840  5080.6
Encroach Node=157993
       1 4859.54 5129.78
Encroach Node=157406
       1    4973  5130.9
Encroach Node=157022
       1  4966.9  5090.9
Encroach Node=156647
       1    4981  5132.3
Encroach Node=156076
       1 4857.41 5139.31
Encroach Node=155595
       1    4970  5181.9
Encroach Node=154882
       1 4856.96 5251.25
Encroach Node=154493
       1 4815.99 5174.66
Encroach Node=154076
       1 4800.63 5032.58
Encroach Node=153373
       1 4878.36    5025
Encroach Node=152971
       1 4917.63  5112.3
Encroach Node=152443
       1 4899.72 5053.42
Encroach Node=151875
       1  4969.5 5178.79
Encroach Node=151434
       1 4871.47 5073.17
Encroach Node=151155
       1    4880    5070
Encroach Node=150875
       1    4930    5035
Encroach Node=150768
       1  4961.9    5060
Encroach Node=150493
       1 4929.91 5108.98
Encroach Node=150073
       1  4822.5  5136.9
Encroach Node=149648
       1 4886.69    5160
Encroach Node=149105
       1 4768.07  5031.2
Encroach Node=148556
       1 4812.48 5063.97
Encroach Node=147937
       1 4849.66 5110.63
Encroach Node=147626
       1 4910.24 5047.91
Encroach Node=147250
       1  4939.5  5061.2
Encroach Node=146493
       1 4904.63 5092.31
Encroach Node=145849
       1 4870.95    5188
Encroach Node=145423
       1 4892.68 5250.31
Encroach Node=144963
       1 4870.31 5121.35
Encroach Node=144534
       1 4860.66 5079.24
Encroach Node=144105
       1 4771.78 5064.15
Encroach Node=143463
       1  4977.9 5189.22
Encroach Node=143155
       1    4943    5056
Encroach Node=143030
       1  4908.7  5086.3
Encroach Node=142764
       1 4728.12 5058.55
Encroach Node=142382
       1 4551.91 5154.25
Encroach Node=141913
       1 4638.48 5217.76
Encroach Node=141543
       1 4776.51 5325.75
Encroach Node=141079
       1  4940.6 5461.07
Encroach Node=140557
       1 4850.31 5207.65
Encroach Node=140029
       1  4861.3 5046.21
Encroach Node=139493
       1 4929.84  5062.4
Encroach Node=139082
       1 4853.35 5114.53
Encroach Node=138493
       1 4610.56 5135.89
Encroach Node=138075
       1 4705.61  5031.3
Encroach Node=137713
       1 4870.67  5043.9
Encroach Node=137548
       1 4950.99  5055.2
Encroach Node=137498
       1 4955.99  5045.2
Encroach Node=137226
       1 4944.59  5023.9
Encroach Node=137020
       1 4938.14    5028
Encroach Node=136690
       1  4975.1  5025.4
Encroach Node=136523
       1    4971    5040
Encroach Node=136353
       1 4956.15 5059.13
Encroach Node=136222
       1  4953.6 5046.58
Encroach Node=136064
       1    4910    5025
Encroach Node=135868
       1  4894.7  5029.8
Encroach Node=135516
       1    4878    5120
Encroach Node=135271
       1 4875.82 5129.35
Encroach Node=134983
       1 4787.64  5172.5
Encroach Node=134418
       1  4820.3  5171.6
Encroach Node=134320
       1  4840.3  5161.6
Encroach Node=133871
       1 4769.35  5035.3
Encroach Node=133493
       1 4535.15  5041.6
Encroach Node=132982
       1 4441.85  5034.8
Encroach Node=132422
       1  4608.8  5031.9
Encroach Node=131796
       1  4588.4  5031.9
Encroach Node=131289
       1 4871.79 5152.91
Encroach Node=131046
       1 4871.79 5152.91
Encroach Node=130571
       1 4607.51  5110.8
Encroach Node=130173
       1 4756.76    5080
Encroach Node=129949
       1 4756.86    5080
Encroach Node=129551
       1 4866.87 5070.85
Encroach Node=129164
       1 4860.73 5077.62
Encroach Node=128543
       1 4854.35    5150
Encroach Node=128201
       1    4900 5094.98
Encroach Node=128073
       1  4950.3 5094.98
Encroach Node=127819
       1    4940    5063
Encroach Node=127098
       1 4838.43  5084.5
Encroach Node=126472
       1 4683.01  5072.3
Encroach Node=126085
       1 4672.14  5036.6
Encroach Node=125359
       1 4653.08  5036.6
Encroach Node=124669
       1 4622.96 5258.54
Encroach Node=124068
       1 4740.43 5077.95
Encroach Node=123285
       1 4870.65  5059.2
Encroach Node=122880
       1    4868 5086.11
Encroach Node=122735
       1    4868 5091.11
Encroach Node=122360
       1 4750.42 5194.82
Encroach Node=121860
       1 4724.86 5246.58
Encroach Node=121082
       1 4646.24 5170.69
Encroach Node=120451
       1 4676.18 5362.97
Encroach Node=119871
       1 4641.94 5142.81
Encroach Node=119435
       1  4657.9  5039.8
Encroach Node=119313
       1  4657.9  5039.8
Encroach Node=119016
       1 4775.55 5128.16
Encroach Node=118493
       1 4892.33 5515.39
Encroach Node=118086
       1  4768.8  5424.1
Encroach Node=117602
       1 4720.16 5272.48
Encroach Node=116993
       1 4180.76 5264.59
Encroach Node=116493
       1 4394.98  5473.1
Encroach Node=116000
       1 4522.79 5512.23
Encroach Node=115511
       1 4535.85 5383.62
Encroach Node=114993
       1  4595.5 5492.21
Encroach Node=114493
       1 4595.44 5555.23
Encroach Node=113779
       1 4688.63 5350.44
Encroach Node=113003
       1 4807.88 5136.47
Encroach Node=112493
       1 4786.42 5385.12
Encroach Node=111900
       1 4697.74 5236.15
Encroach Node=111348
       1 4868.66 5142.37
Encroach Node=110681
       1 4920.44 5449.89
Encroach Node=110093
       1 4681.27 5253.86
Encroach Node=109418
       1  4649.4 5574.99
Encroach Node=108830
       1 4741.81 5529.37
Encroach Node=108091
       1 4469.41  5073.5
Encroach Node=107493
       1 4223.79  5198.9
Encroach Node=106993
       1 4228.48 5314.31
Encroach Node=106626
       1    4460    5122
Encroach Node=106398
       1    4460    5062
Encroach Node=105686
       1    4500    5425
Encroach Node=105211
       1 4542.32 5498.23
Encroach Node=104449
       1 4525.07 5370.55
Encroach Node=103673
       1 4613.59 5266.06
Encroach Node=102993
       1 4674.86 5339.07
Encroach Node=102575
       1 4822.28 5358.29
Encroach Node=101990
       1 4668.53 5302.08
Encroach Node=101547
       1 4628.77 5270.42
Encroach Node=100993
       1 4787.01 5507.53
Encroach Node=100629
       1  4873.7  5280.4
Encroach Node=100214
       1 4728.24 5217.83
Encroach Node=99617
       1 4834.95 5201.75
Encroach Node=98876
       1 4787.54 5428.58
Encroach Node=98493
       1 4881.77 5205.46
Encroach Node=97993
       1 4872.36 5160.38
Encroach Node=97637
       1 4941.93 5100.74
Encroach Node=97140
       1  4910.2 5082.32
Encroach Node=96496
       1 4877.49 5207.41
Encroach Node=95993
       1 4696.14  5059.3
Encroach Node=95735
       1 4889.83 5134.95
Encroach Node=95177
       1 4651.01 5098.76
Encroach Node=94608
       1 4707.17 5179.36
Encroach Node=93865
       1 4652.81  5031.6
Encroach Node=93482
       1  4546.3  5045.2
Encroach Node=93103
       1 4401.58  5055.4
Encroach Node=92322
       1  4472.7    5064
Encroach Node=92044
       1 4650.65  5069.2
Encroach Node=91467
       1 4716.31  5059.2
Encroach Node=90920
       1    4820    5215
Encroach Node=90493
       1    4850    5250
Encroach Node=90261
       1    4897    5100
Encroach Node=90164
       1    4907    5090
Encroach Node=89874
       1  4833.3 5158.25
Encroach Node=89455
       1 4791.36 5112.81
Encroach Node=89079
       1  4908.8  5072.6
Encroach Node=88857
       1  4918.8  5072.6
Encroach Node=88612
       1 4819.19  5034.5
Encroach Node=88184
       1  4707.5  5040.8
Encroach Node=87493
       1  4867.3  5044.9
Encroach Node=86869
       1 4795.07 5122.58
Encroach Node=86493
       1 4553.14  5037.4
Encroach Node=85907
       1    4500    5300
BEGIN DESCRIPTION:
Floodway Run
END DESCRIPTION:
Computation Interval=1HOUR
Output Interval=1HOUR
Run HTab= 0
Run UNet= 0
Run PostProcess= 0
UNET Theta= 1
UNET Theta Warmup= 1
UNET ZTol= 0.02
UNET ZSATol= 0.05
UNET MxIter= 20
UNET MaxInSteps= 0
UNET DtIC= 0
UNET DtMin= 0
UNET MaxCRTS= 20
UNET WFStab= 2
UNET SFStab= 1
UNET WFX= 1
UNET SFX= 1
UNET DSS MLevel= 4
UNET DZMax Abort= 100
UNET Convert EG Bridges=-1
UNET Use Existing IB Tables=-1
UNET Froude Reduction=False
UNET Froude Limit= 1
UNET Froude Power= 10
Instantaneous Interval=1HOUR
Write IC File= 0
Echo Input=False
Echo Output=False
Write Detailed= 0
Detailed Automatic Start=False, 10

--- Fourth Creek.p01 (plan) ---

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Plan Title=Multiple Run
Short Identifier=Multiple
Geom File= g01
Flow File= f01
Encroach Param= -1, 0, 0, 0
Multiple Run

--- Fourth Creek.f02 (steady flow) ---

Flow Title=Floodway
Number of Profiles=2
Profile Names=100-year,100-FW
River Rch & RM= Fourth Creek,Reach-1,183603
    1241    1241
River Rch & RM= Fourth Creek,Reach-1,181197
    1504    1504
River Rch & RM= Fourth Creek,Reach-1,178946
    1771    1771
River Rch & RM= Fourth Creek,Reach-1,174742
    2055    2055
River Rch & RM= Fourth Creek,Reach-1,170099
    2320    2320
River Rch & RM= Fourth Creek,Reach-1,165485
    2548    2548
River Rch & RM= Fourth Creek,Reach-1,160562
    3015    3015
River Rch & RM= Fourth Creek,Reach-1,156076
    3261    3261
River Rch & RM= Fourth Creek,Reach-1,152443
    3525    3525
River Rch & RM= Fourth Creek,Reach-1,148556
    3727    3727
River Rch & RM= Fourth Creek,Reach-1,144105
    3907    3907
River Rch & RM= Fourth Creek,Reach-1,141913
    4037    4037
River Rch & RM= Fourth Creek,Reach-1,137226
    6713    6713
River Rch & RM= Fourth Creek,Reach-1,135868
    7137    7137
River Rch & RM= Fourth Creek,Reach-1,134418
    8587    8587
River Rch & RM= Fourth Creek,Reach-1,130173
    8776    8776
River Rch & RM= Fourth Creek,Reach-1,128201
    9816    9816
River Rch & RM= Fourth Creek,Reach-1,124669
   10019   10019
River Rch & RM= Fourth Creek,Reach-1,120451
   10322   10322
River Rch & RM= Fourth Creek,Reach-1,111900
   10817   10817
River Rch & RM= Fourth Creek,Reach-1,107493
   11003   11003
River Rch & RM= Fourth Creek,Reach-1,104449
   11187   11187
River Rch & RM= Fourth Creek,Reach-1,101547
   11336   11336
River Rch & RM= Fourth Creek,Reach-1,92044
   11519   11519
River Rch & RM= Fourth Creek,Reach-1,88184
   11616   11616
River Rch & RM= Fourth Creek,Reach-1,85907
   11692   11692
Boundary for River Rch & Prof#=Fourth Creek,Reach-1,1
Up Type=0
Dn Type=1
Dn Known WS=729.51
Boundary for River Rch & Prof#=Fourth Creek,Reach-1,2
Up Type=0
Dn Type=1
Dn Known WS=730.43

--- Fourth Creek.f01 (steady flow) ---

Flow Title=Multiple
Number of Profiles=4
Profile Names=10-year,50-year,100-year,500-year
River Rch & RM= Fourth Creek,Reach-1,183603
     573    1011    1241    1901
River Rch & RM= Fourth Creek,Reach-1,181197
     703    1229    1504    2289
River Rch & RM= Fourth Creek,Reach-1,178946
     836    1451    1771    2683
River Rch & RM= Fourth Creek,Reach-1,174742
     978    1687    2055    3097
River Rch & RM= Fourth Creek,Reach-1,170099
    1113    1909    2320    3484
River Rch & RM= Fourth Creek,Reach-1,165485
    1229    2100    2548    3815
River Rch & RM= Fourth Creek,Reach-1,160562
    1468    2491    3015    4489
River Rch & RM= Fourth Creek,Reach-1,156076
    1596    2698    3261    4844
River Rch & RM= Fourth Creek,Reach-1,152443
    1733    2920    3525    5222
River Rch & RM= Fourth Creek,Reach-1,148556
    1838    3091    3727    5512
River Rch & RM= Fourth Creek,Reach-1,144105
    1932    3242    3907    5769
River Rch & RM= Fourth Creek,Reach-1,141913
    2000    3352    4037    5955
River Rch & RM= Fourth Creek,Reach-1,137226
    4057    6048    6713    8533
River Rch & RM= Fourth Creek,Reach-1,135868
    4396    6458    7137    8983
River Rch & RM= Fourth Creek,Reach-1,134418
    5616    7878    8587   10467
River Rch & RM= Fourth Creek,Reach-1,130173
    5722    8043    8776   10727
River Rch & RM= Fourth Creek,Reach-1,128201
    6607    9061    9816   11800
River Rch & RM= Fourth Creek,Reach-1,124669
    6752    9248   10019   12042
River Rch & RM= Fourth Creek,Reach-1,120451
    6964    9527   10322   12410
River Rch & RM= Fourth Creek,Reach-1,111900
    7286    9973   10817   13036
River Rch & RM= Fourth Creek,Reach-1,107493
    7394   10136   11003   13287
River Rch & RM= Fourth Creek,Reach-1,104449
    7490   10294   11187   13549
River Rch & RM= Fourth Creek,Reach-1,101547
    7555   10415   11336   13773
River Rch & RM= Fourth Creek,Reach-1,92044
    7629   10564   11519   14058
River Rch & RM= Fourth Creek,Reach-1,88184
    7669   10642   11616   14207
River Rch & RM= Fourth Creek,Reach-1,85907
    7707   10706   11692   14317
Boundary for River Rch & Prof#=Fourth Creek,Reach-1,1
Up Type=0
Dn Type=3
Dn Slope=0.0003
Boundary for River Rch & Prof#=Fourth Creek,Reach-1,2
Up Type=0
Dn Type=3
Dn Slope=0.0003
Boundary for River Rch & Prof#=Fourth Creek,Reach-1,3
Up Type=0
Dn Type=1
Dn Known WS=729.51
Boundary for River Rch & Prof#=Fourth Creek,Reach-1,4
Up Type=0
Dn Type=3
Dn Slope=0.0003

--- Fourth Creek.g01 (geometry) ---

Geom Title=Existing Conditions

River Reach=Fourth Creek,Reach-1
Reach XY= 30
      1405856.13       771986.06      1414960.05       769258.68
      1421823.00       765678.94      1426430.00       767623.44
      1430739.13       767395.56      1433355.38       764505.75
      1438893.38       761867.56      1442994.63       754783.75
      1449365.50       752539.31      1450687.75       750672.63
      1454669.63       750422.63      1455447.50       747633.75
      1461152.38       743763.69      1471772.38       741959.31
      1475147.76       740625.45      1476582.00       738490.19
      1481866.88       739961.00      1485346.13       737389.25
      1490764.25       740310.56      1495259.38       739256.13
      1499278.25       741624.56      1501695.38       740898.19
      1505782.47       743247.54      1511173.63       743536.13
      1511073.50       745388.44      1514279.61       748672.94
      1518340.88       750610.13      1520123.63       749786.81
      1522012.00       750970.44      1528826.88       747343.44

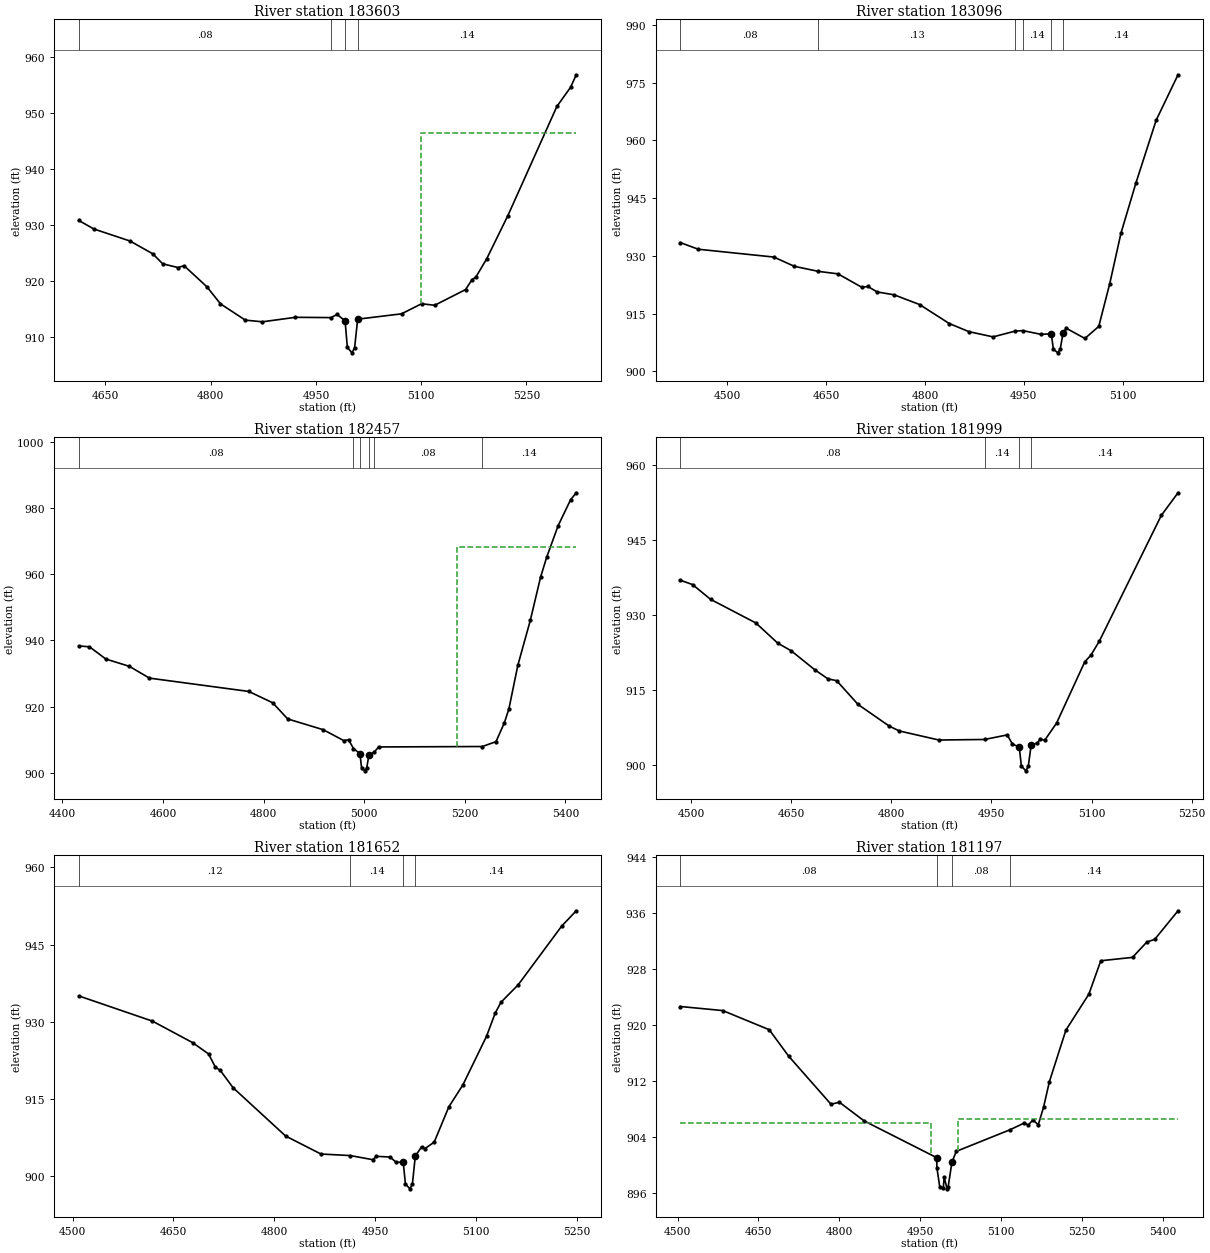
Type RM Length L Ch R = 1,183603,502,507,502
BEGIN DESCRIPTION:
Fourth Creek 310.0
END DESCRIPTION:
XS GIS Cut Line= 5
      1407575.86       771253.90      1407469.96       771046.25
      1407353.69       770938.29      1407301.79       770871.86
      1407285.18       770639.31
#Sta/Elev= 30
  4611.9  930.77  4633.6  929.24  4685.2  927.09  4717.5  924.81  4731.6  923.03
  4753.5  922.36  4762.0  922.70  4794.7  918.92  4813.9  915.89  4849.3  912.98
  4873.7  912.68  4920.8  913.48  4971.4  913.43  4980.3  913.99  4991.6  912.83
  4994.8  908.10  5001.5  907.14  5005.2  908.09  5009.5  913.15  5072.0  914.10
  5100.6  915.90  5119.3  915.63  5163.3  918.43  5172.6  920.21  5177.9  920.64
  5193.3  923.89  5223.5  931.60  5293.5  951.12  5313.0  954.53  5321.1  956.77
#Mann=4,-1,0
  4611.9    0.08       0  4971.4    0.14       0  4991.6   0.042       0
  5009.5    0.14       0
#XS Ineff=2,0
       0                 5099.30    0.00  946.42
Permanent Ineff=
       F       F
Bank Sta=4991.6,5009.5
XS Rating Curve= 0
Exp/Cntr=0.3,0.1

Type RM Length L Ch R = 1,183096,622,639,652
BEGIN DESCRIPTION:
Fourth Creek 309.0
END DESCRIPTION:
XS GIS Cut Line= 3
      1408121.58       771003.99      1407723.97       770596.90
      1407588.25       770470.66
#Sta/Elev= 30
  4429.4  933.44  4456.3  931.73  4570.9  929.70  4601.9  927.30  4638.3  925.99
  4668.2  925.34  4704.1  921.87  4713.6  922.06  4727.4  920.66  4753.4  919.89
  4792.0  917.37  4837.0  912.44  4866.9  910.33  4903.4  908.98  4936.6  910.47
  4948.3  910.61  4976.5  909.63  4991.6  909.80  4994.8  905.80  5001.5  904.84
  5005.2  905.79  5009.5  910.05  5014.3  911.22  5042.6  908.57  5063.6  911.69
  5080.2  922.74  5097.3  935.91  5119.9  948.89  5150.7  965.23  5183.8  977.01
#Mann=6,-1,0
  4429.4    0.08       0  4638.3    0.13       0  4936.6    0.08       0
  4948.3    0.14       0  4991.6   0.042       0  5009.5    0.14       0
Bank Sta=4991.6,5009.5
XS Rating Curve= 0
Exp/Cntr=0.3,0.1

Type RM Length L Ch R = 1,182457,448,458,488
BEGIN DESCRIPTION:
Fourth Creek 308.0
END DESCRIPTION:
XS GIS Cut Line= 3
      1408487.68       770865.18      1408292.00       770338.13
      1408121.60       769946.83
#Sta/Elev= 30
  4432.6  938.34  4453.9  938.09  4486.5  934.38  4533.4  932.16  4573.2  928.60
  4770.7  924.57  4818.2  921.13  4848.0  916.25  4918.6  912.99  4959.4  909.70
  4969.0  909.96  4978.8  907.29  4991.6  905.74  4994.8  901.50  5001.5  900.54
  5005.2  901.49  5009.5  905.44  5019.5  906.10  5028.7  907.77  5234.8  907.90
  5262.1  909.37  5278.7  915.08  5287.7  919.28  5305.5  932.50  5330.2  946.05
  5350.7  959.18  5363.0  965.27  5385.7  974.79  5410.5  982.63  5421.6  984.70
#Mann=6,-1,0
  4432.6    0.08       0  4978.8    0.14       0  4991.6   0.042       0
  5009.5    0.14       0  5019.5    0.08       0  5234.8    0.14       0
#XS Ineff=2,0
       0                 5184.10    0.00  968.34
Permanent Ineff=
       F       F
Bank Sta=4991.6,5009.5
XS Rating Curve= 0
Exp/Cntr=0.3,0.1

Type RM Length L Ch R = 1,181999,365,347,340
BEGIN DESCRIPTION:
Fourth Creek 307.0
END DESCRIPTION:
XS GIS Cut Line= 3
      1408756.53       770764.20      1408731.29       770246.61
      1408731.29       770019.41
#Sta/Elev= 30
  4484.1  936.94  4502.2  936.08  4529.1  933.14  4597.1  928.41  4629.7  924.40
  4650.0  922.86  4684.9  919.12  4705.0  917.26  4718.0  916.91  4750.1  912.16
  4797.0  907.82  4811.9  906.87  4871.3  905.06  4939.8  905.17  4973.6  906.08
  4981.5  904.23  4991.6  903.69  4994.8  899.87  5001.5  898.91  5005.2  899.86
  5009.5  904.08  5018.2  904.44  5023.4  905.25  5029.7  905.00  5047.5  908.43
  5089.8  920.66  5098.9  921.98  5111.5  924.76  5204.4  949.87  5229.5  954.40
#Mann=4,-1,0
  4484.1    0.08       0  4939.8    0.14       0  4991.6   0.042       0
  5009.5    0.14       0
Bank Sta=4991.6,5009.5
XS Rating Curve= 0
Exp/Cntr=0.3,0.1

Type RM Length L Ch R = 1,181652,464,455,468
BEGIN DESCRIPTION:
Fourth Creek 306.0
END DESCRIPTION:
XS GIS Cut Line= 4
      1409044.97       770694.72      1409108.08       770293.95
      1409079.68       770221.37      1408981.87       769984.73
#Sta/Elev= 30
  4509.1  935.01  4618.7  930.10  4678.3  925.93  4702.2  923.71  4712.1  921.19
  4719.5  920.53  4738.6  917.15  4816.7  907.76  4869.2  904.26  4912.7  903.96
  4946.3  903.16  4951.8  903.81  4972.2  903.68  4980.8  902.66  4991.6  902.66
  4994.8  898.45  5001.5  897.49  5005.2  898.44  5009.5  903.85  5018.8  905.66
  5023.9  905.32  5037.6  906.57  5059.4  913.44  5080.2  917.69  5115.4  927.15
  5128.2  931.63  5136.9  933.77  5162.5  937.17  5227.2  948.59  5248.8  951.56
#Mann=4,-1,0
  4509.1    0.12       0  4912.7    0.14       0  4991.6   0.042       0
  5009.5    0.14       0
Bank Sta=4991.6,5009.5
XS Rating Curve= 0
Exp/Cntr=0.3,0.3

Type RM Length L Ch R = 1,181197,58,60,62
BEGIN DESCRIPTION:
Unknown Rd (FC) us
END DESCRIPTION:
XS GIS Cut Line= 4
      1409450.26       770450.59      1409454.81       769992.55
      1409409.24       769757.85      1409516.35       769559.58
#Sta/Elev= 30
  4505.5  922.65  4583.8  922.07  4670.0  919.33  4706.2  915.53  4784.5  908.67
  4800.2  908.95  4846.0  906.28  4980.8  901.01  4980.9  899.58  4986.2  896.84
  4992.8  896.69  4994.4  898.24  4999.8  896.56  5001.9  896.89  5008.7  900.33
  5016.7  901.92  5117.0  905.03  5143.1  905.99  5150.1  905.68  5159.1  906.42
  5168.8  905.72  5178.6  908.21  5189.5  911.90  5220.1  919.27  5262.7  924.42
  5284.8  929.20  5343.6  929.68  5370.1  931.87  5384.8  932.26  5428.0  936.35
#Mann=4,-1,0
  4505.5    0.08       0  4980.8   0.042       0  5008.7    0.08       0
  5117.0    0.14       0
#XS Ineff=2,0
    0.00 4969.20  905.97 5020.00    0.00  906.50
Permanent Ineff=
       F       F
Bank Sta=4980.8,5008.7
XS Rating Curve= 0
Exp/Cntr=0.5,0.3

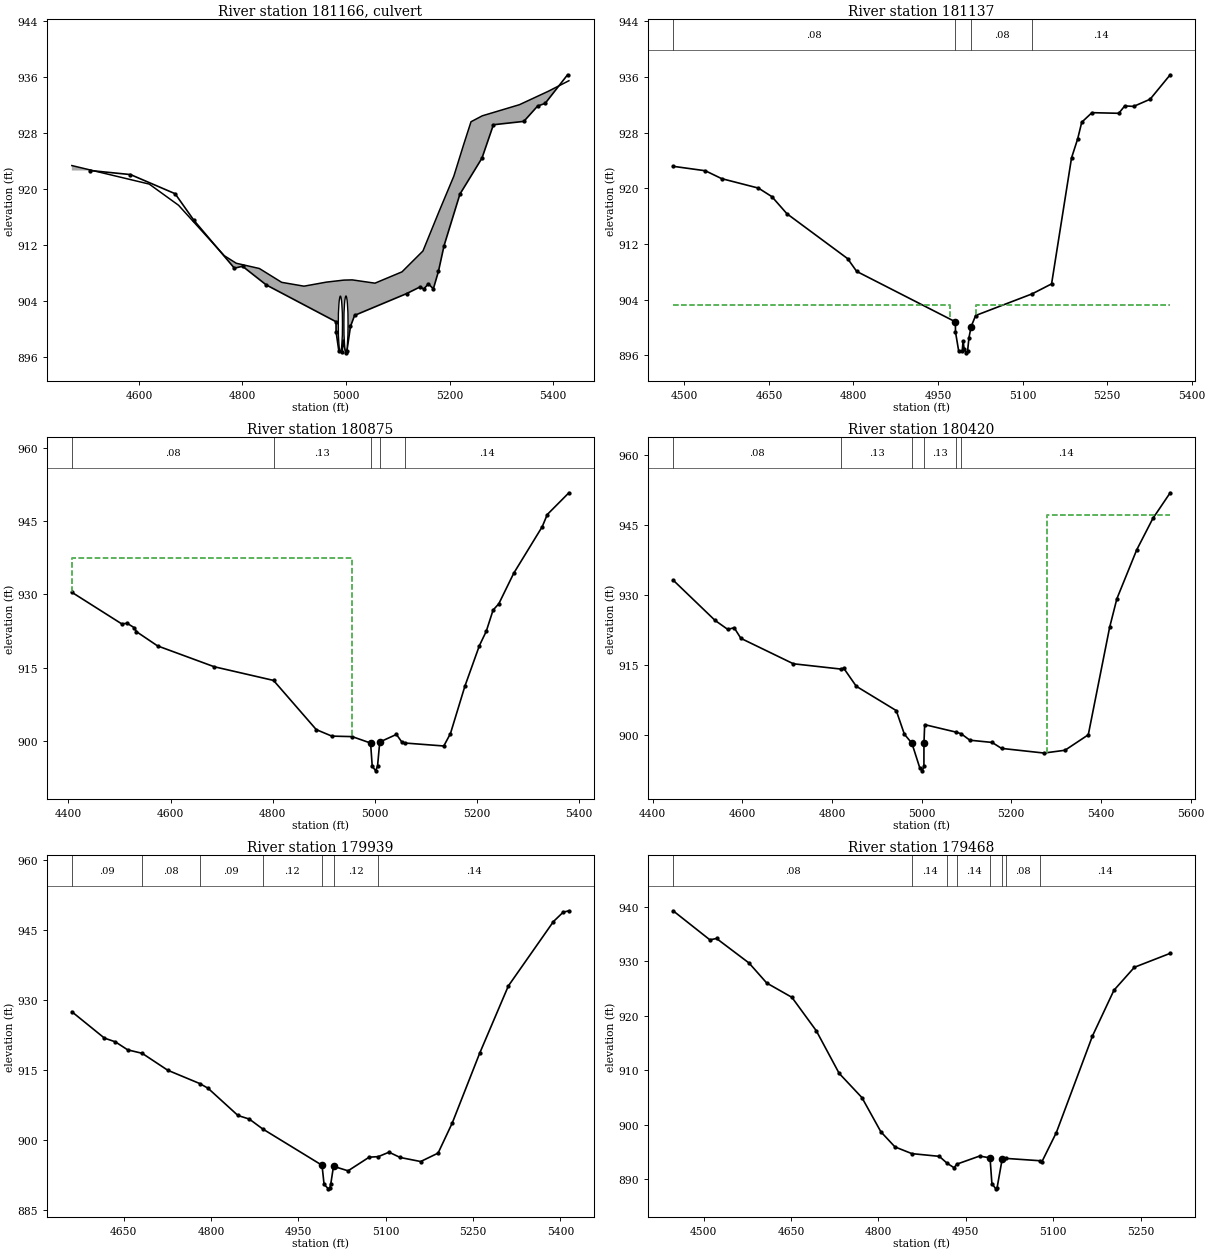
Type RM Length L Ch R =2,181166,,,
BEGIN DESCRIPTION:
Unknown Rd (FC) TOR
Structure ID: I_FC_18B
Detailed Survey Structure
END DESCRIPTION:
Bridge Culvert--1,0,-1,-1,0
Deck Dist Width WeirC Skew NumUp NumDn MinLoCord MaxHiCord MaxSubmerge Is_Ogee
16,30,3,,22,22,,,,0,1,1,,,
  4470.5  4620.0  4676.6  4765.0  4788.1  4832.7  4875.8  4918.9  4962.1  4996.2
  5012.1  5056.0  5108.2  5148.7  5179.6  5208.3  5227.4  5241.5  5263.3  5335.0
  5390.5  5430.6
  923.36  920.71  917.68  910.46  909.38  908.63  906.65  906.10  906.68  906.97
  907.00  906.53  908.15  911.14  916.76  921.84  926.39  929.63  930.48  932.07
  933.98  935.50
  876.56  876.56  876.56  876.56  876.56  876.56  876.56  876.56  876.56  876.56
  876.56  876.56  876.56  876.56  876.56  876.56  876.56  876.56  876.56  876.56
  876.56  876.56
  4470.5  4620.0  4676.6  4765.0  4788.1  4832.7  4875.8  4918.9  4962.1  4996.2
  5012.1  5056.0  5108.2  5148.7  5179.6  5208.3  5227.4  5241.5  5263.3  5335.0
  5390.5  5430.6
  923.36  920.71  917.68  910.46  909.38  908.63  906.65  906.10  906.68  906.97
  907.00  906.53  908.15  911.14  916.76  921.84  926.39  929.63  930.48  932.07
  933.98  935.50
  876.40  876.40  876.40  876.40  876.40  876.40  876.40  876.40  876.40  876.40
  876.40  876.40  876.40  876.40  876.40  876.40  876.40  876.40  876.40  876.40
  876.40  876.40
Culvert=1,8,,30,0.024,0.5,1,2,1,896.67,4989.2,896.83,4989.2,Culvert #1,0,16
Culvert Bottom n=0.024
Culvert Bottom Depth=0
Culvert Depth Blocked=0
Culvert=1,8,,30,0.024,0.5,1,2,1,896.69,5000,896.33,5000,Culvert #2,0,16
Culvert Bottom n=0.024
Culvert Bottom Depth=0
Culvert Depth Blocked=0
BC Design=,,0,,0,,,,,,

Type RM Length L Ch R = 1,181137,259,262,264
BEGIN DESCRIPTION:
Unknown Rd (FC) ds
END DESCRIPTION:
XS GIS Cut Line= 4
      1409486.71       770443.78      1409504.95       769974.32
      1409468.49       769705.44      1409532.29       769580.10
#Sta/Elev= 30
  4480.0  923.15  4537.2  922.51  4566.1  921.38  4631.4  920.02  4655.3  918.79
  4681.9  916.34  4789.5  909.90  4805.7  908.06  4980.8  900.82  4980.9  899.39
  4986.5  896.68  4992.8  896.62  4994.4  898.05  4996.4  896.89  4999.8  896.37
  5002.3  896.57  5004.9  898.57  5008.7  900.14  5016.7  901.73  5117.0  904.84
  5151.4  906.27  5186.8  924.36  5197.7  927.09  5204.9  929.48  5223.0  930.85
  5270.6  930.76  5281.2  931.82  5297.0  931.75  5326.2  932.78  5361.8  936.29
#Mann=4,-1,0
  4480.0    0.08       0  4980.8   0.042       0  5008.7    0.08       0
  5117.0    0.14       0
#XS Ineff=2,0
    0.00 4971.50  903.20 5017.00    0.00  903.20
Permanent Ineff=
       F       F
Bank Sta=4980.8,5008.7
XS Rating Curve= 0
Exp/Cntr=0.5,0.3

Type RM Length L Ch R = 1,180875,451,455,516
BEGIN DESCRIPTION:
Fourth Creek 305.0
END DESCRIPTION:
XS GIS Cut Line= 3
      1409775.21       770489.60      1409753.12       769893.17
      1409731.03       769517.66
#Sta/Elev= 30
  4406.8  930.45  4504.3  923.99  4515.2  924.09  4529.1  923.19  4533.2  922.39
  4574.6  919.47  4685.5  915.20  4801.6  912.40  4885.3  902.32  4915.8  900.99
  4955.6  900.89  4991.6  899.57  4994.8  894.84  5001.5  893.88  5005.2  894.83
  5009.5  899.78  5042.2  901.34  5053.0  899.74  5059.7  899.57  5134.9  898.97
  5147.9  901.51  5176.2  911.22  5204.6  919.53  5218.0  922.46  5231.4  926.81
  5242.6  928.10  5271.8  934.35  5327.6  943.89  5337.5  946.38  5379.8  950.83
#Mann=5,-1,0
  4406.8    0.08       0  4801.6    0.13       0  4991.6   0.042       0
  5009.5    0.13       0  5059.7    0.14       0
#XS Ineff=2,0
    0.00 4955.70  937.57               0
Permanent Ineff=
       F       F
Bank Sta=4991.6,5009.5
XS Rating Curve= 0
Exp/Cntr=0.3,0.1

Type RM Length L Ch R = 1,180420,469,481,467
BEGIN DESCRIPTION:
Fourth Creek 304.0
END DESCRIPTION:
XS GIS Cut Line= 3
      1409920.37       770464.38      1410172.84       769965.75
      1410516.80       769536.58
#Sta/Elev= 30
  4445.7  933.18  4539.3  924.52  4567.5  922.60  4581.9  922.95  4596.9  920.67
  4714.0  915.21  4821.2  914.06  4826.1  914.29  4854.3  910.38  4943.5  905.16
  4961.6  900.09  4978.4  898.15  4996.0  892.85  5001.5  892.22  5005.2  893.17
  5005.3  898.15  5006.9  902.14  5076.7  900.54  5088.2  900.19  5107.7  898.80
  5157.3  898.32  5178.4  897.04  5273.1  896.04  5319.9  896.64  5371.9  899.96
  5419.6  923.07  5435.7  929.18  5480.0  939.69  5515.9  946.41  5554.6  951.93
#Mann=6,-1,0
  4445.7    0.08       0  4821.2    0.13       0  4978.4   0.042       0
  5005.3    0.13       0  5076.7    0.12       0  5088.2    0.14       0
#XS Ineff=2,0
       0                 5279.10    0.00  947.09
Permanent Ineff=
       F       F
Bank Sta=4978.4,5005.3
XS Rating Curve= 0
Exp/Cntr=0.3,0.1

Type RM Length L Ch R = 1,179939,509,471,438
BEGIN DESCRIPTION:
Fourth Creek 303.0
END DESCRIPTION:
XS GIS Cut Line= 4
      1410252.37       770559.03      1410549.00       770230.84
      1410602.22       770173.40      1410880.36       769991.00
#Sta/Elev= 30
  4561.3  927.51  4617.2  921.86  4635.9  921.06  4657.2  919.34  4682.0  918.60
  4726.0  914.97  4780.7  912.13  4795.0  911.13  4846.5  905.28  4866.0  904.51
  4888.8  902.41  4990.8  894.62  4994.3  890.53  5001.7  889.57  5004.1  889.77
  5005.7  890.52  5010.5  894.40  5035.5  893.43  5071.7  896.35  5087.4  896.47
  5105.8  897.42  5124.9  896.29  5160.1  895.42  5190.0  897.22  5214.4  903.69
  5261.3  918.58  5310.7  933.04  5388.1  946.83  5404.7  948.82  5414.6  949.13
#Mann=7,-1,0
  4561.3    0.09       0  4682.0    0.08       0  4780.7    0.09       0
  4888.8    0.12       0  4990.8   0.042       0  5010.5    0.12       0
  5087.4    0.14       0
Bank Sta=4990.8,5010.5
XS Rating Curve= 0
Exp/Cntr=0.3,0.1

Type RM Length L Ch R = 1,179468,568,522,492
BEGIN DESCRIPTION:
Fourth Creek 302.0
END DESCRIPTION:
XS GIS Cut Line= 4
      1411031.84       771007.16      1410935.77       770792.61
      1410924.54       770480.14      1410925.00       770174.99
#Sta/Elev= 30
  4447.8  939.28  4510.9  933.94  4522.3  934.19  4578.1  929.68  4608.5  926.00
  4651.6  923.38  4693.5  917.23  4732.7  909.41  4771.8  904.95  4804.3  898.67
  4828.5  895.89  4857.5  894.66  4904.5  894.16  4918.0  892.89  4929.7  892.08
  4935.0  892.74  4973.6  894.21  4991.6  893.88  4994.8  889.15  5001.5  888.19
  5003.7  888.39  5012.4  893.64  5019.4  893.78  5077.7  893.35  5080.7  893.19
  5105.4  898.54  5167.4  916.29  5204.2  924.68  5239.3  928.90  5300.7  931.46
#Mann=8,-1,0
  4447.8    0.08       0  4857.5    0.14       0  4918.0    0.05       0
  4935.0    0.14       0  4991.6   0.042       0  5012.4    0.14       0
  5019.4    0.08       0  5077.7    0.14       0
Bank Sta=4991.6,5012.4
XS Rating Curve= 0
Exp/Cntr=0.3,0.1

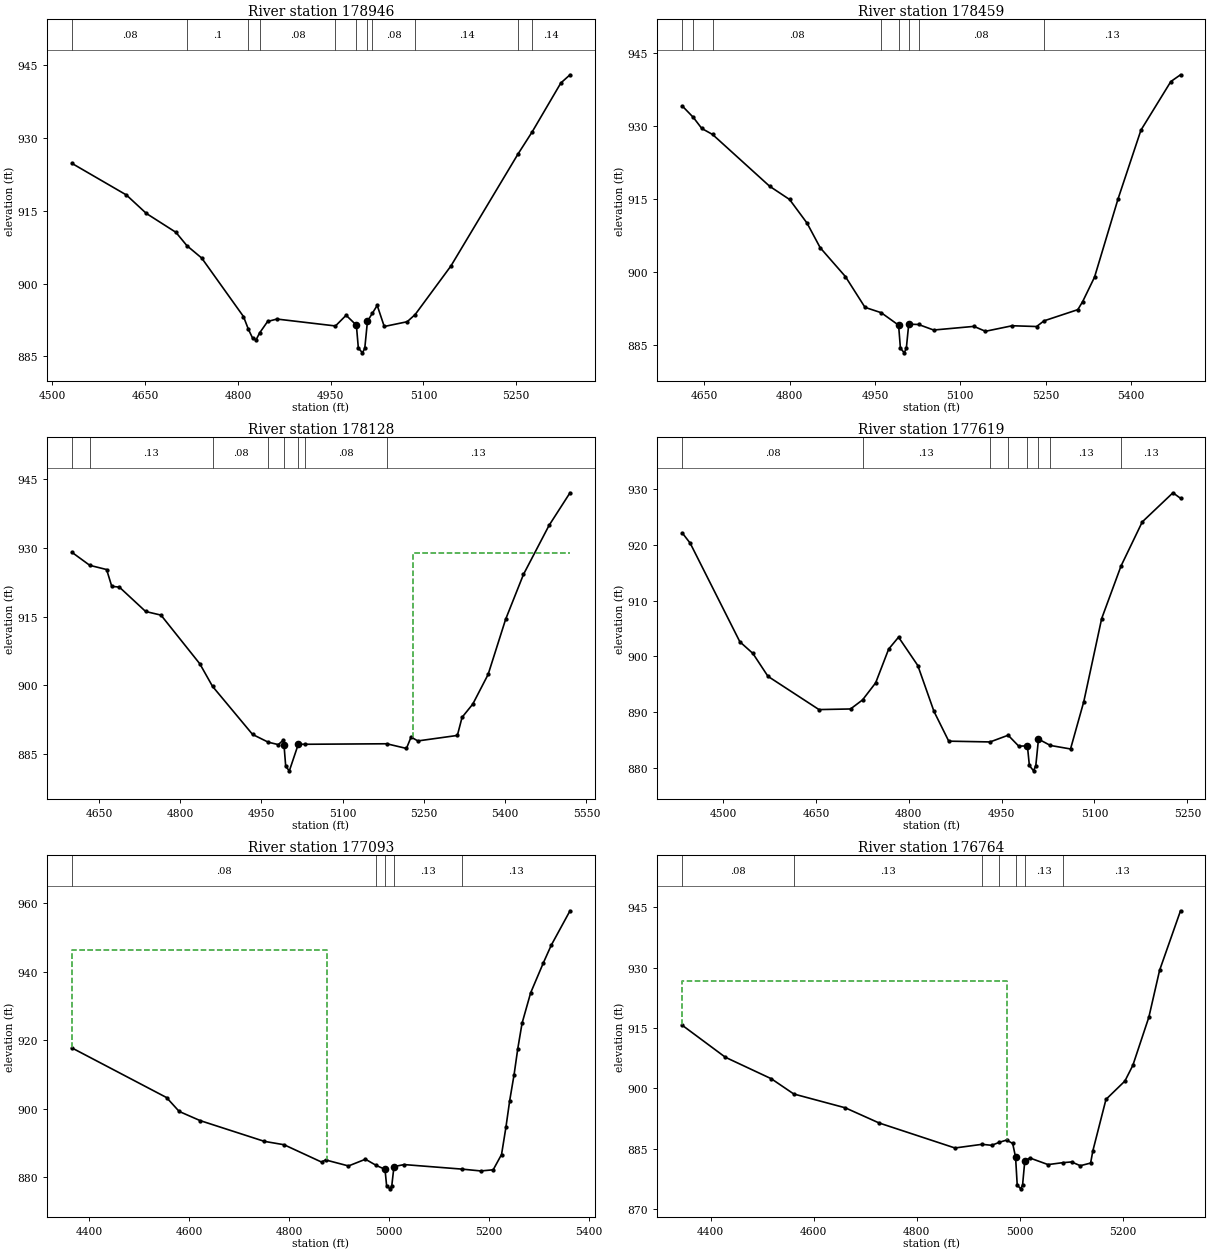
Type RM Length L Ch R = 1,178946,473,487,476
BEGIN DESCRIPTION:
Fourth Creek 301.0
END DESCRIPTION:
XS GIS Cut Line= 4
      1411777.26       770341.30      1411430.09       770243.46
      1411348.04       770180.34      1411075.04       769975.03
#Sta/Elev= 30
  4531.4  924.73  4619.5  918.23  4651.9  914.42  4699.7  910.54  4717.5  907.79
  4741.4  905.25  4809.0  893.21  4817.0  890.57  4824.0  888.71  4829.5  888.46
  4835.0  889.83  4848.0  892.20  4863.1  892.70  4957.8  891.28  4975.0  893.48
  4991.6  891.44  4994.8  886.71  5001.5  885.75  5005.2  886.70  5009.5  892.24
  5017.4  893.88  5025.3  895.51  5036.7  891.17  5073.8  892.15  5086.7  893.63
  5144.5  903.61  5252.9  926.62  5276.0  931.21  5322.4  941.27  5337.2  942.95
#Mann=11,-1,0
  4531.4    0.08       0  4717.5     0.1       0  4817.0    0.05       0
  4835.0    0.08       0  4957.8    0.14       0  4991.6   0.042       0
  5009.5    0.14       0  5017.4    0.08       0  5086.7    0.14       0
  5252.9    0.12       0  5276.0    0.14       0
Bank Sta=4991.6,5009.5
XS Rating Curve= 0
Exp/Cntr=0.3,0.1

Type RM Length L Ch R = 1,178459,323,331,379
BEGIN DESCRIPTION:
Fourth Creek 300.0 (Survey)
END DESCRIPTION:
XS GIS Cut Line= 3
      1411972.85       770132.03      1411698.33       769854.35
      1411322.76       769548.21
#Sta/Elev= 30
  4611.8  934.15  4631.1  931.82  4645.9  929.55  4664.8  928.32  4765.1  917.67
  4800.1  914.95  4830.8  910.09  4853.9  905.03  4898.2  899.10  4932.6  892.77
  4961.1  891.67  4991.6  889.11  4994.8  884.38  5001.5  883.42  5005.2  884.37
  5009.4  889.31  5026.6  889.25  5053.2  888.11  5124.0  888.86  5144.1  887.85
  5191.2  888.99  5234.0  888.83  5247.1  890.00  5306.4  892.30  5314.8  893.93
  5335.8  898.99  5377.2  915.11  5417.3  929.21  5469.8  939.20  5486.8  940.59
#Mann=8,-1,0
  4611.8    0.08       0  4631.1    0.13       0  4664.8    0.08       0
  4961.1    0.14       0  4991.6   0.042       0  5009.4    0.14       0
  5026.6    0.08       0  5247.1    0.13       0
Bank Sta=4991.6,5009.4
XS Rating Curve= 0
Exp/Cntr=0.3,0.1

Type RM Length L Ch R = 1,178128,505,509,512
BEGIN DESCRIPTION:
Fourth Creek 299.0
END DESCRIPTION:
XS GIS Cut Line= 4
      1412152.78       770040.58      1411972.88       769680.79
      1411849.81       769418.86      1411679.37       769267.36
#Sta/Elev= 30
  4600.0  929.05  4633.0  926.20  4664.1  925.28  4673.6  921.62  4687.7  921.44
  4736.2  916.12  4764.5  915.33  4836.2  904.70  4859.7  899.77  4933.6  889.28
  4962.6  887.58  4981.1  887.06  4989.7  887.97  4991.6  887.02  4994.8  882.29
  5001.5  881.33  5018.0  887.14  5030.6  887.13  5181.3  887.24  5217.7  886.22
  5226.2  888.70  5238.8  887.86  5311.7  889.06  5320.4  893.02  5340.2  895.91
  5368.5  902.38  5400.8  914.41  5433.7  924.20  5480.9  934.90  5519.7  942.04
#Mann=8,-1,0
  4600.0    0.08       0  4633.0    0.13       0  4859.7    0.08       0
  4962.6    0.14       0  4991.6   0.042       0  5018.0    0.14       0
  5030.6    0.08       0  5181.3    0.13       0
#XS Ineff=2,0
       0                 5229.00    0.00  928.93
Permanent Ineff=
       F       F
Bank Sta=4991.6,5018
XS Rating Curve= 0
Exp/Cntr=0.3,0.1

Type RM Length L Ch R = 1,177619,495,526,498
BEGIN DESCRIPTION:
Fourth Creek 298.0
END DESCRIPTION:
XS GIS Cut Line= 3
      1412645.06       769958.50      1412421.00       769444.11
      1412332.63       769216.86
#Sta/Elev= 30
  4434.1  922.12  4446.7  920.31  4527.0  902.63  4548.0  900.55  4572.4  896.44
  4654.8  890.48  4705.8  890.59  4725.2  892.21  4746.4  895.27  4767.4  901.32
  4783.4  903.46  4814.5  898.38  4840.7  890.14  4864.5  884.82  4931.3  884.68
  4960.5  885.88  4977.6  883.93  4991.6  883.97  4994.8  880.46  5001.5  879.50
  5005.2  880.45  5009.5  885.19  5028.7  884.05  5061.3  883.42  5082.7  891.90
  5111.6  906.79  5142.9  916.22  5177.2  924.12  5226.8  929.34  5239.0  928.35
#Mann=8,-1,0
  4434.1    0.08       0  4725.2    0.13       0  4931.3    0.08       0
  4960.5    0.13       0  4991.6   0.042       0  5009.5    0.13       0
  5028.7    0.13       0  5142.9    0.13       0
Bank Sta=4991.6,5009.5
XS Rating Curve= 0
Exp/Cntr=0.3,0.1

Type RM Length L Ch R = 1,177093,318,329,316
BEGIN DESCRIPTION:
Fourth Creek 297.0
END DESCRIPTION:
XS GIS Cut Line= 3
      1413108.95       769787.11      1412853.34       769206.48
      1412701.85       768878.26
#Sta/Elev= 30
  4365.6  917.76  4554.9  903.27  4580.1  899.22  4621.9  896.55  4750.3  890.49
  4789.8  889.50  4864.8  884.44  4872.7  885.07  4918.6  883.31  4952.5  885.27
  4974.3  883.45  4991.6  882.32  4994.8  877.59  5001.5  876.63  5005.2  877.58
  5009.5  883.12  5029.9  883.71  5145.2  882.39  5183.3  881.85  5207.9  882.19
  5224.6  886.65  5233.3  894.55  5240.9  902.38  5249.7  909.99  5257.1  917.58
  5265.6  924.95  5282.8  933.84  5308.3  942.62  5324.0  947.74  5361.5  957.78
#Mann=5,-1,0
  4365.6    0.08       0  4974.3    0.13       0  4991.6   0.042       0
  5009.5    0.13       0  5145.2    0.13       0
#XS Ineff=2,0
    0.00 4876.20  946.47               0
Permanent Ineff=
       F       F
Bank Sta=4991.6,5009.5
XS Rating Curve= 0
Exp/Cntr=0.3,0.1

Type RM Length L Ch R = 1,176764,268,271,267
BEGIN DESCRIPTION:
Fourth Creek 296.5
END DESCRIPTION:
XS GIS Cut Line= 4
      1413289.10       769695.26      1413212.79       769197.99
      1413138.95       769094.61      1413035.57       768774.63
#Sta/Elev= 30
  4345.2  915.68  4428.6  907.75  4517.8  902.40  4561.4  898.61  4661.2  895.18
  4726.8  891.41  4874.0  885.19  4926.5  886.10  4945.3  885.85  4959.2  886.56
  4974.2  887.16  4986.0  886.31  4991.6  882.92  4994.8  875.99  5001.5  875.03
  5005.2  875.98  5009.5  881.95  5019.4  882.70  5054.6  881.06  5083.4  881.54
  5100.3  881.72  5117.2  880.78  5137.2  881.44  5141.6  884.51  5167.0  897.27
  5203.7  901.83  5219.1  905.73  5250.2  917.72  5271.0  929.36  5311.6  944.17
#Mann=7,-1,0
  4345.2    0.08       0  4561.4    0.13       0  4926.5    0.08       0
  4959.2    0.13       0  4991.6   0.042       0  5009.5    0.13       0
  5083.4    0.13       0
#XS Ineff=2,0
    0.00 4975.10  926.62               0
Permanent Ineff=
       F       F
Bank Sta=4991.6,5009.5
XS Rating Curve= 0
Exp/Cntr=0.3,0.1