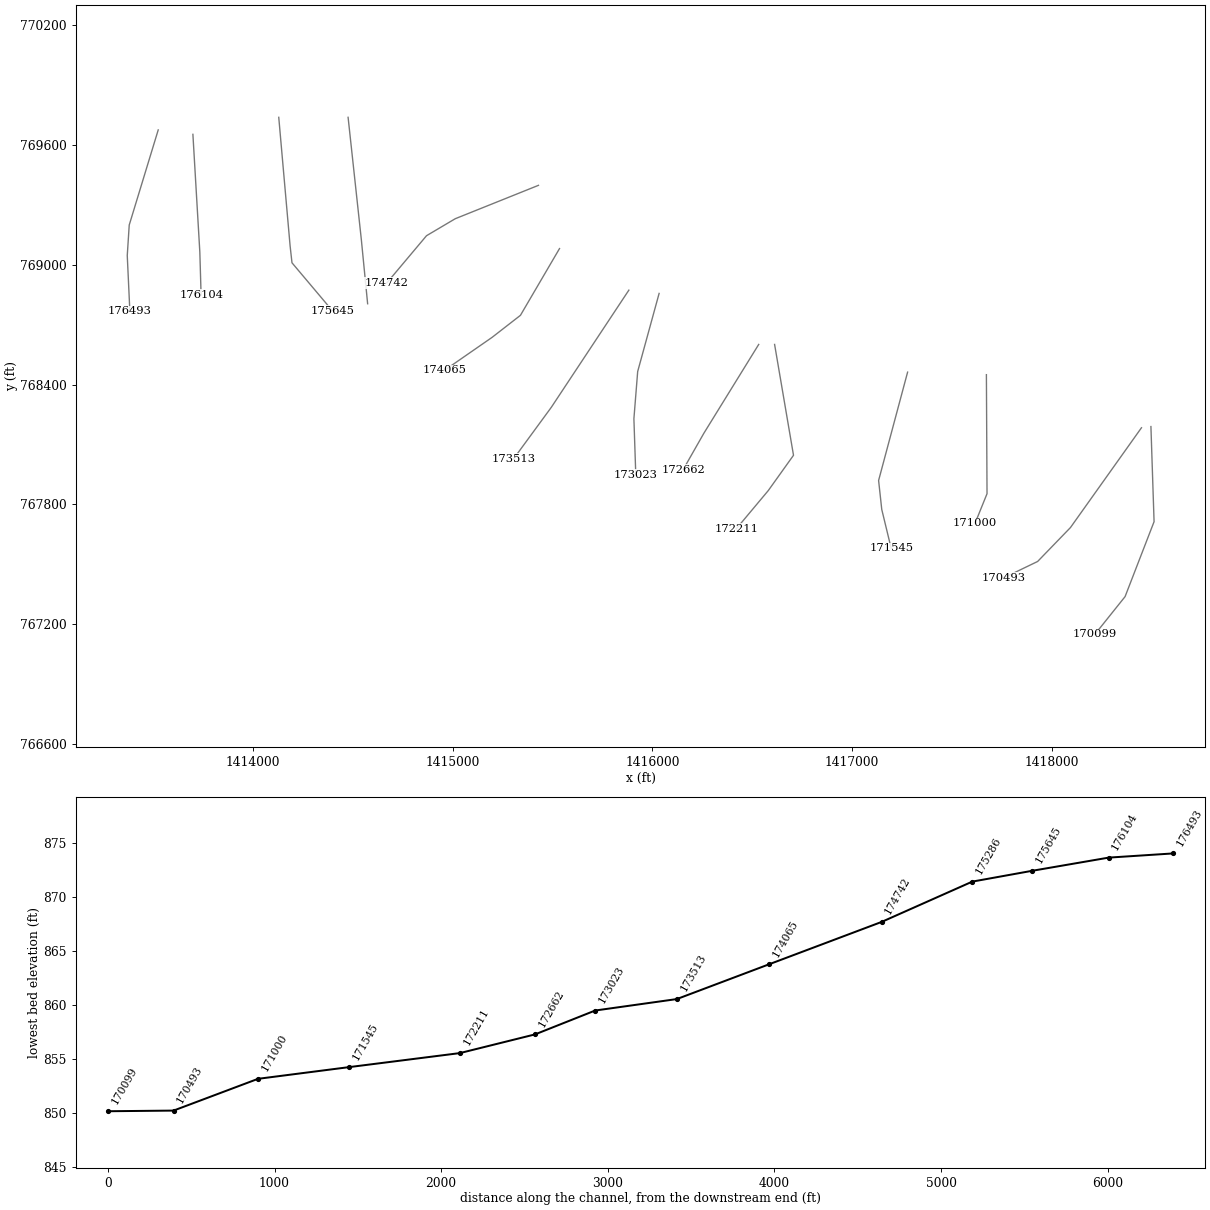
HEC-RAS study Fourth Creek.prj: Fourth Creek Detailed Study

--- Fourth Creek.g01 (geometry) --- (continued)

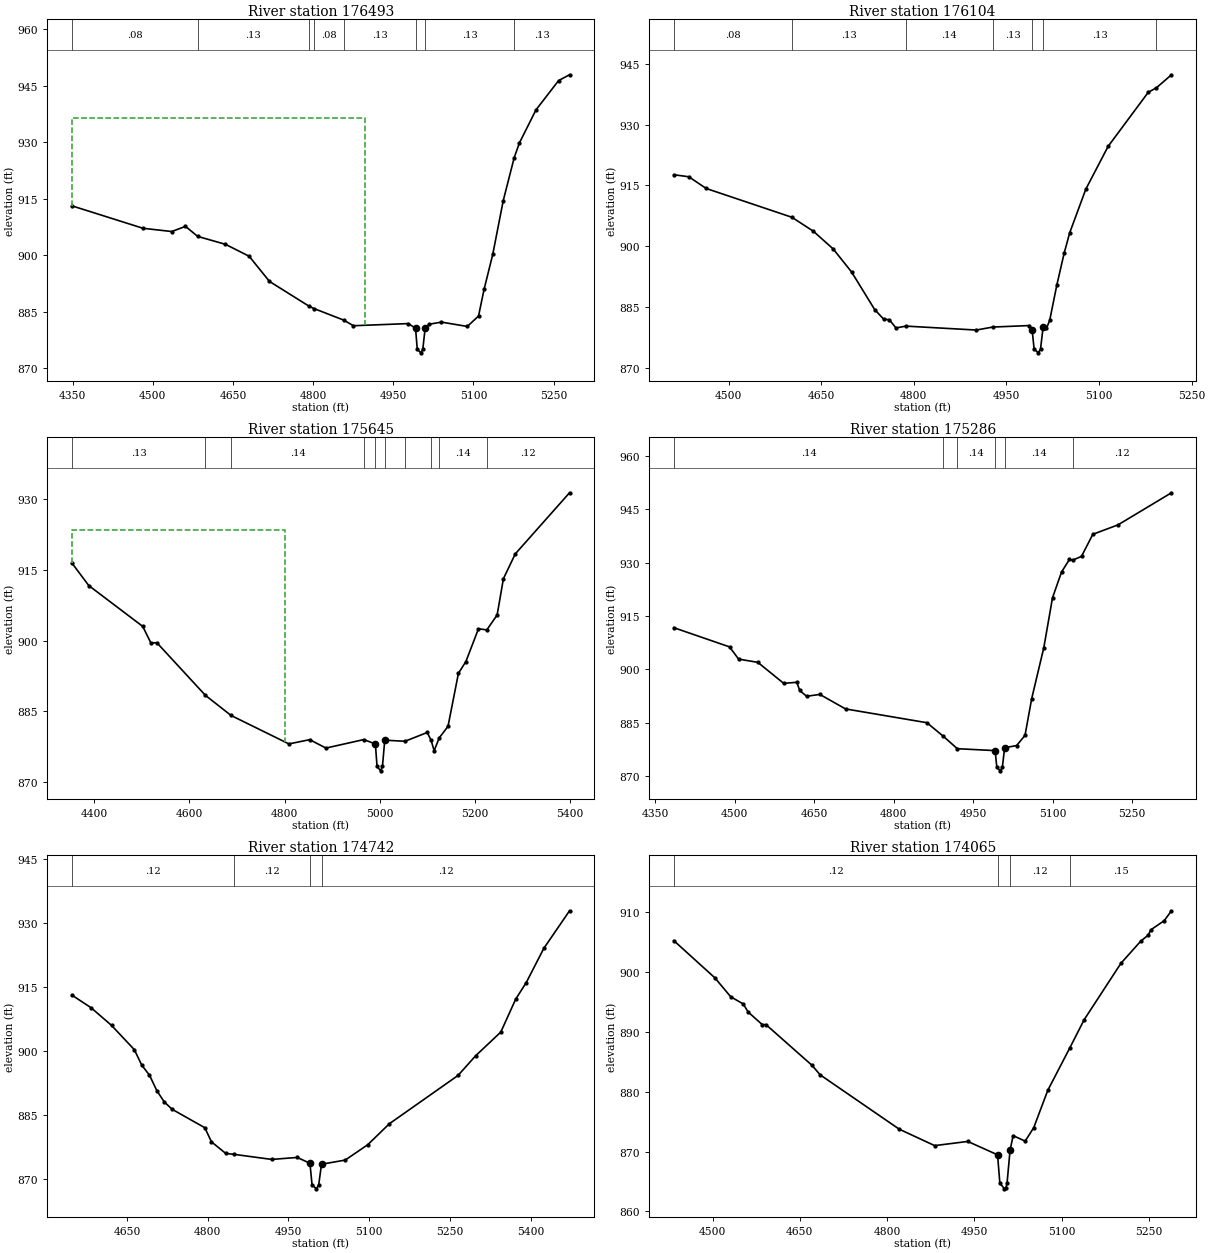
Type RM Length L Ch R = 1,176493,361,389,374
BEGIN DESCRIPTION:
Fourth Creek 296.0
END DESCRIPTION:
XS GIS Cut Line= 4
      1413526.13       769676.64      1413380.98       769200.16
      1413371.11       769047.18      1413384.14       768767.78
#Sta/Elev= 30
  4348.6  913.08  4481.7  907.11  4535.5  906.25  4561.2  907.62  4583.9  904.96
  4636.0  902.85  4680.3  899.68  4718.3  893.00  4792.1  886.44  4801.6  885.79
  4857.1  882.73  4875.4  881.23  4978.1  881.80  4991.6  880.56  4994.8  874.99
  5001.5  874.03  5005.2  874.98  5009.5  880.52  5017.6  881.64  5040.1  882.19
  5088.4  881.04  5109.4  883.79  5119.8  890.87  5136.1  900.22  5155.7  914.47
  5176.1  925.83  5185.8  929.74  5216.8  938.53  5259.3  946.35  5279.7  947.88
#Mann=8,-1,0
  4348.6    0.08       0  4583.9    0.13       0  4792.1    0.14       0
  4801.6    0.08       0  4857.1    0.13       0  4991.6   0.042       0
  5009.5    0.13       0  5176.1    0.13       0
#XS Ineff=2,0
    0.00 4897.40  936.51               0
Permanent Ineff=
       F       F
Bank Sta=4991.6,5009.5
XS Rating Curve= 0
Exp/Cntr=0.3,0.1

Type RM Length L Ch R = 1,176104,451,459,458
BEGIN DESCRIPTION:
Fourth Creek 295.0
END DESCRIPTION:
XS GIS Cut Line= 3
      1413699.72       769654.55      1413734.43       769064.47
      1413740.74       768849.86
#Sta/Elev= 30
  4411.4  917.63  4435.7  917.13  4463.8  914.24  4602.7  907.12  4637.5  903.66
  4669.5  899.30  4699.2  893.62  4736.6  884.34  4751.2  881.96  4760.5  881.81
  4771.1  879.79  4787.4  880.24  4901.2  879.27  4927.9  880.01  4987.3  880.38
  4991.6  879.33  4994.8  874.60  5001.5  873.64  5005.2  874.59  5009.5  880.13
  5014.8  879.68  5020.0  881.64  5031.6  890.40  5043.4  898.22  5052.4  903.28
  5078.6  914.09  5114.6  924.63  5179.7  938.01  5192.9  939.11  5217.2  942.32
#Mann=7,-1,0
  4411.4    0.08       0  4602.7    0.13       0  4787.4    0.14       0
  4927.9    0.13       0  4991.6   0.042       0  5009.5    0.13       0
  5192.9    0.12       0
Bank Sta=4991.6,5009.5
XS Rating Curve= 0
Exp/Cntr=0.3,0.1

Type RM Length L Ch R = 1,175645,361,359,361
BEGIN DESCRIPTION:
Fourth Creek 294.0
END DESCRIPTION:
XS GIS Cut Line= 4
      1414129.53       769739.78      1414186.33       769096.02
      1414195.80       769010.82      1414397.75       768771.01
#Sta/Elev= 30
  4353.2  916.43  4388.8  911.64  4502.1  903.00  4519.1  899.52  4531.9  899.53
  4633.8  888.40  4687.7  884.14  4809.2  878.12  4852.9  879.02  4887.0  877.24
  4966.5  879.04  4990.8  878.11  4994.3  873.38  5001.7  872.42  5005.7  873.37
  5010.5  878.91  5053.0  878.68  5099.8  880.54  5108.0  878.85  5114.3  876.68
  5125.0  879.40  5143.4  881.84  5165.3  893.07  5181.0  895.56  5207.4  902.50
  5224.9  902.26  5246.6  905.41  5259.8  913.10  5284.7  918.35  5398.7  931.29
#Mann=10,-1,0
  4353.2    0.13       0  4633.8    0.08       0  4687.7    0.14       0
  4966.5    0.08       0  4990.8   0.042       0  5010.5    0.08       0
  5053.0    0.14       0  5108.0    0.05       0  5125.0    0.14       0
  5224.9    0.12       0
#XS Ineff=2,0
    0.00 4801.90  923.51               0
Permanent Ineff=
       F       F
Bank Sta=4990.8,5010.5
XS Rating Curve= 0
Exp/Cntr=0.3,0.1

Type RM Length L Ch R = 1,175286,625,544,491
BEGIN DESCRIPTION:
Fourth Creek 293.0
END DESCRIPTION:
XS GIS Cut Line= 3
      1414476.66       769739.85      1414542.93       769127.58
      1414574.49       768805.67
#Sta/Elev= 30
  4385.1  911.70  4490.3  906.29  4507.4  902.86  4543.7  901.94  4592.5  896.04
  4617.4  896.33  4622.7  894.03  4635.8  892.40  4660.7  892.92  4709.2  888.84
  4862.8  884.96  4894.0  881.12  4920.2  877.65  4991.6  877.11  4994.8  872.38
  5001.5  871.42  5005.2  872.37  5009.5  877.91  5032.2  878.54  5048.0  881.41
  5060.6  891.74  5083.5  906.11  5099.9  920.12  5116.9  927.34  5131.9  930.92
  5137.9  930.69  5154.6  931.76  5176.0  937.97  5223.5  940.62  5324.4  949.65
#Mann=6,-1,0
  4385.1    0.14       0  4894.0    0.08       0  4920.2    0.14       0
  4991.6   0.042       0  5009.5    0.14       0  5137.9    0.12       0
Bank Sta=4991.6,5009.5
XS Rating Curve= 0
Exp/Cntr=0.3,0.1

Type RM Length L Ch R = 1,174742,628,677,653
BEGIN DESCRIPTION:
Fourth Creek 292.0
END DESCRIPTION:
XS GIS Cut Line= 4
      1415429.69       769398.97      1415013.14       769231.72
      1414869.24       769146.52      1414670.43       768909.84
#Sta/Elev= 30
  4547.3  913.13  4582.8  910.18  4621.0  906.03  4663.5  900.32  4677.2  896.70
  4691.6  894.35  4705.3  890.70  4719.1  888.07  4733.9  886.33  4794.5  882.02
  4806.8  878.72  4833.4  875.99  4848.2  875.79  4918.8  874.59  4966.3  875.05
  4989.9  873.69  4993.8  868.65  5001.8  867.69  5006.2  868.64  5011.4  873.46
  5055.4  874.43  5097.3  878.03  5137.7  882.97  5265.3  894.29  5297.9  898.89
  5344.7  904.45  5372.4  912.17  5392.1  916.08  5424.6  924.07  5472.5  932.90
#Mann=4,-1,0
  4547.3    0.12       0  4848.2    0.12       0  4989.9   0.042       0
  5011.4    0.12       0
Bank Sta=4989.9,5011.4
XS Rating Curve= 0
Exp/Cntr=0.3,0.1

Type RM Length L Ch R = 1,174065,448,552,500
BEGIN DESCRIPTION:
Fourth Creek 291.0
END DESCRIPTION:
XS GIS Cut Line= 4
      1415535.10       769082.14      1415339.45       768747.63
      1415197.44       768637.18      1414960.79       768473.10
#Sta/Elev= 30
  4433.4  905.29  4503.8  899.08  4531.2  895.90  4552.9  894.68  4561.1  893.35
  4585.4  891.24  4591.9  891.23  4671.0  884.42  4685.0  882.83  4820.9  873.74
  4881.8  870.99  4938.7  871.69  4989.9  869.45  4993.8  864.72  5001.8  863.76
  5004.4  863.96  5006.2  864.71  5011.4  870.25  5016.7  872.66  5037.3  871.74
  5052.1  874.00  5076.3  880.26  5114.4  887.40  5138.7  892.05  5202.0  901.50
  5236.3  905.23  5248.9  906.20  5253.3  907.09  5276.3  908.62  5288.8  910.28
#Mann=4,-1,0
  4433.4    0.12       0  4989.9   0.042       0  5011.4    0.12       0
  5114.4    0.15       0
Bank Sta=4989.9,5011.4
XS Rating Curve= 0
Exp/Cntr=0.3,0.1

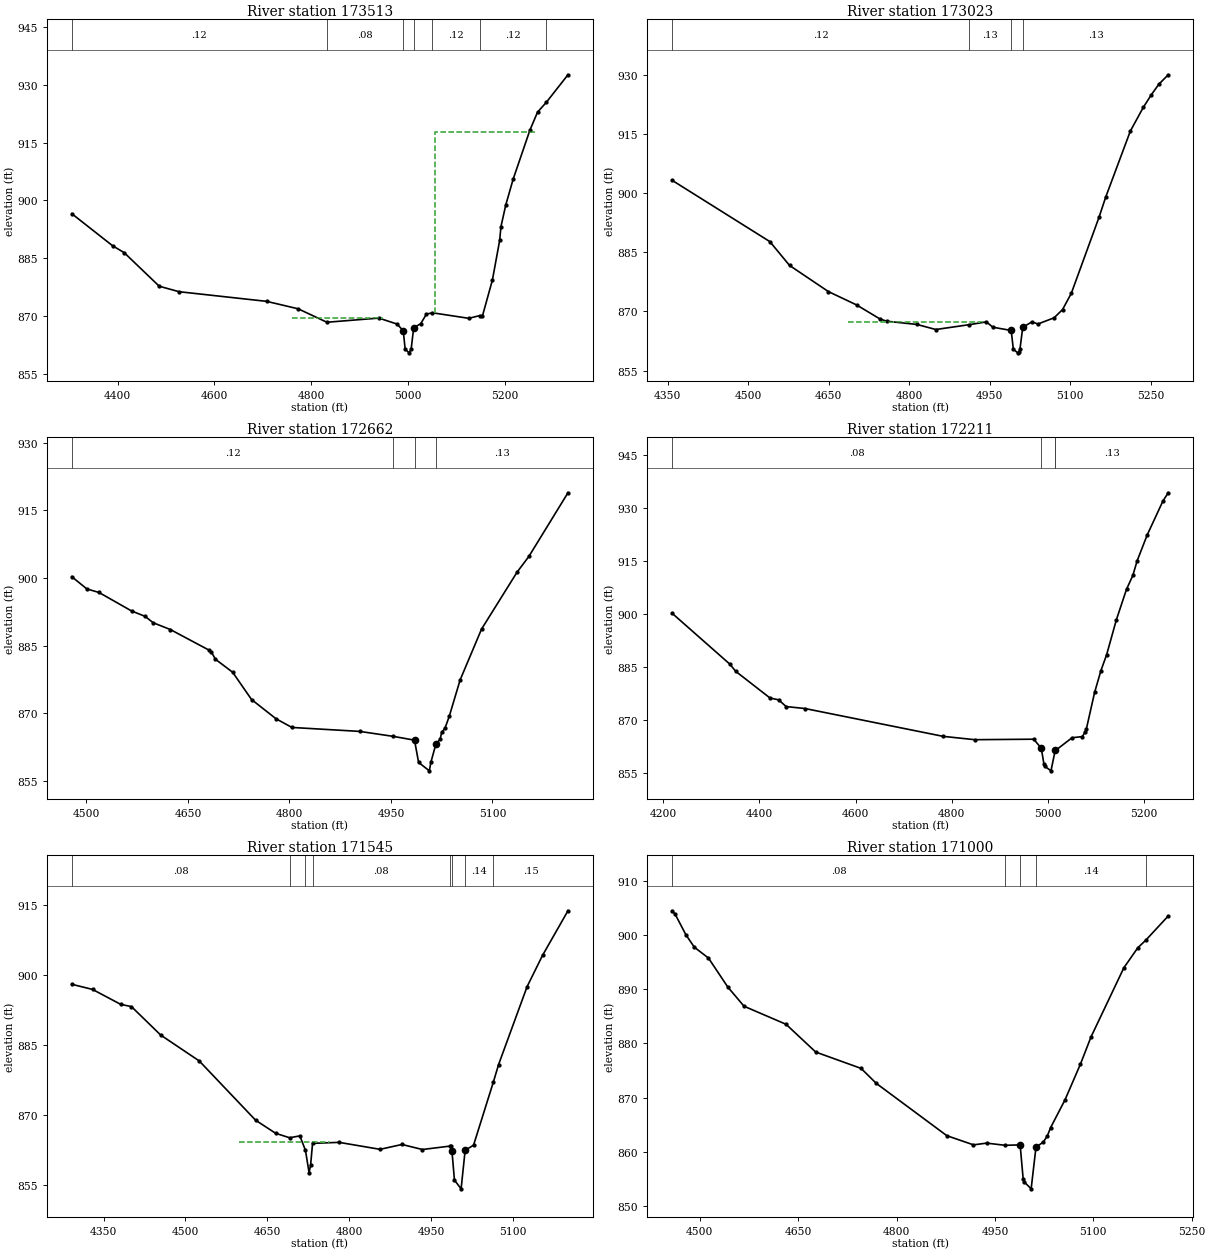
Type RM Length L Ch R = 1,173513,404,490,458
BEGIN DESCRIPTION:
Fourth Creek 290.0
END DESCRIPTION:
XS GIS Cut Line= 3
      1415882.24       768873.85      1415494.08       768286.89
      1415304.76       768028.15
#Sta/Elev= 30
  4305.6  896.58  4389.9  888.27  4413.8  886.49  4486.1  877.80  4527.0  876.38
  4707.9  873.88  4772.9  871.95  4832.3  868.47  4939.5  869.55  4977.4  867.99
  4989.9  866.24  4993.8  861.51  5001.8  860.55  5006.2  861.50  5011.4  867.04
  5026.0  868.11  5037.8  870.58  5050.2  870.92  5125.1  869.49  5148.2  870.20
  5153.2  870.02  5173.9  879.39  5188.9  889.65  5191.6  893.26  5201.6  898.87
  5216.7  905.50  5251.2  918.16  5267.1  922.87  5285.5  925.46  5329.9  932.55
#Mann=7,-1,0
  4305.6    0.12       0  4832.3    0.08       0  4989.9   0.042       0
  5011.4    0.08       0  5050.2    0.12       0  5148.2    0.12       0
  5285.5    0.15       0
#XS Ineff=2,-1
 4760.70 4945.50  869.54 5054.50 5265.30  917.79
Permanent Ineff=
       F       F
Bank Sta=4989.9,5011.4
XS Rating Curve= 0
Exp/Cntr=0.3,0.1

Type RM Length L Ch R = 1,173023,395,361,352
BEGIN DESCRIPTION:
Fourth Creek 289.0
END DESCRIPTION:
XS GIS Cut Line= 4
      1416033.71       768857.42      1415926.42       768466.14
      1415907.49       768229.45      1415916.95       767948.58
#Sta/Elev= 30
  4358.2  903.35  4540.3  887.77  4577.0  881.71  4649.4  875.06  4702.0  871.66
  4745.3  868.11  4758.1  867.52  4814.1  866.71  4849.5  865.42  4911.8  866.65
  4943.7  867.36  4955.7  866.00  4989.9  865.18  4993.8  860.45  5001.8  859.49
  5004.4  859.69  5006.2  860.44  5011.4  865.98  5028.6  867.38  5039.6  866.82
  5069.7  868.39  5085.6  870.50  5101.9  874.64  5153.5  893.96  5165.8  899.03
  5211.8  915.86  5235.9  921.88  5251.2  925.15  5265.0  927.79  5282.4  930.17
#Mann=4,-1,0
  4358.2    0.12       0  4911.8    0.13       0  4989.9   0.042       0
  5011.4    0.13       0
#XS Ineff=1,-1
 4686.10 4938.80  867.44
Permanent Ineff=
       F
Bank Sta=4989.9,5011.4
XS Rating Curve= 0
Exp/Cntr=0.3,0.1

Type RM Length L Ch R = 1,172662,442,451,440
BEGIN DESCRIPTION:
Fourth Creek 288.0
END DESCRIPTION:
XS GIS Cut Line= 3
      1416532.30       768601.80      1416257.77       768156.87
      1416153.63       767973.83
#Sta/Elev= 30
  4478.3  900.32  4500.5  897.61  4518.5  896.82  4566.8  892.71  4586.6  891.53
  4598.6  890.11  4623.9  888.61  4680.5  884.09  4684.7  883.59  4690.7  882.01
  4716.1  879.13  4744.0  873.09  4780.2  868.82  4803.7  866.90  4904.0  866.02
  4953.5  864.92  4984.9  864.08  4990.9  859.15  5006.8  857.28  5009.1  859.19
  5016.4  863.15  5022.8  864.32  5025.0  865.78  5029.9  866.71  5036.3  869.39
  5052.3  877.43  5084.0  888.71  5136.6  901.35  5153.9  904.80  5211.7  918.92
#Mann=4,-1,0
  4478.3    0.12       0  4953.5    0.13       0  4984.9   0.042       0
  5016.4    0.13       0
Bank Sta=4984.9,5016.4
XS Rating Curve= 0
Exp/Cntr=0.3,0.1

Type RM Length L Ch R = 1,172211,537,666,654
BEGIN DESCRIPTION:
Fourth Creek 287.0
END DESCRIPTION:
XS GIS Cut Line= 4
      1416611.86       768601.80      1416706.52       768046.42
      1416580.29       767869.70      1416419.34       767677.18
#Sta/Elev= 30
  4218.5  900.23  4338.5  885.81  4350.8  883.76  4422.2  876.19  4440.1  875.68
  4455.6  873.77  4494.7  873.22  4781.9  865.33  4847.6  864.38  4970.3  864.52
  4986.1  861.95  4991.6  857.42  4993.4  856.84  5006.2  855.55  5015.1  861.42
  5015.6  861.33  5050.0  864.93  5071.5  865.26  5077.0  866.56  5080.0  867.55
  5096.9  877.78  5110.1  883.99  5121.9  888.46  5142.1  898.35  5163.3  907.04
  5176.4  910.94  5185.3  915.08  5206.5  922.50  5239.2  932.11  5250.0  934.38
#Mann=4,-1,0
  4218.5    0.08       0  4986.1   0.042       0  5015.1    0.08       0
  5015.6    0.13       0
Bank Sta=4986.1,5015.1
XS Rating Curve= 0
Exp/Cntr=0.3,0.1

Type RM Length L Ch R = 1,171545,543,545,542
BEGIN DESCRIPTION:
Fourth Creek 286.0
END DESCRIPTION:
XS GIS Cut Line= 4
      1417277.73       768463.02      1417132.55       767920.19
      1417148.33       767775.02      1417195.66       767579.40
#Sta/Elev= 30
  4291.8  898.00  4329.8  896.90  4381.4  893.71  4401.2  893.22  4454.6  887.15
  4525.4  881.60  4628.6  868.93  4665.3  866.13  4691.0  865.17  4709.7  865.58
  4720.0  862.47  4726.6  857.73  4729.4  859.28  4733.0  863.98  4781.6  864.19
  4856.7  862.70  4896.9  863.74  4934.3  862.66  4984.7  863.39  4987.0  863.44
  4988.4  862.36  4993.0  856.12  5005.2  854.25  5012.6  862.49  5028.0  863.59
  5064.3  877.09  5073.9  880.84  5126.1  897.49  5154.4  904.18  5201.0  913.72
#Mann=8,-1,0
  4291.8    0.08       0  4691.0    0.14       0  4720.0    0.05       0
  4733.0    0.08       0  4984.7    0.14       0  4988.4   0.042       0
  5012.6    0.14       0  5064.3    0.15       0
#XS Ineff=1,-1
 4598.20 4762.50  864.31
Permanent Ineff=
       F
Bank Sta=4988.4,5012.6
XS Rating Curve= 0
Exp/Cntr=0.3,0.1

Type RM Length L Ch R = 1,171000,526,507,473
BEGIN DESCRIPTION:
Fourth Creek 285.0
END DESCRIPTION:
XS GIS Cut Line= 3
      1417672.19       768450.34      1417675.34       767853.92
      1417615.39       767705.61
#Sta/Elev= 30
  4457.8  904.50  4462.5  903.87  4478.9  900.06  4491.8  897.77  4513.3  895.77
  4542.7  890.43  4567.5  886.88  4631.5  883.55  4676.8  878.42  4746.0  875.40
  4769.1  872.64  4876.7  862.98  4917.3  861.29  4937.5  861.61  4965.3  861.21
  4988.4  861.28  4993.0  855.04  4994.5  854.46  5005.2  853.17  5012.6  860.89
  5023.7  861.79  5029.9  862.95  5034.9  864.48  5056.6  869.54  5080.4  876.21
  5096.5  881.22  5146.6  893.99  5167.8  897.67  5179.8  899.05  5214.2  903.54
#Mann=5,-1,0
  4457.8    0.08       0  4965.3    0.14       0  4988.4   0.042       0
  5012.6    0.14       0  5179.8    0.15       0
Bank Sta=4988.4,5012.6
XS Rating Curve= 0
Exp/Cntr=0.3,0.1

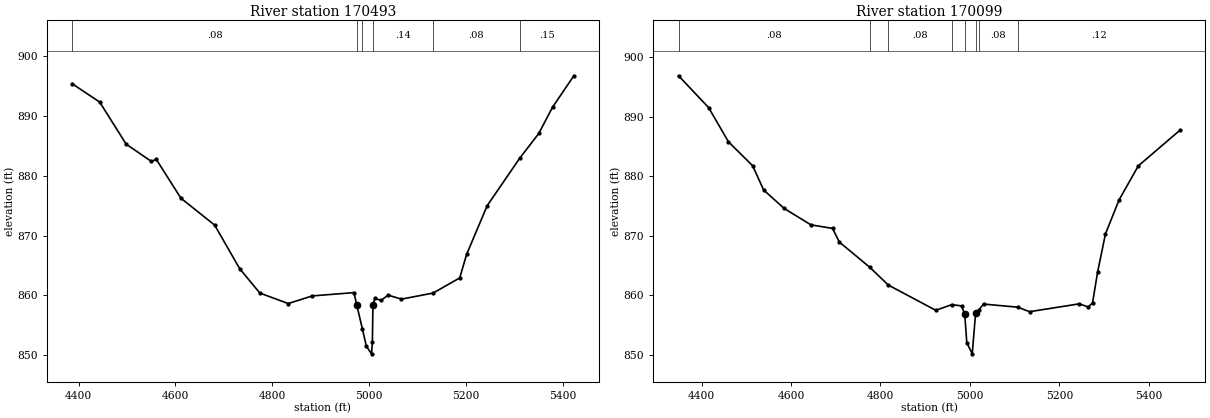
Type RM Length L Ch R = 1,170493,365,394,409
BEGIN DESCRIPTION:
Fourth Creek 284.0
END DESCRIPTION:
XS GIS Cut Line= 4
      1418448.50       768184.33      1418093.08       767684.39
      1417928.68       767514.35      1417760.54       767433.25
#Sta/Elev= 30
  4386.6  895.42  4443.7  892.34  4498.3  885.31  4550.5  882.41  4560.5  882.77
  4611.4  876.27  4681.2  871.76  4732.7  864.49  4774.5  860.40  4833.1  858.64
  4882.9  859.92  4968.9  860.47  4974.9  858.34  4986.3  854.41  4994.5  851.52
  5005.2  850.23  5007.0  852.14  5008.1  858.41  5012.0  859.49  5025.1  859.18
  5039.4  860.05  5067.0  859.38  5132.5  860.40  5187.4  862.93  5201.6  866.86
  5244.2  875.02  5311.1  882.92  5350.8  887.10  5379.2  891.49  5423.2  896.74
#Mann=6,-1,0
  4386.6    0.08       0  4974.9   0.042       0  4986.3    0.14       0
  5008.1    0.14       0  5132.5    0.08       0  5311.1    0.15       0
Bank Sta=4974.9,5008.1
XS Rating Curve= 0
Exp/Cntr=0.3,0.1

Type RM Length L Ch R = 1,170099,448,450,479
BEGIN DESCRIPTION:
Fourth Creek 283.0
END DESCRIPTION:
XS GIS Cut Line= 4
      1418495.84       768190.36      1418511.62       767713.80
      1418366.45       767338.27      1418214.99       767148.94
#Sta/Elev= 30
  4348.5  896.88  4415.7  891.54  4460.1  885.79  4514.3  881.76  4538.7  877.70
  4584.7  874.59  4644.5  871.84  4692.9  871.24  4708.0  868.95  4776.2  864.70
  4817.4  861.73  4923.7  857.48  4959.5  858.44  4981.3  858.22  4988.4  856.81
  4993.0  852.04  5005.2  850.17  5012.6  856.97  5019.6  857.53  5030.4  858.53
  5106.7  858.01  5133.3  857.25  5244.7  858.57  5264.7  858.04  5274.1  858.72
  5285.4  863.89  5303.0  870.31  5333.4  876.02  5376.5  881.75  5470.4  887.79
#Mann=8,-1,0
  4348.5    0.08       0  4776.2    0.14       0  4817.4    0.08       0
  4959.5    0.14       0  4988.4   0.042       0  5012.6    0.14       0
  5019.6    0.08       0  5106.7    0.12       0
Bank Sta=4988.4,5012.6
XS Rating Curve= 0
Exp/Cntr=0.3,0.1