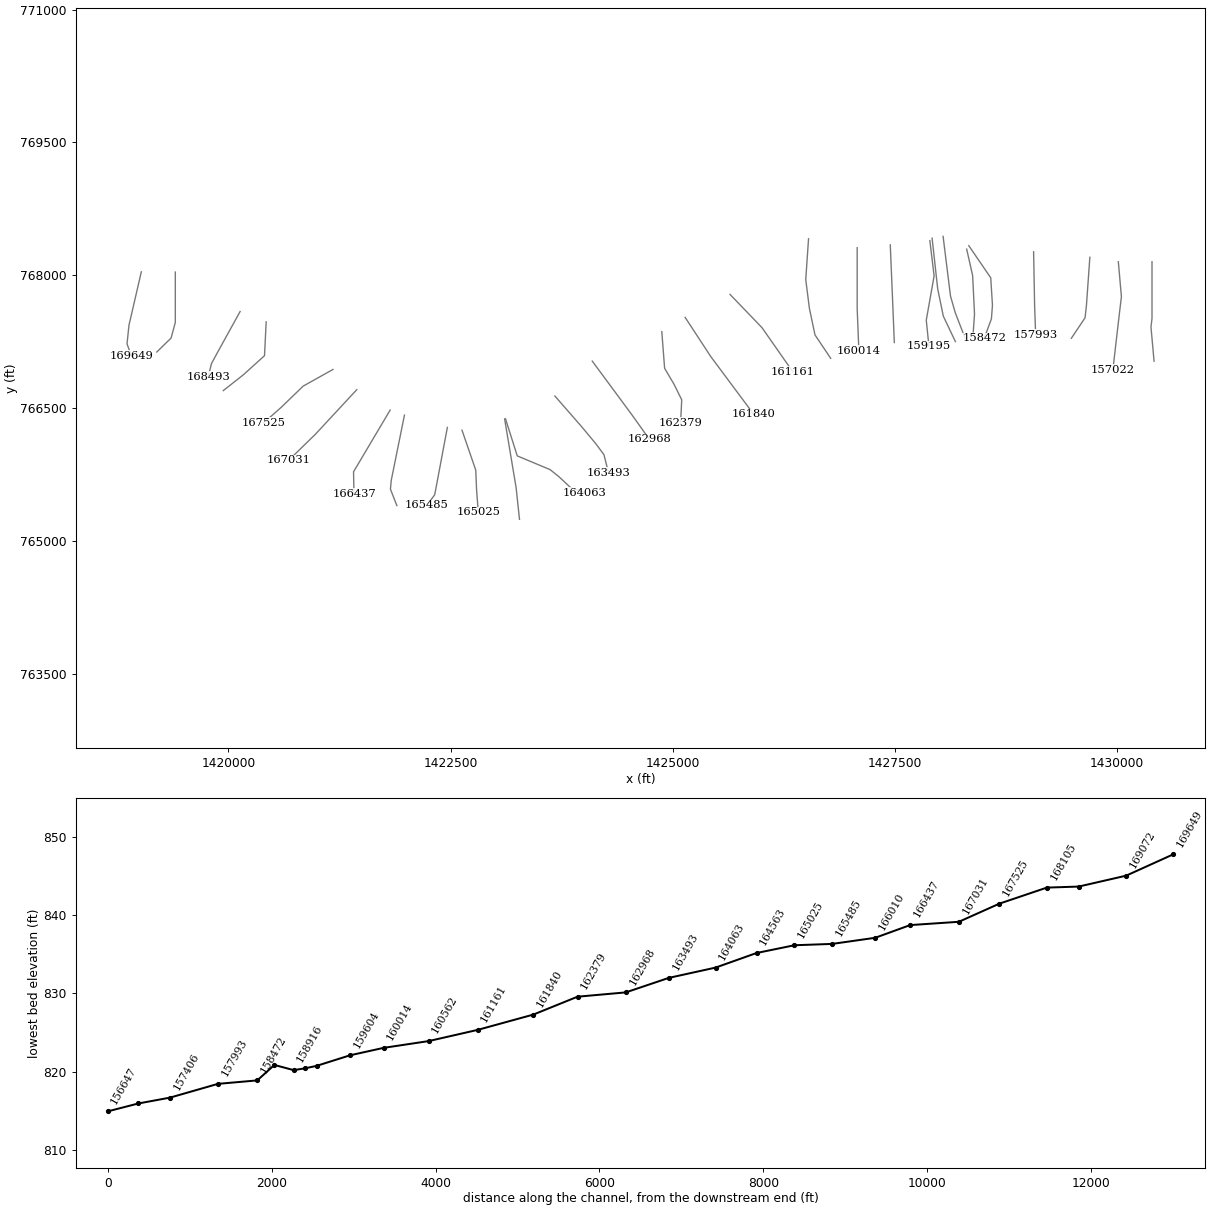
HEC-RAS study Fourth Creek.prj: Fourth Creek Detailed Study

--- Fourth Creek.g01 (geometry) --- (continued)

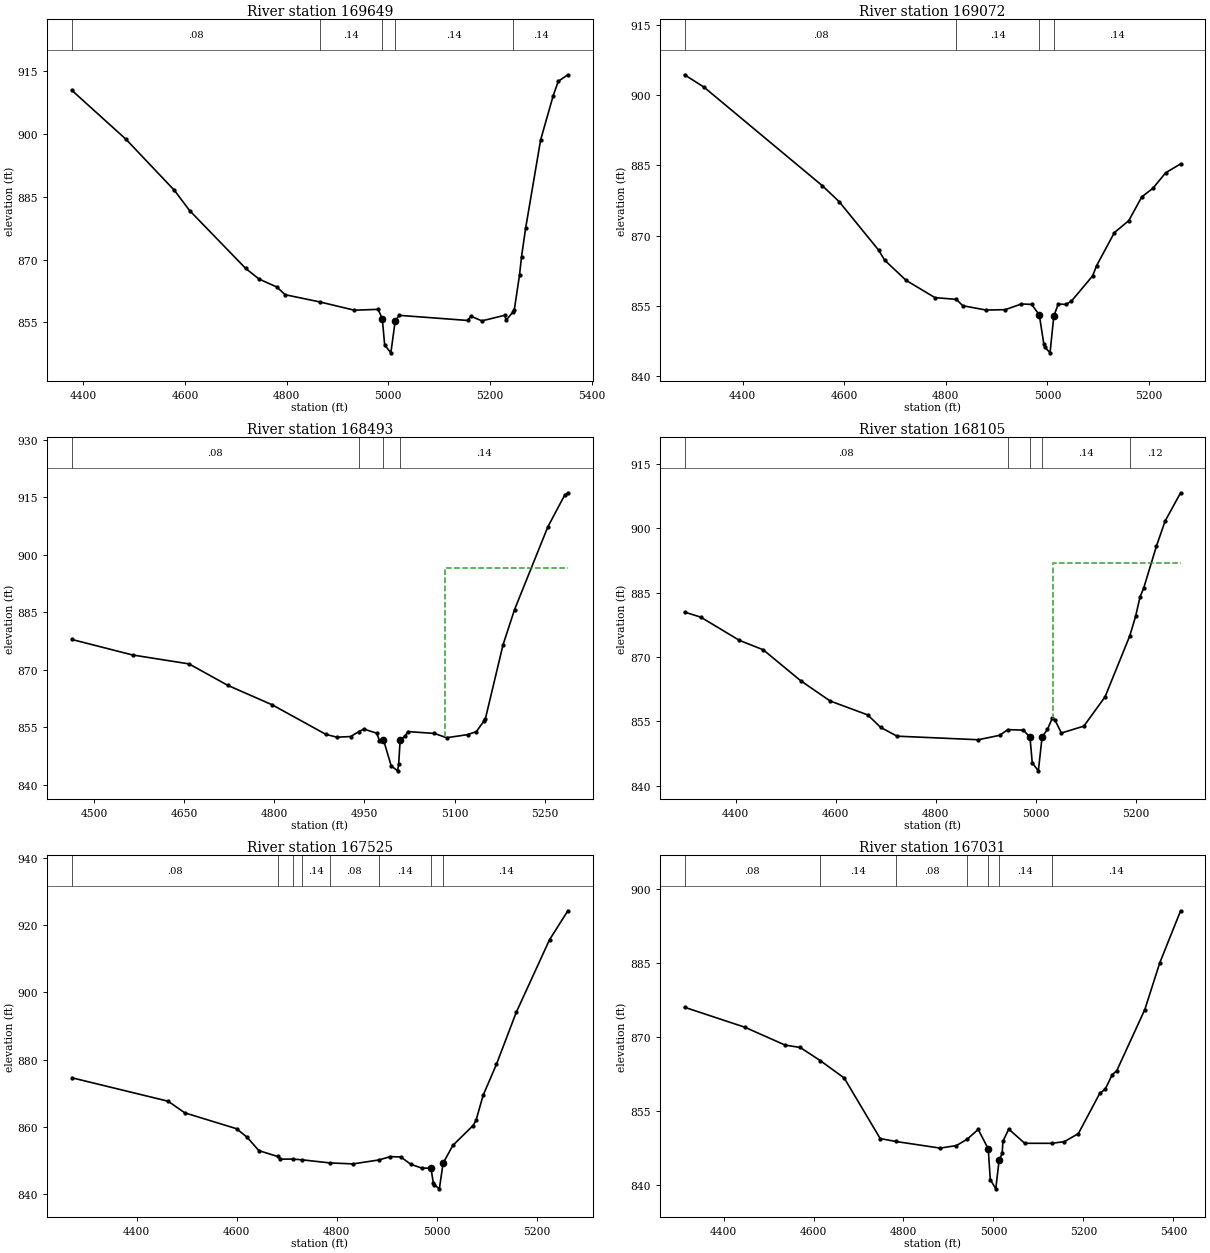
Type RM Length L Ch R = 1,169649,515,577,501
BEGIN DESCRIPTION:
Fourth Creek 282.0
END DESCRIPTION:
XS GIS Cut Line= 4
      1419019.70       768038.86      1418880.84       767436.09
      1418858.75       767224.66      1418909.23       767088.99
#Sta/Elev= 30
  4377.5  910.41  4484.1  898.72  4579.4  886.52  4609.3  881.70  4719.4  867.91
  4745.8  865.36  4780.7  863.46  4797.4  861.61  4865.5  859.89  4933.3  857.92
  4980.2  858.12  4988.4  855.85  4993.0  849.61  5005.2  847.74  5013.7  855.32
  5021.7  856.69  5156.1  855.47  5162.9  856.47  5184.2  855.37  5229.9  856.72
  5231.6  855.46  5245.7  857.54  5248.1  858.08  5258.4  866.38  5262.2  870.65
  5270.3  877.47  5299.8  898.55  5324.6  909.14  5334.5  912.54  5353.4  914.11
#Mann=5,-1,0
  4377.5    0.08       0  4865.5    0.14       0  4988.4   0.042       0
  5013.7    0.14       0  5245.7    0.14       0
Bank Sta=4988.4,5013.7
XS Rating Curve= 0
Exp/Cntr=0.3,0.1

Type RM Length L Ch R = 1,169072,567,579,546
BEGIN DESCRIPTION:
Fourth Creek 281.0
END DESCRIPTION:
XS GIS Cut Line= 4
      1419402.17       768035.72      1419402.17       767467.65
      1419354.84       767290.93      1419193.90       767133.15
#Sta/Elev= 30
  4285.8  904.34  4324.1  901.70  4556.7  880.70  4589.9  877.30  4668.2  866.87
  4679.6  864.80  4721.7  860.49  4778.7  856.79  4820.7  856.42  4833.4  855.07
  4879.1  854.14  4917.0  854.22  4948.8  855.43  4968.9  855.35  4984.0  853.12
  4993.0  846.88  4994.5  846.30  5005.2  845.01  5012.6  852.82  5021.3  855.42
  5036.3  855.34  5047.3  856.04  5089.0  861.43  5097.0  863.64  5131.9  870.68
  5160.0  873.19  5185.8  878.29  5207.7  880.12  5232.8  883.43  5262.2  885.33
#Mann=4,-1,0
  4285.8    0.08       0  4820.7    0.14       0  4984.0   0.042       0
  5012.6    0.14       0
Bank Sta=4984,5012.6
XS Rating Curve= 0
Exp/Cntr=0.3,0.1

Type RM Length L Ch R = 1,168493,409,388,369
BEGIN DESCRIPTION:
Fourth Creek 280.0
END DESCRIPTION:
XS GIS Cut Line= 4
      1420131.16       767590.11      1419872.20       767119.56
      1419809.27       767003.12      1419771.40       766851.64
#Sta/Elev= 30
  4462.9  877.91  4564.0  873.86  4658.0  871.53  4722.5  865.93  4796.2  860.87
  4885.8  853.14  4904.1  852.40  4927.0  852.57  4940.7  853.87  4948.9  854.52
  4970.5  853.44  4975.0  851.45  4981.6  851.73  4994.5  844.91  5005.2  843.62
  5007.0  845.53  5009.4  851.65  5017.7  852.72  5022.3  853.87  5066.5  853.38
  5086.7  852.26  5121.7  853.07  5136.4  853.87  5149.2  856.73  5151.3  857.25
  5180.7  876.56  5199.8  885.71  5255.2  907.30  5283.4  915.63  5288.5  916.19
#Mann=4,-1,0
  4462.9    0.08       0  4940.7    0.14       0  4981.6   0.042       0
  5009.4    0.14       0
#XS Ineff=2,0
       0                 5084.60    0.00  896.50
Permanent Ineff=
       F       F
Bank Sta=4981.6,5009.4
XS Rating Curve= 0
Exp/Cntr=0.3,0.1

Type RM Length L Ch R = 1,168105,564,580,574
BEGIN DESCRIPTION:
Fourth Creek 279.0
END DESCRIPTION:
XS GIS Cut Line= 4
      1420424.64       767473.29      1420405.71       767091.49
      1420169.02       766876.89      1419941.85       766697.05
#Sta/Elev= 30
  4298.0  880.49  4330.4  879.31  4407.6  873.90  4455.3  871.70  4529.9  864.51
  4589.0  859.77  4664.2  856.52  4690.0  853.61  4722.8  851.57  4885.1  850.74
  4927.9  851.77  4944.0  853.09  4975.1  852.98  4988.4  851.34  4993.0  845.36
  5005.2  843.49  5012.6  851.34  5023.3  853.14  5032.9  855.73  5038.6  855.28
  5051.2  852.30  5096.1  853.91  5138.5  860.74  5187.8  874.92  5199.6  879.51
  5208.4  884.03  5215.6  886.03  5241.0  895.79  5258.5  901.70  5289.5  908.29
#Mann=5,-1,0
  4298.0    0.08       0  4944.0    0.14       0  4988.4   0.042       0
  5012.6    0.14       0  5187.8    0.12       0
#XS Ineff=2,0
       0                 5034.60    0.00  891.84
Permanent Ineff=
       F       F
Bank Sta=4988.4,5012.6
XS Rating Curve= 0
Exp/Cntr=0.3,0.1

Type RM Length L Ch R = 1,167525,484,494,490
BEGIN DESCRIPTION:
Fourth Creek 278.0
END DESCRIPTION:
XS GIS Cut Line= 4
      1421175.70       766935.90      1420840.29       766747.50
      1420591.90       766506.72      1420396.23       766333.15
#Sta/Elev= 30
  4270.0  874.57  4462.7  867.57  4496.1  864.10  4599.5  859.37  4620.8  856.81
  4644.2  852.84  4681.5  851.10  4687.3  850.31  4712.5  850.31  4730.2  850.10
  4786.0  849.17  4832.4  848.88  4883.7  850.04  4907.3  851.05  4928.2  850.95
  4948.1  848.74  4969.6  847.66  4988.4  847.56  4993.0  843.31  4994.5  842.73
  5005.2  841.44  5012.6  849.07  5032.2  854.40  5072.7  860.33  5078.5  861.86
  5092.7  869.32  5119.3  878.56  5159.0  894.09  5225.5  915.72  5262.2  924.37
#Mann=8,-1,0
  4270.0    0.08       0  4681.5    0.14       0  4712.5    0.08       0
  4730.2    0.14       0  4786.0    0.08       0  4883.7    0.14       0
  4988.4   0.042       0  5012.6    0.14       0
Bank Sta=4988.4,5012.6
XS Rating Curve= 0
Exp/Cntr=0.3,0.1

Type RM Length L Ch R = 1,167031,574,594,608
BEGIN DESCRIPTION:
Fourth Creek 277.0 (Survey)
END DESCRIPTION:
XS GIS Cut Line= 3
      1421443.94       766707.74      1420976.90       766202.82
      1420680.24       765912.47
#Sta/Elev= 30
  4313.2  875.96  4447.3  871.91  4536.8  868.29  4570.4  867.80  4614.6  865.16
  4668.2  861.61  4748.2  849.33  4782.6  848.74  4881.5  847.39  4917.8  847.91
  4941.9  849.22  4966.1  851.18  4988.4  847.24  4993.0  841.00  5005.2  839.13
  5012.6  845.00  5019.4  846.30  5021.1  848.78  5034.0  851.25  5069.5  848.37
  5129.2  848.36  5157.5  848.70  5188.8  850.33  5236.5  858.53  5248.4  859.32
  5264.0  862.27  5274.2  863.10  5336.5  875.49  5369.8  884.98  5416.1  895.53
#Mann=7,-1,0
  4313.2    0.08       0  4614.6    0.14       0  4782.6    0.08       0
  4941.9    0.14       0  4988.4   0.042       0  5012.6    0.14       0
  5129.2    0.14       0
Bank Sta=4988.4,5012.6
XS Rating Curve= 0
Exp/Cntr=0.3,0.1

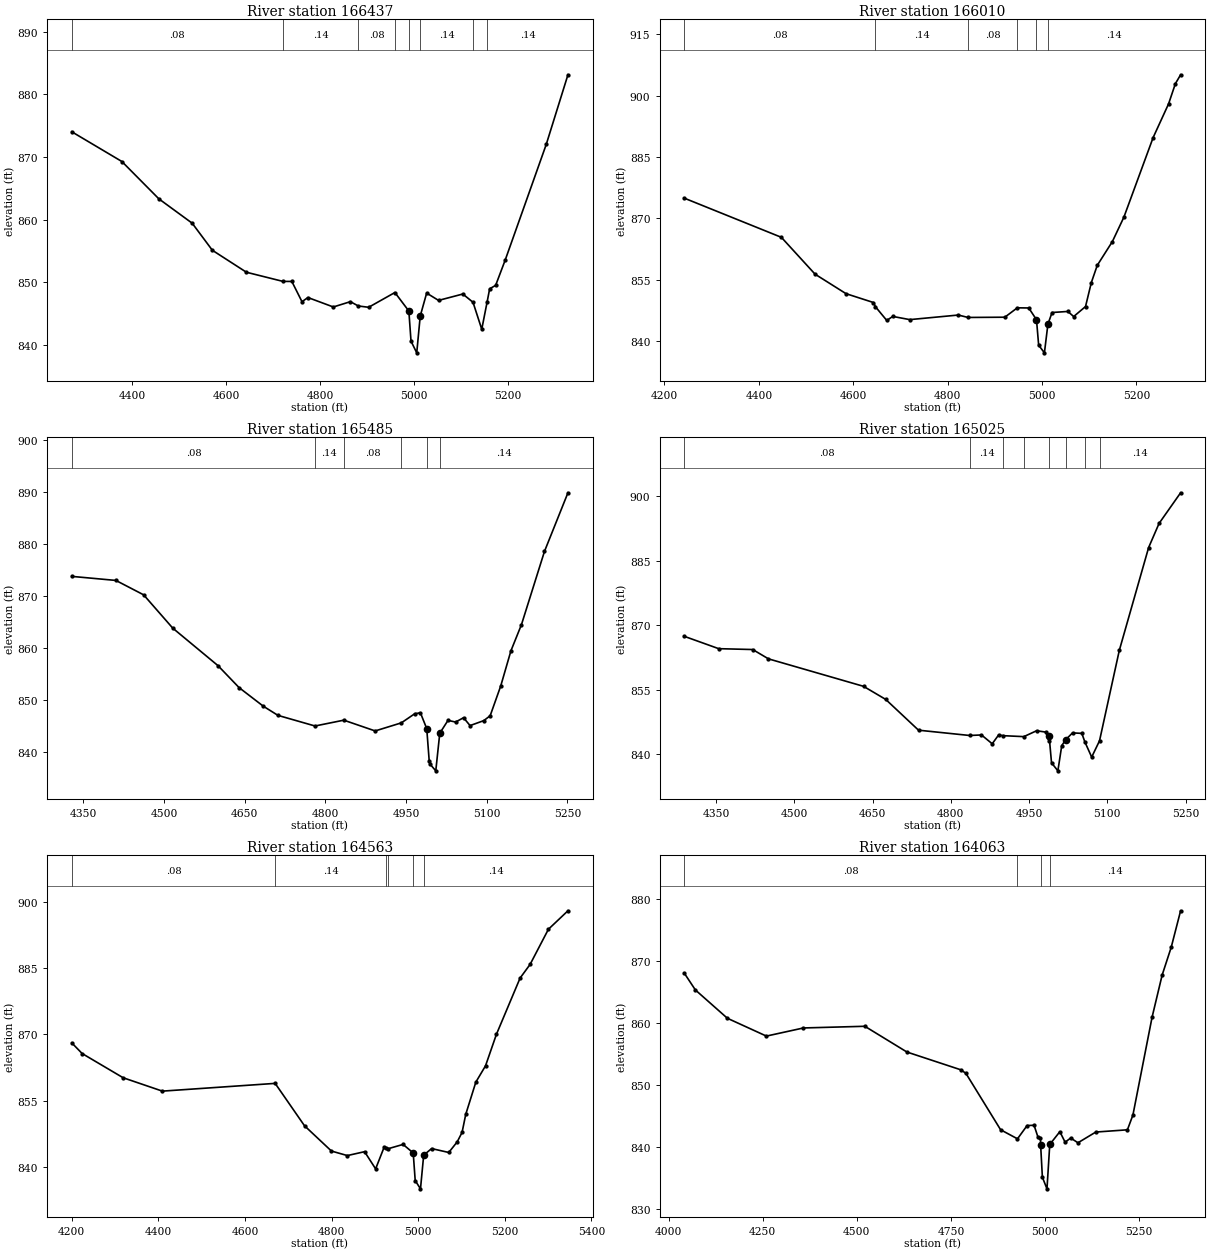
Type RM Length L Ch R = 1,166437,388,427,439
BEGIN DESCRIPTION:
Fourth Creek 276.0
END DESCRIPTION:
XS GIS Cut Line= 4
      1421819.46       766477.33      1421450.26       765852.53
      1421407.55       765780.96      1421412.39       765533.78
#Sta/Elev= 30
  4270.8  874.04  4377.4  869.29  4456.2  863.32  4527.1  859.43  4570.1  855.10
  4642.6  851.59  4720.3  850.13  4739.3  850.12  4760.9  846.88  4773.5  847.55
  4827.6  846.04  4864.0  846.89  4880.7  846.20  4902.8  845.99  4958.7  848.35
  4988.4  845.39  4993.0  840.58  5005.2  838.71  5012.6  844.58  5026.3  848.26
  5051.6  847.09  5103.3  848.11  5125.0  846.79  5143.6  842.48  5155.0  846.83
  5160.4  848.94  5173.2  849.50  5193.4  853.51  5280.9  872.02  5327.1  883.15
#Mann=8,-1,0
  4270.8    0.08       0  4720.3    0.14       0  4880.7    0.08       0
  4958.7    0.14       0  4988.4   0.042       0  5012.6    0.14       0
  5125.0    0.05       0  5155.0    0.14       0
Bank Sta=4988.4,5012.6
XS Rating Curve= 0
Exp/Cntr=0.3,0.1

Type RM Length L Ch R = 1,166010,512,525,515
BEGIN DESCRIPTION:
Fourth Creek 275.0
END DESCRIPTION:
XS GIS Cut Line= 4
      1421980.43       766420.58      1421832.11       765685.28
      1421822.64       765584.29      1421895.23       765398.08
#Sta/Elev= 30
  4242.4  874.93  4447.8  865.36  4519.2  856.34  4584.8  851.57  4643.0  849.40
  4647.1  848.38  4671.1  845.02  4683.8  846.00  4719.9  845.22  4822.6  846.34
  4843.4  845.75  4921.3  845.81  4947.8  848.11  4972.0  848.07  4988.4  845.20
  4993.0  838.96  5005.2  837.09  5012.6  844.10  5021.4  846.96  5054.9  847.22
  5067.2  845.97  5092.3  848.42  5104.6  854.28  5117.2  858.51  5149.2  864.32
  5173.6  870.29  5235.6  889.78  5268.3  898.02  5282.7  902.96  5293.8  905.14
#Mann=6,-1,0
  4242.4    0.08       0  4647.1    0.14       0  4843.4    0.08       0
  4947.8    0.14       0  4988.4   0.042       0  5012.6    0.14       0
Bank Sta=4988.4,5012.6
XS Rating Curve= 0
Exp/Cntr=0.3,0.1

Type RM Length L Ch R = 1,165485,435,460,470
BEGIN DESCRIPTION:
Fourth Creek 274.0
END DESCRIPTION:
XS GIS Cut Line= 4
      1422463.26       766281.73      1422341.49       765630.84
      1422320.20       765520.17      1422232.89       765401.26
#Sta/Elev= 30
  4328.5  873.69  4410.5  872.91  4462.1  870.14  4516.2  863.74  4600.3  856.53
  4639.5  852.31  4684.6  848.73  4711.8  846.97  4780.7  844.93  4834.2  846.05
  4892.5  843.98  4941.1  845.53  4966.0  847.28  4976.6  847.47  4988.4  844.42
  4993.0  838.18  4994.5  837.60  5005.2  836.31  5012.6  843.53  5027.9  846.01
  5042.0  845.69  5056.8  846.52  5068.9  845.01  5094.4  845.96  5106.3  846.90
  5125.9  852.61  5144.9  859.38  5164.5  864.42  5207.3  878.50  5250.9  889.76
#Mann=6,-1,0
  4328.5    0.08       0  4780.7    0.14       0  4834.2    0.08       0
  4941.1    0.14       0  4988.4   0.042       0  5012.6    0.14       0
Bank Sta=4988.4,5012.6
XS Rating Curve= 0
Exp/Cntr=0.3,0.1

Type RM Length L Ch R = 1,165025,440,462,452
BEGIN DESCRIPTION:
Fourth Creek 273.0
END DESCRIPTION:
XS GIS Cut Line= 4
      1422628.01       766250.12      1422782.62       765798.89
      1422792.09       765574.83      1422811.03       765325.49
#Sta/Elev= 30
  4289.2  867.43  4354.9  864.57  4420.1  864.37  4450.3  862.20  4632.5  855.81
  4675.1  852.76  4738.0  845.60  4835.9  844.37  4858.7  844.49  4879.3  842.44
  4891.5  844.48  4900.7  844.32  4939.9  844.10  4964.4  845.47  4982.3  845.15
  4987.9  843.10  4988.4  844.25  4993.0  838.01  5005.2  836.14  5012.6  842.01
  5020.3  843.41  5033.3  844.97  5051.1  844.86  5057.0  842.85  5070.0  839.34
  5085.0  843.12  5123.0  864.19  5179.2  888.11  5199.2  893.72  5240.5  900.85
#Mann=8,-1,0
  4289.2    0.08       0  4835.9    0.14       0  4900.7    0.08       0
  4939.9    0.14       0  4988.4   0.042       0  5020.3    0.14       0
  5057.0    0.05       0  5085.0    0.14       0
Bank Sta=4988.4,5020.3
XS Rating Curve= 0
Exp/Cntr=0.3,0.1

Type RM Length L Ch R = 1,164563,473,500,544
BEGIN DESCRIPTION:
Fourth Creek 272.0
END DESCRIPTION:
XS GIS Cut Line= 3
      1423107.66       766376.41      1423237.05       765600.07
      1423274.93       765243.43
#Sta/Elev= 30
  4200.0  868.10  4223.9  865.70  4318.6  860.23  4409.2  857.21  4669.6  858.96
  4737.4  849.39  4799.6  843.68  4836.3  842.66  4876.1  843.54  4901.6  839.66
  4921.5  844.61  4926.4  844.31  4929.9  844.19  4965.0  845.18  4988.4  843.26
  4993.0  837.02  5005.2  835.15  5012.6  842.76  5030.9  844.24  5070.5  843.36
  5090.0  845.76  5101.2  847.89  5109.8  852.00  5133.0  859.24  5155.4  862.93
  5180.6  870.05  5235.2  882.74  5258.3  885.82  5300.6  893.76  5345.7  897.93
#Mann=6,-1,0
  4200.0    0.08       0  4669.6    0.14       0  4926.4    0.08       0
  4929.9    0.14       0  4988.4   0.042       0  5012.6    0.14       0
Bank Sta=4988.4,5012.6
XS Rating Curve= 0
Exp/Cntr=0.3,0.1

Type RM Length L Ch R = 1,164063,585,570,558
BEGIN DESCRIPTION:
Fourth Creek 271.0
END DESCRIPTION:
XS GIS Cut Line= 6
      1423117.15       766379.50      1423249.68       765959.83
      1423618.90       765805.20      1423716.73       765726.30
      1423852.43       765600.07      1424010.25       765546.41
#Sta/Elev= 30
  4042.1  868.00  4071.2  865.33  4156.2  860.77  4259.8  857.90  4358.2  859.21
  4521.3  859.48  4633.2  855.33  4776.7  852.46  4789.9  851.89  4882.0  842.81
  4926.8  841.35  4952.5  843.49  4970.9  843.53  4980.8  841.71  4987.8  841.47
  4988.4  840.28  4993.0  835.16  5005.2  833.29  5012.6  840.44  5039.4  842.50
  5053.4  840.80  5068.2  841.48  5087.5  840.71  5134.9  842.44  5218.9  842.80
  5233.5  845.18  5284.4  860.94  5311.1  867.72  5335.3  872.22  5360.2  878.09
#Mann=4,-1,0
  4042.1    0.08       0  4926.8    0.14       0  4988.4   0.042       0
  5012.6    0.14       0
Bank Sta=4988.4,5012.6
XS Rating Curve= 0
Exp/Cntr=0.3,0.1

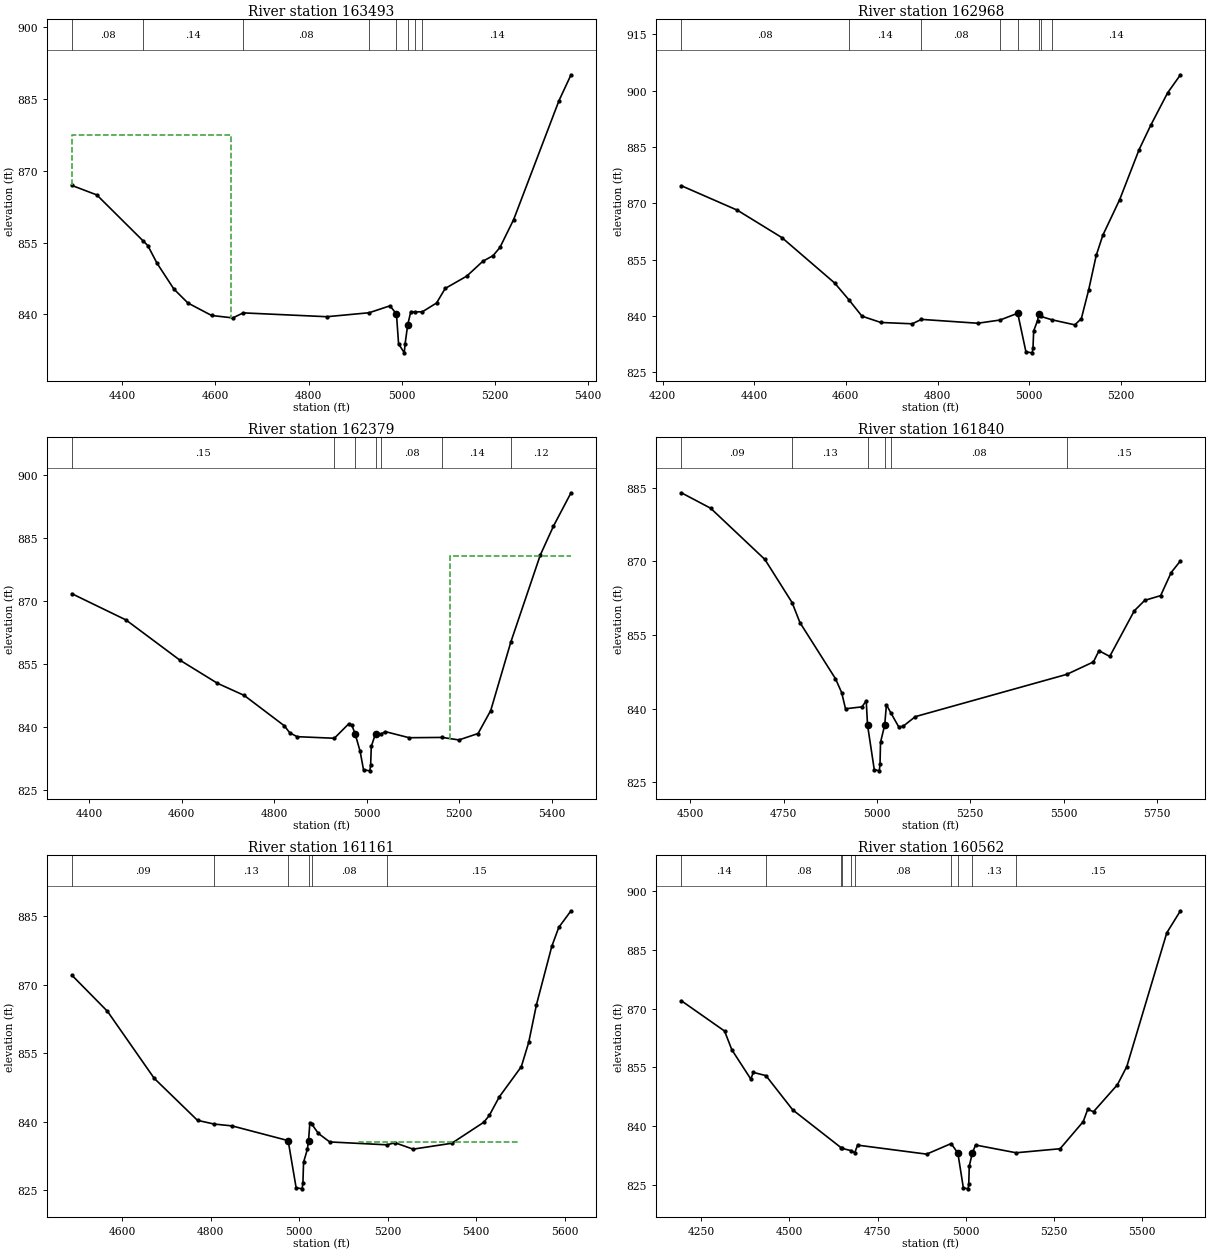
Type RM Length L Ch R = 1,163493,530,525,520
BEGIN DESCRIPTION:
Fourth Creek 270.0
END DESCRIPTION:
XS GIS Cut Line= 5
      1423673.19       766635.78      1423969.82       766294.97
      1424133.52       766097.79      1424225.44       765973.08
      1424275.93       765771.12
#Sta/Elev= 30
  4291.9  866.96  4345.3  864.98  4444.4  855.40  4454.7  854.40  4474.5  850.71
  4510.8  845.30  4540.9  842.39  4591.6  839.79  4637.2  839.28  4659.5  840.33
  4839.1  839.53  4929.8  840.36  4974.6  841.81  4988.4  840.09  4993.0  833.85
  5005.2  831.98  5007.0  833.89  5012.6  837.85  5019.2  840.58  5028.9  840.53
  5044.1  840.56  5074.5  842.40  5093.1  845.44  5139.3  848.01  5173.7  851.11
  5195.8  852.29  5210.5  854.00  5240.0  859.84  5337.3  884.70  5363.1  890.09
#Mann=8,-1,0
  4291.9    0.08       0  4444.4    0.14       0  4659.5    0.08       0
  4929.8    0.14       0  4988.4   0.042       0  5012.6    0.14       0
  5028.9    0.08       0  5044.1    0.14       0
#XS Ineff=2,0
    0.00 4632.30  877.57               0
Permanent Ineff=
       F       F
Bank Sta=4988.4,5012.6
XS Rating Curve= 0
Exp/Cntr=0.3,0.1

Type RM Length L Ch R = 1,162968,596,589,573
BEGIN DESCRIPTION:
Fourth Creek 269.0
END DESCRIPTION:
XS GIS Cut Line= 3
      1424093.51       767030.28      1424541.64       766421.20
      1424734.14       766149.81
#Sta/Elev= 30
  4241.1  874.68  4363.2  868.16  4460.5  860.85  4575.5  848.75  4606.6  844.27
  4635.1  839.91  4676.1  838.23  4744.9  837.87  4764.7  839.05  4887.8  838.02
  4936.5  838.88  4974.9  840.69  4992.9  830.38  5006.5  830.13  5008.3  831.49
  5009.7  835.95  5018.2  838.75  5020.9  840.46  5025.7  839.83  5048.9  838.96
  5099.5  837.59  5113.7  839.23  5129.6  846.84  5146.2  856.10  5160.6  861.48
  5197.4  870.98  5239.8  884.32  5265.1  890.79  5302.0  899.45  5330.0  904.26
#Mann=8,-1,0
  4241.1    0.08       0  4606.6    0.14       0  4764.7    0.08       0
  4936.5    0.14       0  4974.9   0.042       0  5020.9    0.14       0
  5025.7    0.08       0  5048.9    0.14       0
Bank Sta=4974.9,5020.9
XS Rating Curve= 0
Exp/Cntr=0.3,0.1

Type RM Length L Ch R = 1,162379,519,539,544
BEGIN DESCRIPTION:
Fourth Creek 268.0
END DESCRIPTION:
XS GIS Cut Line= 5
      1424876.15       767362.92      1424907.71       766949.48
      1425015.01       766766.44      1425100.21       766592.88
      1425087.59       766334.15
#Sta/Elev= 30
  4362.4  871.77  4479.2  865.53  4595.7  855.96  4677.0  850.44  4734.9  847.55
  4821.7  840.31  4833.5  838.63  4849.3  837.72  4929.8  837.34  4961.1  840.80
  4967.5  840.52  4974.9  838.33  4985.5  834.25  4992.9  829.83  5006.5  829.58
  5008.3  830.94  5009.7  835.40  5018.2  838.20  5020.9  838.33  5029.9  838.32
  5040.3  838.91  5091.6  837.47  5163.2  837.54  5199.1  836.94  5240.6  838.47
  5267.9  843.93  5311.6  860.32  5375.2  881.00  5403.7  887.89  5441.6  895.82
#Mann=7,-1,0
  4362.4    0.15       0  4929.8    0.13       0  4974.9   0.042       0
  5020.9    0.13       0  5029.9    0.08       0  5163.2    0.14       0
  5311.6    0.12       0
#XS Ineff=2,0
       0                 5180.60    0.00  880.80
Permanent Ineff=
       F       F
Bank Sta=4974.9,5020.9
XS Rating Curve= 0
Exp/Cntr=0.3,0.1

Type RM Length L Ch R = 1,161840,669,679,674
BEGIN DESCRIPTION:
Fourth Creek 266.0
END DESCRIPTION:
XS GIS Cut Line= 3
      1425138.70       767523.85      1425429.04       767078.86
      1425908.73       766431.92
#Sta/Elev= 30
  4476.3  883.97  4554.7  880.82  4700.0  870.38  4772.8  861.60  4793.9  857.51
  4889.1  846.07  4905.7  843.23  4915.9  839.95  4960.0  840.34  4971.4  841.57
  4974.9  836.64  4992.9  827.55  5006.5  827.30  5008.3  828.66  5009.7  833.12
  5020.9  836.64  5025.5  840.76  5038.1  839.01  5058.2  836.29  5069.4  836.34
  5103.0  838.35  5508.8  846.97  5579.9  849.50  5594.8  851.78  5623.6  850.62
  5689.4  859.92  5717.4  862.05  5759.9  863.01  5788.2  867.72  5813.0  870.10
#Mann=6,-1,0
  4476.3    0.09       0  4772.8    0.13       0  4974.9   0.042       0
  5020.9    0.13       0  5038.1    0.08       0  5508.8    0.15       0
Bank Sta=4974.9,5020.9
XS Rating Curve= 0
Exp/Cntr=0.3,0.1

Type RM Length L Ch R = 1,161161,635,599,540
BEGIN DESCRIPTION:
Fourth Creek 265.0
END DESCRIPTION:
XS GIS Cut Line= 3
      1425643.65       767783.53      1426003.39       767408.01
      1426350.54       766909.38
#Sta/Elev= 30
  4486.4  872.12  4566.7  864.22  4672.3  849.55  4770.1  840.35  4807.4  839.54
  4848.3  839.13  4974.9  835.91  4992.9  825.60  5006.5  825.35  5008.3  826.71
  5009.7  831.17  5018.2  833.97  5020.9  835.83  5024.0  839.85  5027.7  839.60
  5043.2  837.48  5068.8  835.62  5198.2  834.99  5216.3  835.44  5257.1  834.04
  5344.6  835.33  5416.9  839.93  5429.3  841.41  5451.8  845.47  5501.7  852.10
  5518.4  857.43  5535.9  865.67  5570.5  878.44  5586.3  882.60  5614.0  886.24
#Mann=6,-1,0
  4486.4    0.09       0  4807.4    0.13       0  4974.9   0.042       0
  5020.9    0.13       0  5027.7    0.08       0  5198.2    0.15       0
#XS Ineff=1,-1
 5133.90 5495.40  835.66
Permanent Ineff=
       F
Bank Sta=4974.9,5020.9
XS Rating Curve= 0
Exp/Cntr=0.3,0.1

Type RM Length L Ch R = 1,160562,550,548,522
BEGIN DESCRIPTION:
Fourth Creek 264.0
END DESCRIPTION:
XS GIS Cut Line= 5
      1426527.25       768411.87      1426495.69       767951.11
      1426536.72       767626.07      1426599.83       767326.27
      1426776.54       767061.21
#Sta/Elev= 30
  4193.8  871.99  4316.2  864.25  4336.9  859.45  4390.5  851.99  4397.8  853.68
  4433.4  852.86  4509.4  844.10  4647.1  834.39  4648.3  834.28  4675.0  833.68
  4685.0  833.13  4693.2  835.09  4888.9  832.79  4958.3  835.49  4977.4  833.05
  4992.9  824.17  5006.5  823.92  5008.3  825.28  5009.7  829.74  5018.3  833.05
  5027.5  835.12  5142.4  833.14  5267.1  834.17  5332.7  841.11  5345.3  844.22
  5361.9  843.64  5429.5  850.53  5456.1  855.17  5569.5  889.37  5608.2  894.99
#Mann=10,-1,0
  4193.8    0.14       0  4433.4    0.08       0  4647.1    0.14       0
  4648.3    0.08       0  4675.0    0.05       0  4685.0    0.08       0
  4958.3    0.13       0  4977.4   0.042       0  5018.3    0.13       0
  5142.4    0.15       0
#XS Ineff=2,-1
 4629.20 4936.60  833.86 5063.40 5286.50  834.17
Permanent Ineff=
       F       F
Bank Sta=4977.4,5018.3
XS Rating Curve= 0
Exp/Cntr=0.3,0.1

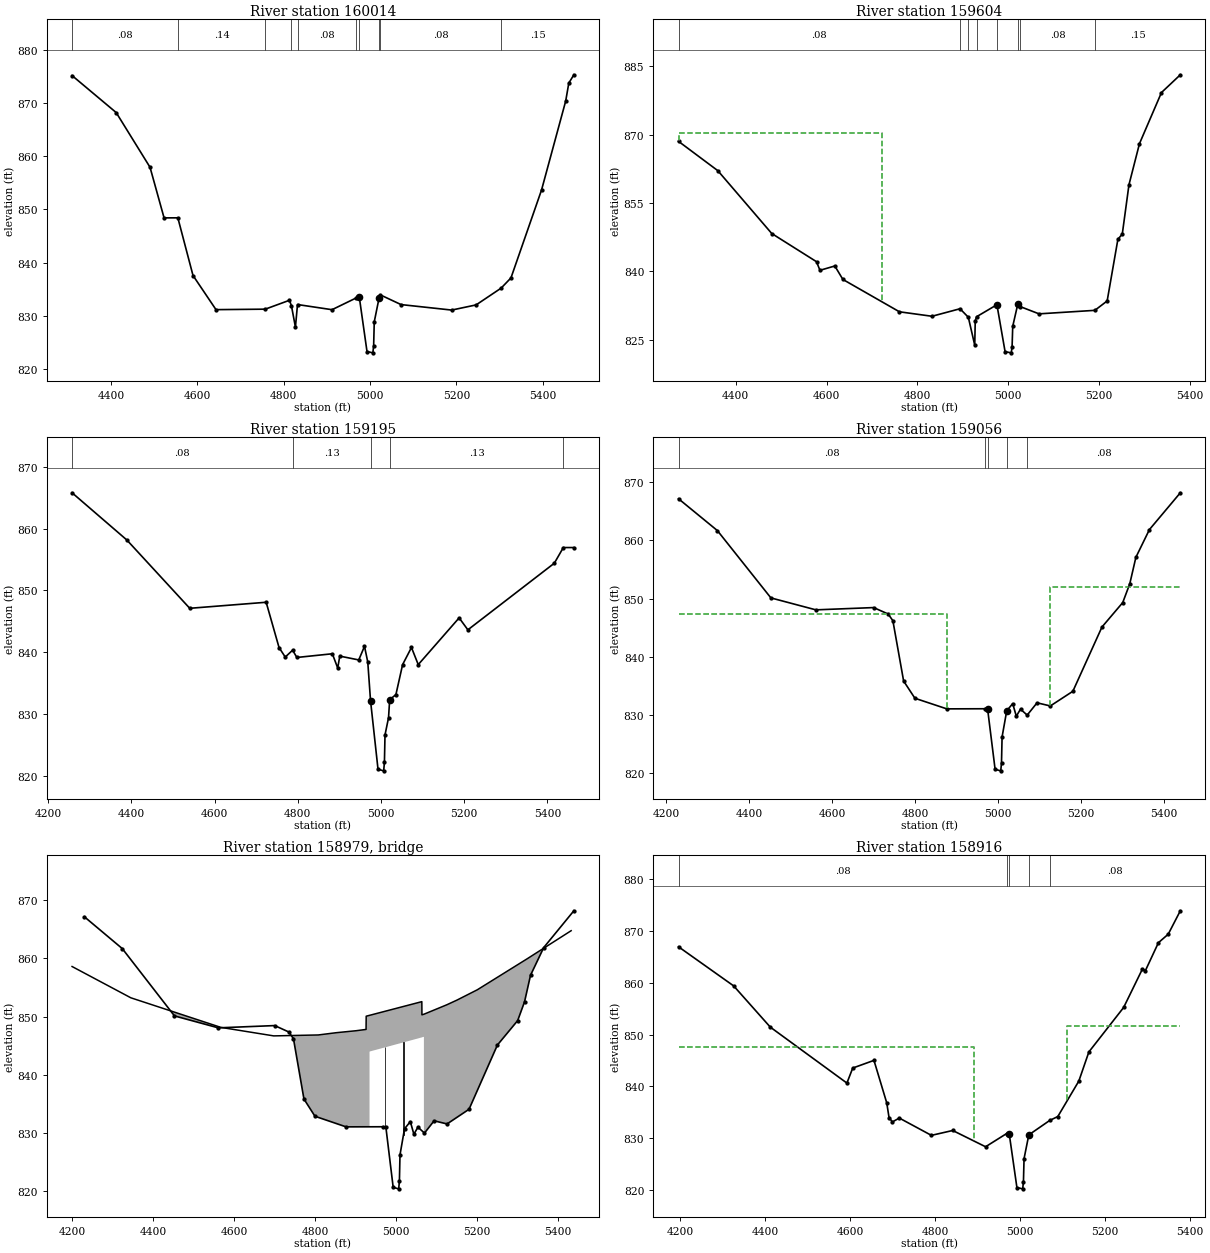
Type RM Length L Ch R = 1,160014,398,410,402
BEGIN DESCRIPTION:
Fourth Creek 263.0
END DESCRIPTION:
XS GIS Cut Line= 3
      1427074.46       768310.84      1427074.46       767622.92
      1427093.39       767149.52
#Sta/Elev= 30
  4310.1  875.12  4412.2  868.18  4490.6  857.90  4523.1  848.40  4555.0  848.41
  4590.1  837.58  4643.3  831.17  4757.3  831.26  4813.4  832.93  4818.0  831.88
  4827.2  827.89  4832.0  832.13  4911.9  831.16  4967.7  833.36  4974.9  833.62
  4992.9  823.31  5006.5  823.06  5008.3  824.42  5009.7  828.88  5020.9  833.38
  5023.8  833.94  5071.7  832.12  5189.0  831.09  5245.5  832.06  5303.4  835.21
  5326.2  837.13  5397.0  853.64  5452.9  870.34  5460.1  873.71  5471.8  875.27
#Mann=10,-1,0
  4310.1    0.08       0  4555.0    0.14       0  4757.3    0.08       0
  4818.0    0.05       0  4832.0    0.08       0  4967.7    0.13       0
  4974.9   0.042       0  5020.9    0.13       0  5023.8    0.08       0
  5303.4    0.15       0
Bank Sta=4974.9,5020.9
XS Rating Curve= 0
Exp/Cntr=0.3,0.1

Type RM Length L Ch R = 1,159604,422,409,411
BEGIN DESCRIPTION:
Fourth Creek 262.0
END DESCRIPTION:
XS GIS Cut Line= 3
      1427446.84       768343.07      1427477.13       767615.97
      1427492.28       767239.81
#Sta/Elev= 30
  4274.3  868.54  4360.7  862.11  4479.4  848.31  4577.9  842.12  4585.5  840.23
  4618.2  841.18  4636.0  838.22  4760.4  831.12  4832.0  830.14  4893.7  831.79
  4912.0  829.92  4926.1  823.80  4927.2  829.07  4930.0  830.03  4974.9  832.67
  4992.9  822.36  5006.5  822.11  5008.3  823.47  5009.7  827.93  5020.9  832.84
  5026.2  832.26  5067.6  830.67  5190.4  831.44  5217.5  833.50  5241.1  847.03
  5250.8  848.20  5265.5  859.03  5288.6  868.04  5337.0  879.26  5378.5  883.16
#Mann=8,-1,0
  4274.3    0.08       0  4893.7    0.13       0  4912.0    0.05       0
  4930.0    0.13       0  4974.9   0.042       0  5020.9    0.13       0
  5026.2    0.08       0  5190.4    0.15       0
#XS Ineff=2,0
    0.00 4722.10  870.42               0
Permanent Ineff=
       F       F
Bank Sta=4974.9,5020.9
XS Rating Curve= 0
Exp/Cntr=0.3,0.1

Type RM Length L Ch R = 1,159195,133,139,145
BEGIN DESCRIPTION:
Fourth Creek 261.0
END DESCRIPTION:
XS GIS Cut Line= 4
      1427892.18       768391.01      1427940.15       767992.14
      1427851.78       767492.27      1427882.08       767196.89
#Sta/Elev= 30
  4257.4  865.84  4389.0  858.19  4540.3  847.11  4724.0  848.09  4755.0  840.74
  4769.9  839.21  4787.6  840.32  4797.8  839.14  4883.1  839.74  4896.0  837.43
  4901.0  839.36  4946.6  838.74  4960.4  840.95  4968.3  838.38  4974.9  832.13
  4992.9  821.01  5006.5  820.76  5008.3  822.12  5009.7  826.58  5018.2  829.38
  5020.9  832.30  5035.9  833.12  5052.0  837.98  5073.3  840.76  5089.6  837.98
  5187.9  845.56  5208.9  843.62  5416.7  854.42  5438.4  856.96  5463.7  856.96
#Mann=5,-1,0
  4257.4    0.08       0  4787.6    0.13       0  4974.9   0.042       0
  5020.9    0.13       0  5438.4    0.08       0
Bank Sta=4974.9,5020.9
XS Rating Curve= 0
Exp/Cntr=0.5,0.3

Type RM Length L Ch R = 1,159056,135,140,140
BEGIN DESCRIPTION:
Wilkesboro Hwy (FC) us
END DESCRIPTION:
XS GIS Cut Line= 4
      1427917.42       768418.81      1427980.54       767845.71
      1428043.65       767537.71      1428179.97       767249.93
#Sta/Elev= 30
  4229.9  867.16  4323.5  861.70  4452.5  850.14  4560.9  848.09  4700.2  848.48
  4735.0  847.38  4746.5  846.23  4772.4  835.87  4799.6  832.91  4876.5  831.09
  4968.5  831.11  4974.9  831.01  4992.9  820.70  5006.5  820.45  5008.3  821.81
  5009.7  826.27  5020.9  830.76  5035.3  831.99  5044.0  829.83  5054.1  831.04
  5070.2  830.02  5094.0  832.13  5126.0  831.59  5180.3  834.11  5250.4  845.14
  5300.5  849.34  5317.5  852.57  5332.2  857.11  5364.8  861.87  5439.3  868.19
#Mann=5,-1,0
  4229.9    0.08       0  4968.5    0.13       0  4974.9   0.042       0
  5020.9    0.13       0  5070.2    0.08       0
#XS Ineff=2,0
    0.00 4877.50  847.43 5125.80    0.00  852.07
Permanent Ineff=
       F       F
Bank Sta=4974.9,5020.9
XS Rating Curve= 0
Exp/Cntr=0.5,0.3

Type RM Length L Ch R =3,158979,,,
BEGIN DESCRIPTION:
Wilkesboro Hwy (FC) TOR
Structure ID: I_FC_18
Detailed Survey Structure
END DESCRIPTION:
Bridge Culvert--1,0,-1,-1,0
Deck Dist Width WeirC Skew NumUp NumDn MinLoCord MaxHiCord MaxSubmerge Is_Ogee
57,40,3,,22,22,,,,0,1,1,,,
  4199.5  4344.7  4567.2  4697.7  4807.6  4852.5  4901.6  4925.9  4925.9  4926.2
  4934.5  4934.5  5063.7  5063.9  5063.9  5068.8  5068.8  5125.0  5150.6  5200.8
  5324.4  5432.6
  858.62  853.25  848.17  846.71  846.87  847.26  847.60  847.82  848.20  850.09
  850.24  850.24  852.59  850.93  850.33  850.43  850.43  852.04  852.86  854.63
  859.97  864.77
  800.45  800.45  800.45  800.45  800.45  800.45  800.45  800.45  800.45  800.45
  800.45  844.02  846.45  846.46  846.46  846.55  800.45  800.45  800.45  800.45
  800.45  800.45
  4199.5  4344.7  4567.2  4697.7  4807.6  4852.5  4901.6  4925.9  4925.9  4926.2
  4934.5  4934.5  5063.7  5063.9  5063.9  5068.8  5068.8  5125.0  5150.6  5200.8
  5324.4  5432.6
  858.62  853.25  848.17  846.71  846.87  847.26  847.60  847.82  848.20  850.09
  850.24  850.24  852.59  850.93  850.33  850.43  850.43  852.04  852.86  854.63
  859.97  864.77
  800.45  800.45  800.45  800.45  800.45  800.45  800.45  800.45  800.45  800.45
  800.45  844.02  846.45  846.46  846.46  846.55  800.45  800.45  800.45  800.45
  800.45  800.45
Pier Skew, UpSta & Num, DnSta & Num=,4972.5,2,4972.5,2,0,0,0,0,0
       1       1
  831.04  844.74
       1       1
  831.31  844.74
Pier Skew, UpSta & Num, DnSta & Num=,5018.1,2,5018.1,2,0,0,0,0,0
       1       1
  829.03  845.59
       1       1
  829.30  845.59
BR Coef=1,1,0,1.25,0,,,0.8,0,2,0,
WSPro=,,,, 1 ,,,, 0 ,,,, 0 ,,,,-1 ,-1 ,-1 , 0 , 0 , 0 , 0 , 0
BC Design=,,0,,0,,,,,,

Type RM Length L Ch R = 1,158916,246,235,232
BEGIN DESCRIPTION:
Wilkesboro Hwy (FC) ds
END DESCRIPTION:
XS GIS Cut Line= 4
      1428041.13       768439.02      1428124.44       767764.93
      1428177.46       767578.10      1428288.54       767290.31
#Sta/Elev= 30
  4195.9  866.93  4325.8  859.38  4412.0  851.43  4592.5  840.63  4606.2  843.53
  4656.2  845.01  4686.3  836.81  4691.7  833.98  4699.6  833.13  4715.9  833.88
  4791.5  830.54  4841.7  831.48  4919.1  828.34  4968.5  830.88  4974.9  830.78
  4992.9  820.47  5006.5  820.22  5008.3  821.58  5009.7  826.04  5020.9  830.63
  5070.2  833.42  5089.2  834.17  5138.7  841.01  5162.4  846.64  5244.3  855.22
  5288.5  862.64  5295.6  862.34  5326.2  867.72  5349.3  869.36  5377.8  873.88
#Mann=5,-1,0
  4195.9    0.08       0  4968.5    0.13       0  4974.9   0.042       0
  5020.9    0.13       0  5070.2    0.08       0
#XS Ineff=2,0
    0.00 4891.50  847.53 5111.80    0.00  851.66
Permanent Ineff=
       F       F
Bank Sta=4974.9,5020.9
XS Rating Curve= 0
Exp/Cntr=0.5,0.3

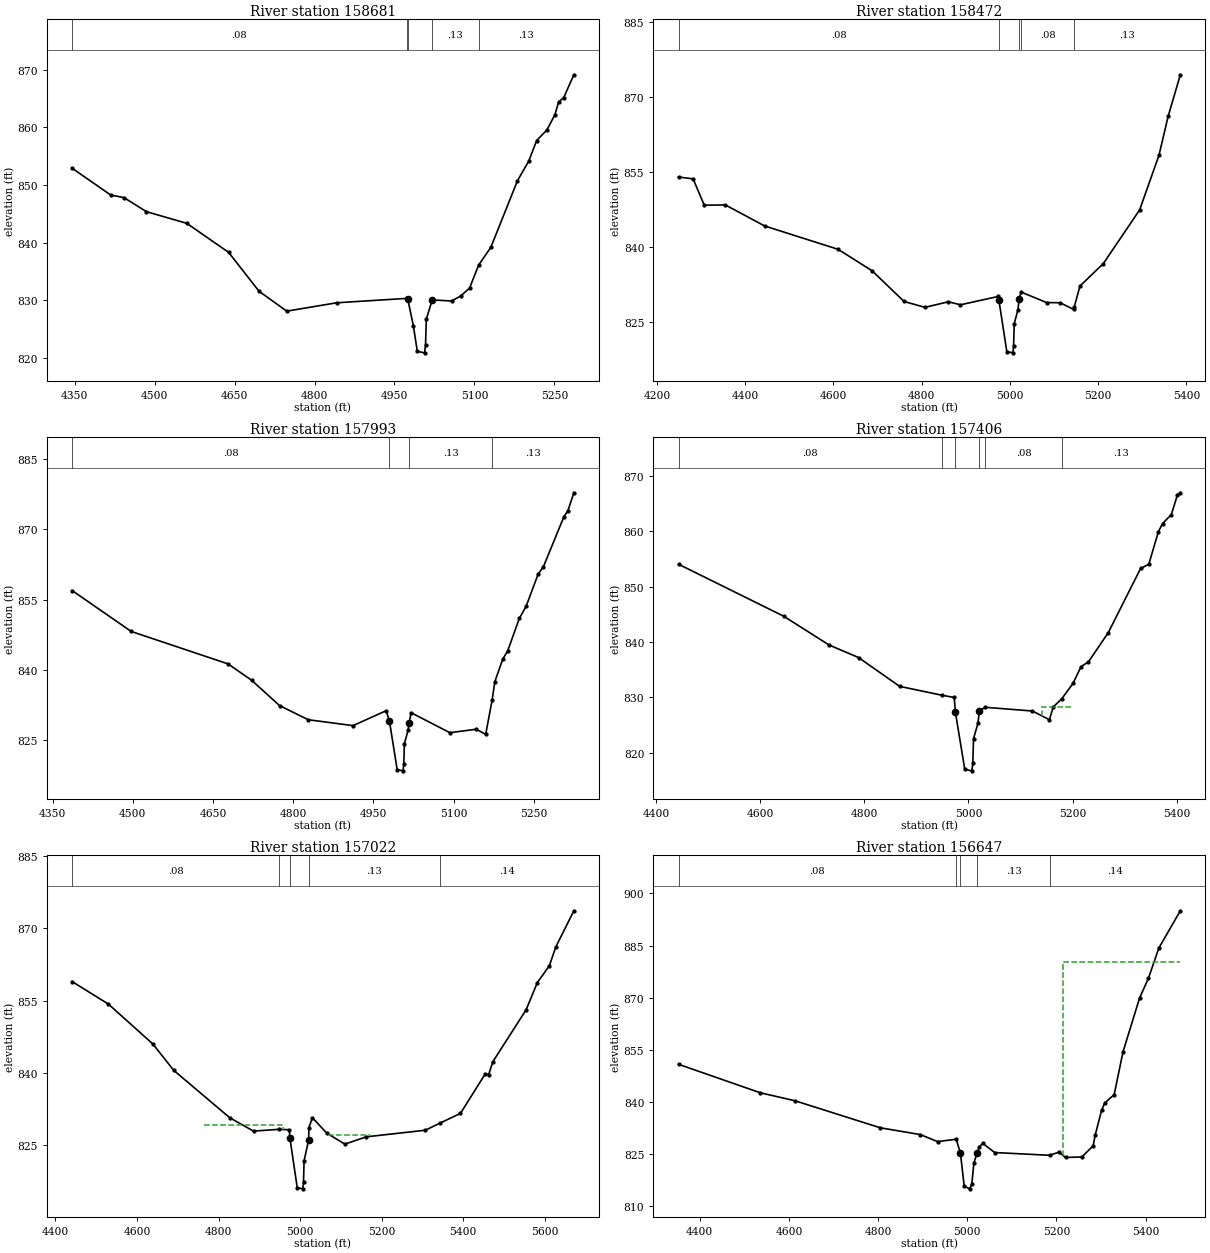
Type RM Length L Ch R = 1,158681,205,209,201
BEGIN DESCRIPTION:
Fourth Creek 260.5
END DESCRIPTION:
XS GIS Cut Line= 4
      1428306.67       768294.76      1428373.57       767995.46
      1428394.70       767562.37      1428380.62       767361.65
#Sta/Elev= 30
  4345.1  852.90  4417.7  848.24  4442.5  847.80  4484.7  845.36  4560.3  843.34
  4638.8  838.31  4695.9  831.56  4747.9  828.11  4841.5  829.56  4972.7  830.32
  4974.9  830.24  4985.5  825.55  4992.9  821.13  5006.5  820.88  5008.3  822.24
  5009.7  826.70  5020.9  830.06  5057.1  829.87  5074.5  830.75  5091.0  832.12
  5107.8  836.08  5130.8  839.17  5180.8  850.73  5202.0  854.14  5216.8  857.70
  5236.1  859.54  5251.2  862.21  5258.0  864.38  5267.6  865.15  5286.6  869.10
#Mann=5,-1,0
  4345.1    0.08       0  4972.7    0.13       0  4974.9    0.04       0
  5020.9    0.13       0  5107.8    0.13       0
Bank Sta=4974.9,5020.9
XS Rating Curve= 0
Exp/Cntr=0.3,0.1

Type RM Length L Ch R = 1,158472,479,479,482
BEGIN DESCRIPTION:
Fourth Creek 260.0
END DESCRIPTION:
XS GIS Cut Line= 5
      1428330.27       768333.78      1428577.23       767971.05
      1428596.53       767662.32      1428584.95       767507.95
      1428503.90       767287.96
#Sta/Elev= 30
  4248.8  854.01  4281.9  853.63  4307.1  848.37  4354.8  848.44  4443.8  844.24
  4610.5  839.57  4687.6  835.28  4760.0  829.16  4807.4  827.99  4860.4  829.10
  4887.9  828.50  4973.2  830.16  4974.9  829.47  4992.9  819.16  5006.5  818.91
  5008.3  820.27  5009.7  824.73  5018.2  827.53  5020.9  829.68  5025.4  831.04
  5082.9  828.95  5113.9  828.91  5144.1  827.58  5146.0  828.15  5158.7  832.24
  5211.7  836.73  5294.0  847.44  5337.9  858.37  5358.5  866.09  5386.2  874.41
#Mann=5,-1,0
  4248.8    0.08       0  4974.9   0.042       0  5020.9    0.08       0
  5025.4    0.08       0  5146.0    0.13       0
Bank Sta=4974.9,5020.9
XS Rating Curve= 0
Exp/Cntr=0.3,0.1

Type RM Length L Ch R = 1,157993,588,587,575
BEGIN DESCRIPTION:
Fourth Creek 259.0
END DESCRIPTION:
XS GIS Cut Line= 3
      1429059.62       768264.36      1429070.99       767650.97
      1429082.78       767326.58
#Sta/Elev= 30
  4386.5  856.96  4497.1  848.22  4677.8  841.31  4722.4  837.79  4774.3  832.40
  4828.0  829.38  4911.7  828.12  4973.8  831.31  4979.9  829.03  4994.3  818.72
  5005.2  818.47  5006.6  819.83  5007.8  824.29  5014.6  827.09  5016.7  828.69
  5020.3  830.88  5092.8  826.61  5142.0  827.35  5159.8  826.25  5171.7  833.53
  5176.9  837.52  5191.7  842.33  5200.9  844.07  5222.6  851.00  5235.3  853.57
  5257.7  860.42  5267.8  862.07  5306.0  872.71  5313.4  873.97  5324.6  877.82
#Mann=4,-1,0
  4386.5    0.08       0  4979.9   0.042       0  5016.7    0.13       0
  5171.7    0.13       0
#XS Ineff=1,-1
 4798.60 4956.80  829.64
Permanent Ineff=
       F
Bank Sta=4979.9,5016.7
XS Rating Curve= 0
Exp/Cntr=0.3,0.1

Type RM Length L Ch R = 1,157406,382,384,389
BEGIN DESCRIPTION:
Fourth Creek 258.0
END DESCRIPTION:
XS GIS Cut Line= 4
      1429692.53       768202.61      1429653.93       767658.46
      1429638.50       767519.53      1429484.13       767287.98
#Sta/Elev= 30
  4443.2  854.04  4645.1  844.65  4732.2  839.45  4788.9  837.18  4867.6  831.98
  4949.4  830.36  4972.6  829.97  4974.9  827.27  4992.9  816.96  5006.5  816.71
  5008.3  818.07  5009.7  822.53  5018.2  825.33  5020.9  827.56  5032.3  828.19
  5122.7  827.52  5155.4  825.95  5162.7  828.24  5179.2  829.74  5200.7  832.51
  5216.3  835.56  5230.4  836.40  5268.5  841.69  5330.5  853.27  5346.2  854.02
  5364.7  859.92  5372.6  861.39  5389.5  863.01  5401.3  866.58  5406.8  866.95
#Mann=6,-1,0
  4443.2    0.08       0  4949.4    0.13       0  4974.9   0.042       0
  5020.9    0.13       0  5032.3    0.08       0  5179.2    0.13       0
#XS Ineff=1,-1
 5141.20 5198.10  828.29
Permanent Ineff=
       F
Bank Sta=4974.9,5020.9
XS Rating Curve= 0
Exp/Cntr=0.3,0.1

Type RM Length L Ch R = 1,157022,375,375,376
BEGIN DESCRIPTION:
Fourth Creek 257.0
END DESCRIPTION:
XS GIS Cut Line= 4
      1430012.83       768152.40      1430047.56       767758.79
      1430028.27       767596.71      1429951.09       766929.12
#Sta/Elev= 30
  4440.8  858.97  4529.8  854.30  4639.0  846.01  4690.0  840.56  4827.8  830.69
  4885.7  827.95  4948.1  828.31  4973.7  828.23  4974.9  826.53  4992.9  816.22
  5006.5  815.97  5008.3  817.33  5009.7  821.79  5020.9  826.11  5021.5  828.68
  5030.1  830.72  5065.6  827.50  5109.7  825.25  5162.2  826.76  5307.1  828.13
  5342.2  829.57  5393.1  831.62  5453.4  839.74  5462.4  839.67  5472.3  842.31
  5554.2  853.12  5581.7  858.76  5611.3  862.26  5626.9  866.15  5671.2  873.65
#Mann=5,-1,0
  4440.8    0.08       0  4948.1    0.13       0  4974.9   0.042       0
  5020.9    0.13       0  5342.2    0.14       0
#XS Ineff=2,-1
 4763.30 4958.40  829.22 5068.50 5172.50  827.16
Permanent Ineff=
       F       F
Bank Sta=4974.9,5020.9
XS Rating Curve= 0
Exp/Cntr=0.3,0.1

Type RM Length L Ch R = 1,156647,585,571,509
BEGIN DESCRIPTION:
Fourth Creek 256.0
END DESCRIPTION:
XS GIS Cut Line= 4
      1430391.80       768152.44      1430391.80       767511.81
      1430380.22       767415.33      1430414.96       767029.39
#Sta/Elev= 30
  4352.4  850.82  4535.4  842.63  4613.5  840.32  4804.7  832.54  4894.7  830.58
  4933.4  828.56  4975.1  829.24  4984.6  825.22  4993.0  815.77  5005.0  814.96
  5010.1  816.35  5014.7  822.34  5022.3  825.41  5026.9  827.07  5034.9  828.04
  5061.4  825.41  5184.8  824.62  5205.3  825.53  5220.2  823.99  5256.9  824.14
  5282.2  827.36  5286.6  830.34  5301.1  837.54  5308.2  839.71  5329.3  842.06
  5349.1  854.38  5386.3  869.89  5406.1  875.56  5429.6  884.31  5477.7  895.02
#Mann=5,-1,0
  4352.4    0.08       0  4975.1    0.13       0  4984.6   0.042       0
  5022.3    0.13       0  5184.8    0.14       0
#XS Ineff=2,0
       0                 5215.00    0.00  880.29
Permanent Ineff=
       F       F
Bank Sta=4984.6,5022.3
XS Rating Curve= 0
Exp/Cntr=0.3,0.1