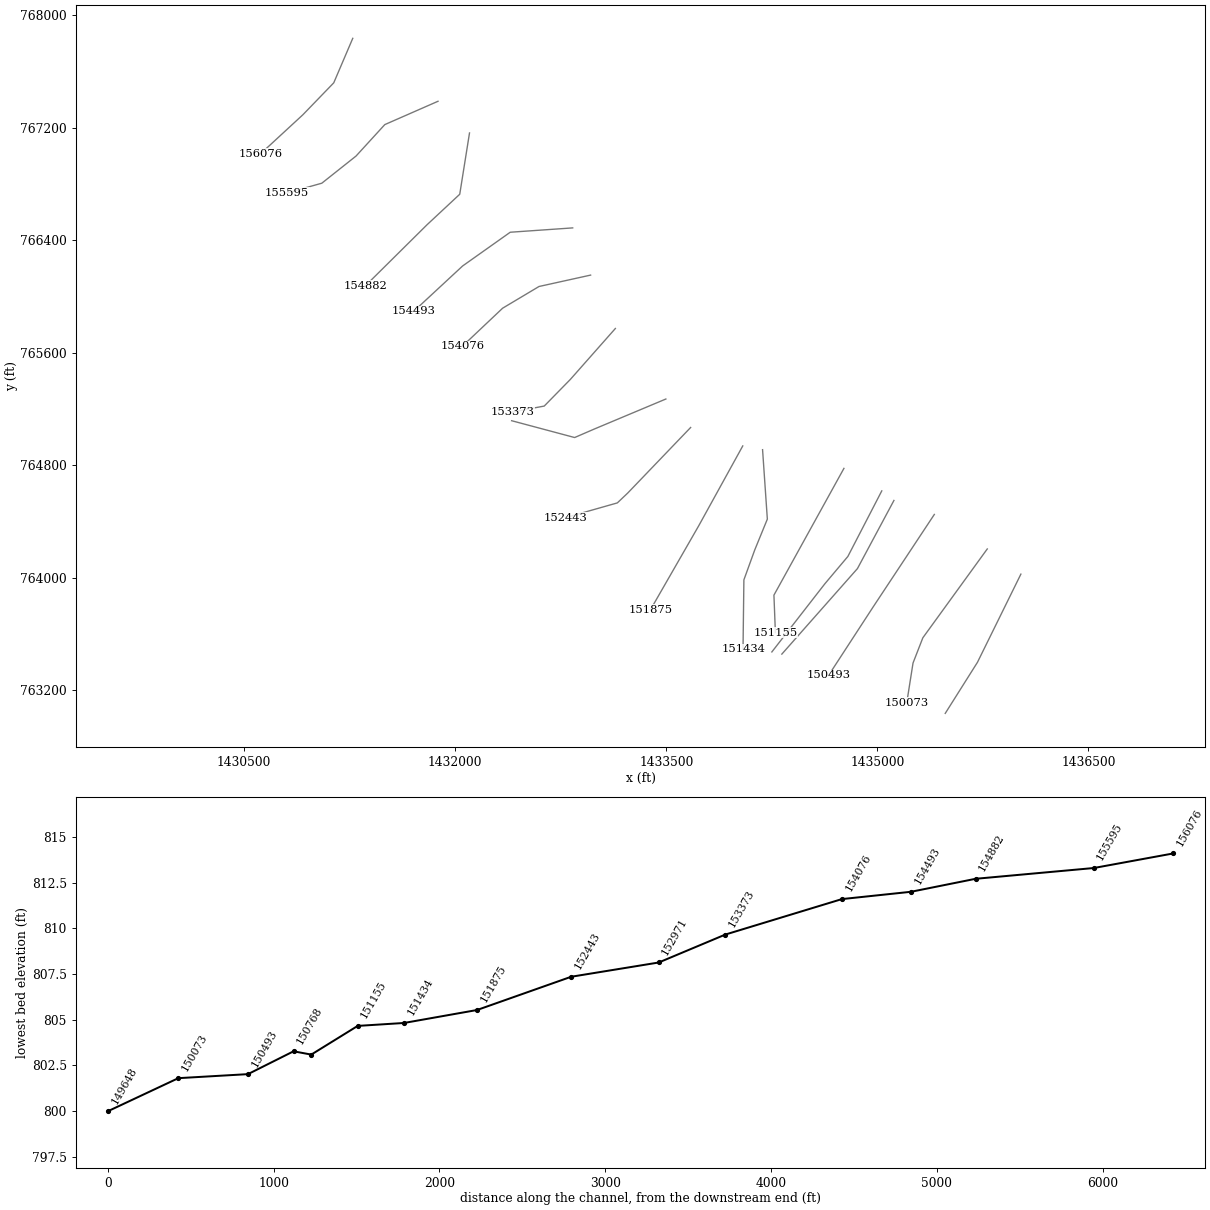
HEC-RAS study Fourth Creek.prj: Fourth Creek Detailed Study

--- Fourth Creek.g01 (geometry) --- (continued)

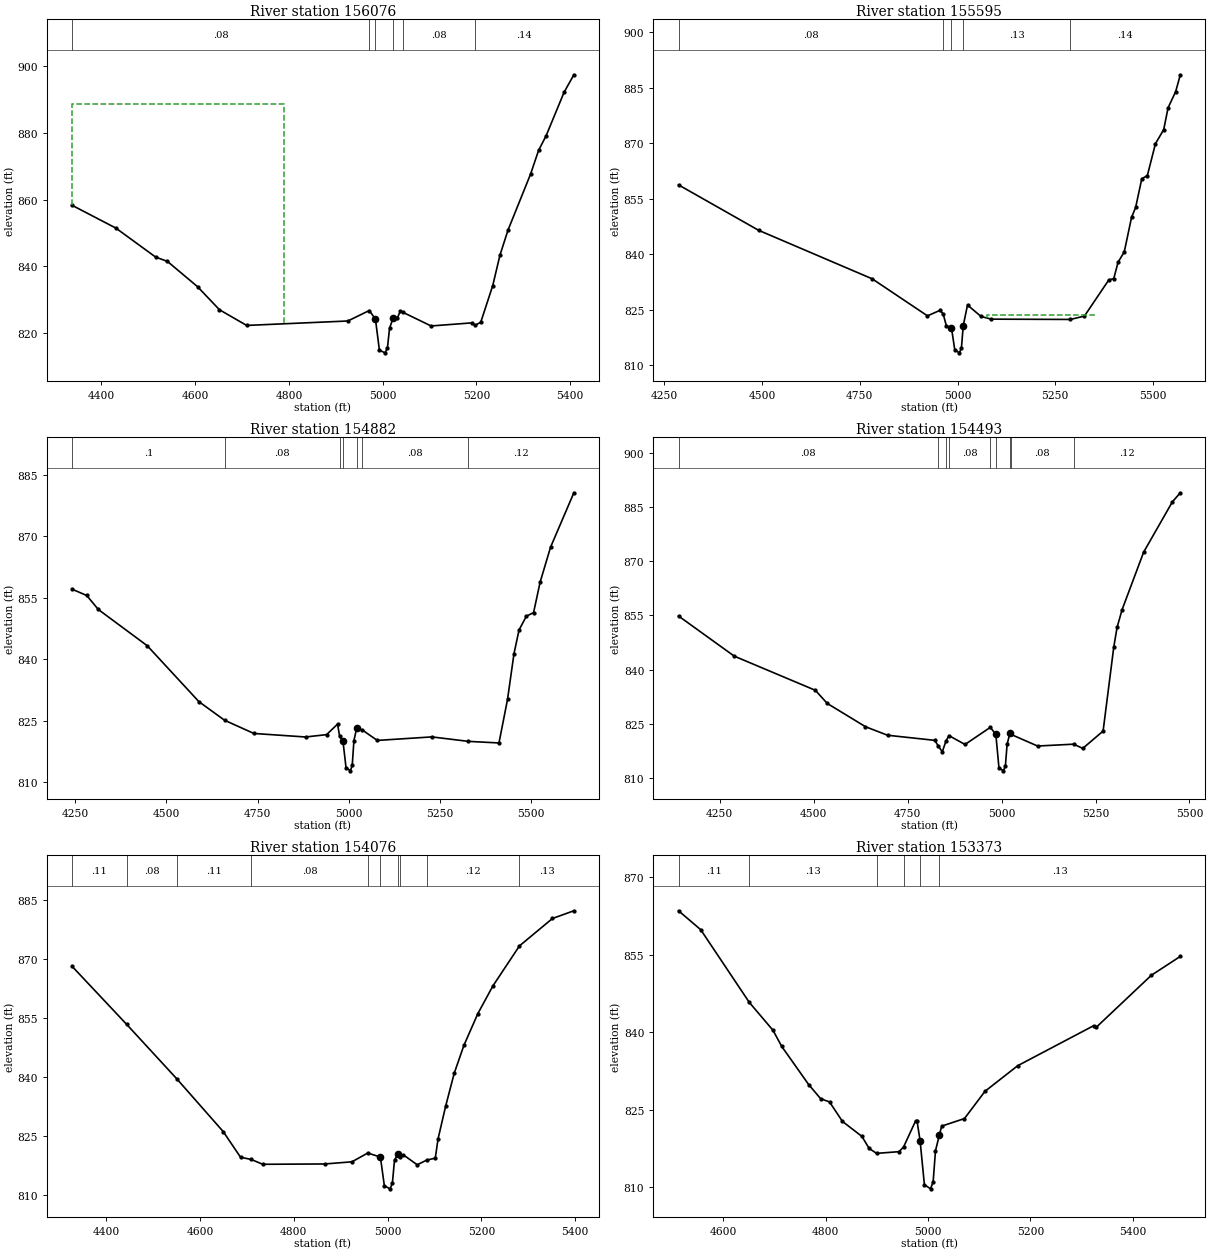
Type RM Length L Ch R = 1,156076,482,481,467
BEGIN DESCRIPTION:
Fourth Creek 255.0
END DESCRIPTION:
XS GIS Cut Line= 4
      1431271.68       767835.97      1431136.61       767519.53
      1430916.64       767291.84      1430615.63       767013.98
#Sta/Elev= 30
  4337.5  858.34  4430.8  851.52  4515.8  842.81  4540.9  841.52  4605.1  833.94
  4651.8  827.03  4709.9  822.32  4925.7  823.65  4971.5  826.79  4984.6  824.20
  4993.0  814.91  5005.0  814.10  5010.1  815.49  5014.7  821.48  5022.3  824.55
  5030.8  824.43  5037.8  826.63  5042.6  826.29  5103.3  822.16  5191.5  823.10
  5196.7  822.32  5209.2  823.28  5234.8  834.27  5250.1  843.37  5267.4  850.92
  5315.7  867.78  5332.5  874.79  5348.5  879.16  5387.0  892.25  5407.8  897.48
#Mann=6,-1,0
  4337.5    0.08       0  4971.5    0.13       0  4984.6   0.042       0
  5022.3    0.13       0  5042.6    0.08       0  5196.7    0.14       0
#XS Ineff=2,0
    0.00 4789.60  888.59               0
Permanent Ineff=
       F       F
Bank Sta=4984.6,5022.3
XS Rating Curve= 0
Exp/Cntr=0.3,0.1

Type RM Length L Ch R = 1,155595,712,713,717
BEGIN DESCRIPTION:
Fourth Creek 254.0
END DESCRIPTION:
XS GIS Cut Line= 5
      1431877.54       767388.30      1431499.37       767222.37
      1431294.84       766998.54      1431051.77       766805.52
      1430804.70       766736.11
#Sta/Elev= 30
  4286.6  858.72  4491.3  846.44  4781.9  833.31  4923.2  823.30  4955.6  824.81
  4963.3  823.81  4971.5  820.62  4984.6  820.01  4993.0  814.11  5005.0  813.30
  5010.1  814.69  5014.7  820.68  5025.6  826.23  5060.1  823.14  5086.0  822.41
  5288.9  822.33  5324.6  823.25  5386.8  833.00  5399.6  833.38  5410.7  837.84
  5426.4  840.57  5445.0  849.91  5455.5  852.61  5471.2  860.36  5485.5  861.25
  5506.2  869.86  5527.3  873.67  5538.5  879.57  5557.9  883.94  5569.8  888.49
#Mann=5,-1,0
  4286.6    0.08       0  4963.3    0.13       0  4984.6   0.042       0
  5014.7    0.13       0  5288.9    0.14       0
#XS Ineff=1,-1
 5075.40 5356.90  823.51
Permanent Ineff=
       F
Bank Sta=4984.6,5014.7
XS Rating Curve= 0
Exp/Cntr=0.3,0.1

Type RM Length L Ch R = 1,154882,400,389,384
BEGIN DESCRIPTION:
Fourth Creek 253.0 (Survey)
END DESCRIPTION:
XS GIS Cut Line= 4
      1432101.41       767162.99      1432031.94       766726.86
      1431800.39       766510.75      1431360.45       766074.67
#Sta/Elev= 30
  4240.8  857.08  4281.1  855.54  4312.9  852.12  4447.2  843.27  4589.2  829.60
  4659.5  825.07  4739.9  821.84  4881.8  820.98  4939.6  821.55  4969.8  824.12
  4975.5  821.11  4984.6  819.96  4993.0  813.52  5005.0  812.71  5010.1  814.10
  5014.7  820.09  5022.3  823.16  5037.5  822.70  5078.9  820.14  5228.7  821.00
  5328.7  819.91  5413.0  819.52  5436.5  830.18  5454.2  841.33  5468.1  847.13
  5488.2  850.48  5508.0  851.37  5526.0  858.81  5554.6  867.34  5618.6  880.63
#Mann=7,-1,0
  4240.8     0.1       0  4659.5    0.08       0  4975.5    0.13       0
  4984.6   0.042       0  5022.3    0.13       0  5037.5    0.08       0
  5328.7    0.12       0
Bank Sta=4984.6,5022.3
XS Rating Curve= 0
Exp/Cntr=0.3,0.1

Type RM Length L Ch R = 1,154493,421,417,419
BEGIN DESCRIPTION:
Fourth Creek 252.0
END DESCRIPTION:
XS GIS Cut Line= 4
      1432834.67       766487.60      1432390.84       766456.72
      1432052.46       766216.81      1431703.88       765893.26
#Sta/Elev= 30
  4140.3  854.81  4288.6  843.71  4504.4  834.27  4536.0  830.64  4637.8  824.20
  4696.6  821.84  4822.4  820.43  4831.0  818.92  4842.2  817.26  4852.0  820.26
  4859.9  821.74  4902.7  819.29  4969.9  824.02  4984.6  822.12  4993.0  812.81
  5005.0  812.00  5010.1  813.39  5014.7  819.38  5022.3  822.45  5025.1  822.07
  5095.7  818.86  5191.6  819.37  5216.1  818.21  5270.1  823.00  5298.4  846.14
  5307.3  851.68  5320.6  856.55  5378.0  872.47  5454.5  886.38  5475.6  888.88
#Mann=9,-1,0
  4140.3    0.08       0  4831.0    0.05       0  4852.0     0.1       0
  4859.9    0.08       0  4969.9    0.13       0  4984.6   0.042       0
  5022.3    0.13       0  5025.1    0.08       0  5191.6    0.12       0
Bank Sta=4984.6,5022.3
XS Rating Curve= 0
Exp/Cntr=0.3,0.1

Type RM Length L Ch R = 1,154076,677,703,704
BEGIN DESCRIPTION:
Fourth Creek 251.0
END DESCRIPTION:
XS GIS Cut Line= 4
      1432961.97       766151.84      1432595.37       766070.81
      1432336.81       765916.44      1432051.22       765646.29
#Sta/Elev= 30
  4327.3  868.24  4443.5  853.49  4550.4  839.62  4649.6  826.16  4686.5  819.64
  4709.2  819.08  4733.7  817.85  4865.8  817.93  4923.9  818.48  4957.7  820.72
  4984.6  819.68  4993.0  812.41  5005.0  811.60  5010.1  812.99  5014.7  818.98
  5022.3  820.42  5025.9  819.80  5033.2  820.28  5063.1  817.72  5083.1  818.90
  5101.6  819.42  5107.5  824.31  5123.6  832.61  5141.9  841.00  5162.6  848.12
  5192.4  856.22  5224.5  863.27  5281.1  873.45  5351.4  880.42  5397.0  882.38
#Mann=10,-1,0
  4327.3    0.11       0  4443.5    0.08       0  4550.4    0.11       0
  4709.2    0.08       0  4957.7    0.13       0  4984.6   0.042       0
  5022.3    0.13       0  5025.9    0.08       0  5083.1    0.12       0
  5281.1    0.13       0
Bank Sta=4984.6,5022.3
XS Rating Curve= 0
Exp/Cntr=0.3,0.1

Type RM Length L Ch R = 1,153373,422,402,397
BEGIN DESCRIPTION:
Fourth Creek 250.0
END DESCRIPTION:
XS GIS Cut Line= 4
      1433137.98       765772.12      1432817.66       765409.35
      1432632.42       765220.25      1432404.70       765177.80
#Sta/Elev= 30
  4512.7  863.51  4556.0  859.85  4651.0  845.76  4697.2  840.37  4714.3  837.24
  4766.9  829.86  4790.3  827.12  4807.7  826.49  4833.0  822.71  4871.0  819.81
  4885.0  817.49  4899.6  816.53  4943.5  816.86  4952.3  817.76  4975.9  822.83
  4978.7  822.76  4984.6  819.00  4993.0  810.47  5005.0  809.66  5010.1  811.05
  5014.7  817.04  5022.3  820.11  5026.9  821.81  5071.3  823.27  5111.3  828.54
  5175.2  833.50  5323.6  841.25  5328.8  840.95  5436.3  851.01  5493.0  854.68
#Mann=6,-1,0
  4512.7    0.11       0  4651.0    0.13       0  4899.6    0.08       0
  4952.3    0.13       0  4984.6   0.042       0  5022.3    0.13       0
Bank Sta=4984.6,5022.3
XS Rating Curve= 0
Exp/Cntr=0.3,0.1

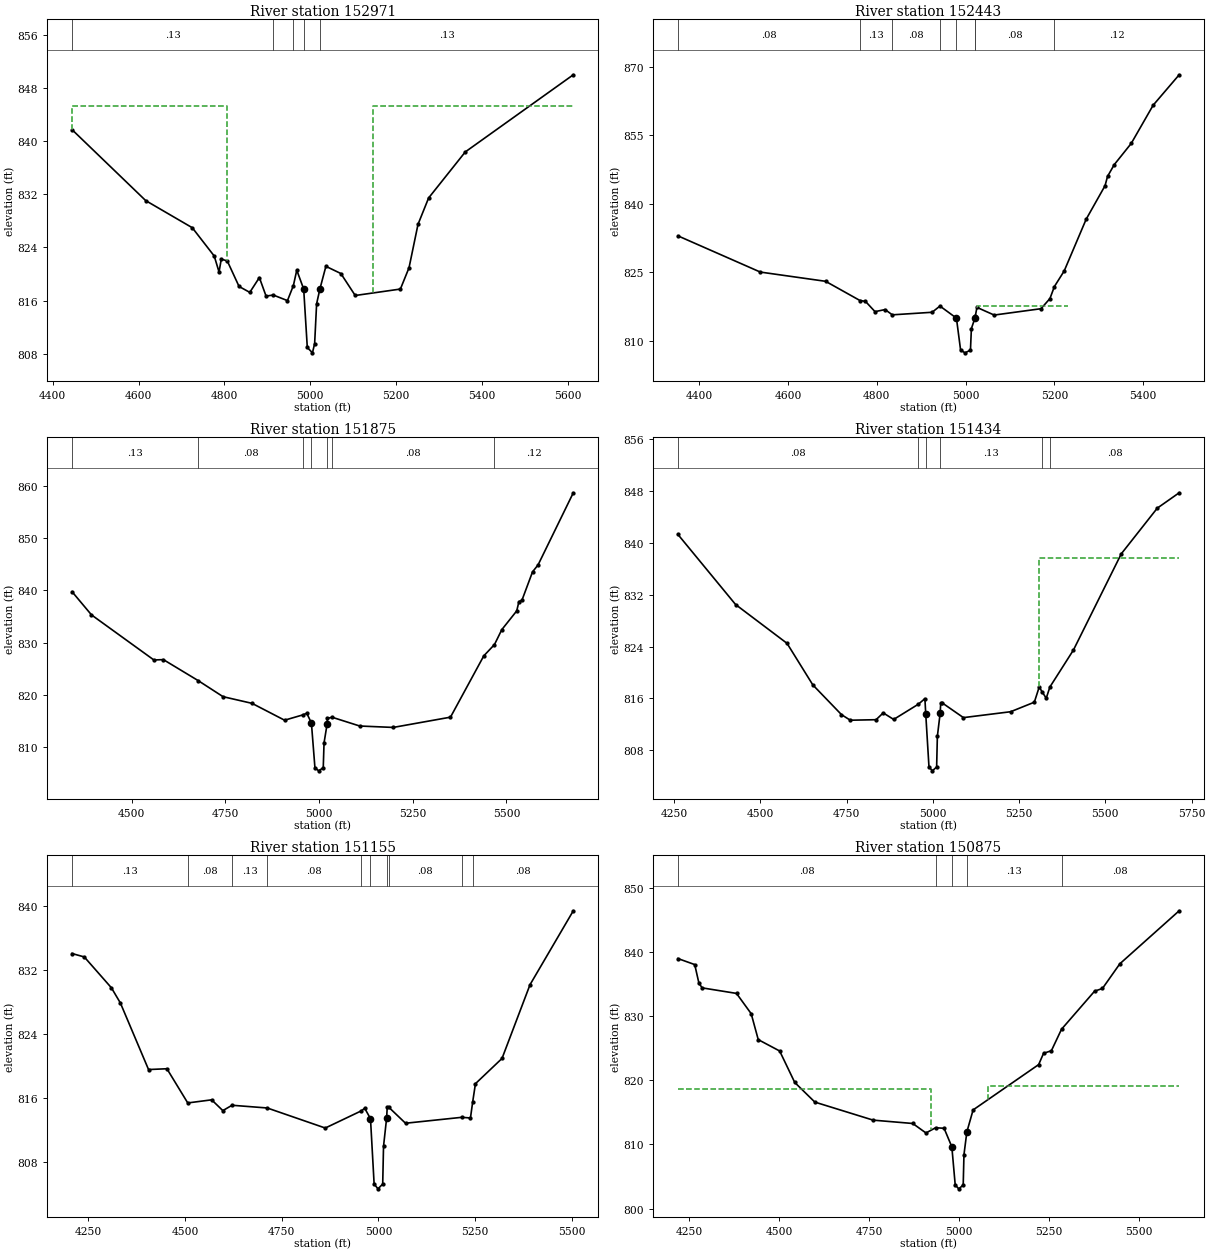
Type RM Length L Ch R = 1,152971,493,528,543
BEGIN DESCRIPTION:
Fourth Creek 249.0
END DESCRIPTION:
XS GIS Cut Line= 4
      1433496.83       765270.40      1432991.32       765058.17
      1432848.53       764996.42      1432400.86       765116.06
#Sta/Elev= 30
  4445.2  841.72  4616.8  831.04  4725.2  826.96  4776.3  822.70  4787.5  820.30
  4792.7  822.23  4806.6  821.97  4834.1  818.12  4859.1  817.23  4881.4  819.46
  4897.0  816.67  4913.8  816.83  4946.8  815.99  4960.6  818.25  4968.5  820.57
  4984.6  817.73  4993.0  808.94  5005.0  808.13  5010.1  809.52  5014.7  815.51
  5022.3  817.73  5036.3  821.15  5071.1  820.07  5104.6  816.76  5209.8  817.73
  5229.9  820.94  5250.8  827.47  5275.5  831.44  5360.9  838.37  5612.4  849.98
#Mann=5,-1,0
  4445.2    0.13       0  4913.8    0.08       0  4960.6    0.13       0
  4984.6   0.042       0  5022.3    0.13       0
#XS Ineff=2,0
    0.00 4806.30  845.35 5145.00    0.00  845.35
Permanent Ineff=
       F       F
Bank Sta=4984.6,5022.3
XS Rating Curve= 0
Exp/Cntr=0.3,0.1

Type RM Length L Ch R = 1,152443,540,568,581
BEGIN DESCRIPTION:
Fourth Creek 248.0
END DESCRIPTION:
XS GIS Cut Line= 4
      1433672.86       765067.83      1433225.18       764600.86
      1433151.86       764531.39      1432785.28       764427.21
#Sta/Elev= 30
  4352.2  832.96  4537.8  825.03  4684.8  823.01  4762.3  818.80  4774.6  818.62
  4796.1  816.37  4818.8  816.82  4835.1  815.67  4924.7  816.23  4942.4  817.59
  4979.5  814.95  4988.9  807.95  4998.9  807.35  5011.1  807.95  5013.2  812.67
  5021.2  814.95  5022.0  815.37  5025.7  817.30  5064.5  815.62  5169.9  817.01
  5190.1  819.23  5200.2  821.87  5222.2  825.27  5271.7  836.60  5314.2  843.93
  5319.8  845.96  5334.9  848.54  5373.2  853.19  5422.6  861.56  5481.2  868.22
#Mann=8,-1,0
  4352.2    0.08       0  4762.3    0.13       0  4835.1    0.08       0
  4942.4    0.13       0  4979.5   0.042       0  5021.2    0.13       0
  5022.0    0.08       0  5200.2    0.12       0
#XS Ineff=2,-1
 4751.00 4944.30  816.94 5025.30 5231.00  817.61
Permanent Ineff=
       F       F
Bank Sta=4979.5,5021.2
XS Rating Curve= 0
Exp/Cntr=0.3,0.1

Type RM Length L Ch R = 1,151875,429,441,458
BEGIN DESCRIPTION:
Fourth Creek 247.0
END DESCRIPTION:
XS GIS Cut Line= 3
      1434043.32       764936.61      1433730.73       764369.31
      1433387.26       763771.12
#Sta/Elev= 30
  4340.8  839.74  4392.7  835.31  4559.2  826.70  4584.5  826.77  4677.4  822.76
  4743.8  819.69  4821.0  818.42  4907.9  815.20  4956.5  816.21  4967.1  816.53
  4979.5  814.67  4988.9  806.13  4998.9  805.53  5011.1  806.13  5013.2  810.85
  5021.2  814.38  5022.4  815.56  5034.9  815.76  5108.4  814.09  5197.8  813.82
  5350.6  815.78  5439.5  827.49  5468.0  829.65  5487.6  832.50  5527.3  836.07
  5533.3  837.86  5541.2  838.09  5569.5  843.52  5584.4  844.87  5678.3  858.63
#Mann=7,-1,0
  4340.8    0.13       0  4677.4    0.08       0  4956.5    0.13       0
  4979.5   0.042       0  5021.2    0.13       0  5034.9    0.08       0
  5468.0    0.12       0
Bank Sta=4979.5,5021.2
XS Rating Curve= 0
Exp/Cntr=0.3,0.1

Type RM Length L Ch R = 1,151434,295,279,263
BEGIN DESCRIPTION:
Fourth Creek 246.0
END DESCRIPTION:
XS GIS Cut Line= 5
      1434184.10       764910.16      1434218.06       764416.16
      1434128.53       764196.96      1434051.35       763983.94
      1434045.17       763490.00
#Sta/Elev= 30
  4261.4  841.29  4428.5  830.48  4577.6  824.49  4652.3  818.08  4735.4  813.49
  4760.9  812.63  4835.6  812.71  4856.3  813.76  4886.6  812.75  4958.1  815.10
  4977.1  815.96  4979.5  813.61  4988.9  805.42  4998.9  804.82  5011.1  805.42
  5013.2  810.14  5021.2  813.67  5023.0  815.28  5027.3  815.30  5088.7  813.03
  5225.5  813.94  5294.2  815.41  5308.4  817.77  5316.1  817.06  5328.7  816.02
  5339.2  817.75  5407.6  823.47  5546.1  838.30  5650.5  845.35  5713.9  847.72
#Mann=6,-1,0
  4261.4    0.08       0  4958.1    0.13       0  4979.5   0.042       0
  5021.2    0.13       0  5316.1    0.13       0  5339.2    0.08       0
#XS Ineff=2,0
       0                 5308.70    0.00  837.68
Permanent Ineff=
       F       F
Bank Sta=4979.5,5021.2
XS Rating Curve= 0
Exp/Cntr=0.3,0.1

Type RM Length L Ch R = 1,151155,303,280,281
BEGIN DESCRIPTION:
Fourth Creek 245.0
END DESCRIPTION:
XS GIS Cut Line= 3
      1434762.34       764777.06      1434264.86       763875.37
      1434275.22       763609.30
#Sta/Elev= 30
  4207.8  834.11  4239.5  833.68  4309.6  829.82  4332.8  827.92  4405.6  819.59
  4453.1  819.69  4507.0  815.41  4568.8  815.80  4597.7  814.45  4621.5  815.12
  4712.5  814.78  4862.6  812.27  4956.2  814.43  4964.5  814.75  4979.5  813.44
  4988.9  805.26  4998.9  804.66  5011.1  805.26  5013.2  809.98  5021.2  813.51
  5022.8  814.92  5027.0  814.86  5070.1  812.87  5215.4  813.61  5238.0  813.53
  5243.8  815.56  5250.9  817.82  5319.6  820.98  5392.0  830.21  5503.9  839.46
#Mann=10,-1,0
  4207.8    0.13       0  4507.0    0.08       0  4621.5    0.13       0
  4712.5    0.08       0  4956.2    0.13       0  4979.5    0.04       0
  5021.2    0.13       0  5027.0    0.08       0  5215.4    0.13       0
  5243.8    0.08       0
Bank Sta=4979.5,5021.2
XS Rating Curve= 0
Exp/Cntr=0.5,0.3

Type RM Length L Ch R = 1,150875,162,107,110
BEGIN DESCRIPTION:
Chipley Ford Rd (FC) us
END DESCRIPTION:
XS GIS Cut Line= 4
      1435031.27       764616.86      1434790.45       764150.65
      1434626.82       763956.15      1434250.14       763471.40
#Sta/Elev= 30
  4218.4  838.96  4265.1  838.02  4276.9  835.09  4286.0  834.39  4381.2  833.53
  4422.0  830.37  4441.6  826.33  4501.1  824.56  4543.0  819.66  4598.9  816.60
  4760.9  813.79  4870.9  813.27  4907.7  811.79  4934.4  812.61  4958.0  812.52
  4979.5  809.64  4988.9  803.69  4998.9  803.09  5011.1  803.69  5013.2  808.41
  5021.2  811.94  5038.6  815.38  5220.7  822.44  5234.4  824.20  5256.1  824.60
  5284.3  827.95  5376.2  833.88  5398.0  834.30  5446.3  838.14  5611.2  846.40
#Mann=5,-1,0
  4218.4    0.08       0  4934.4    0.13       0  4979.5   0.042       0
  5021.2    0.13       0  5284.3    0.08       0
#XS Ineff=2,0
    0.00 4921.80  818.57 5079.40    0.00  819.04
Permanent Ineff=
       F       F
Bank Sta=4979.5,5021.2
XS Rating Curve= 0
Exp/Cntr=0.5,0.3

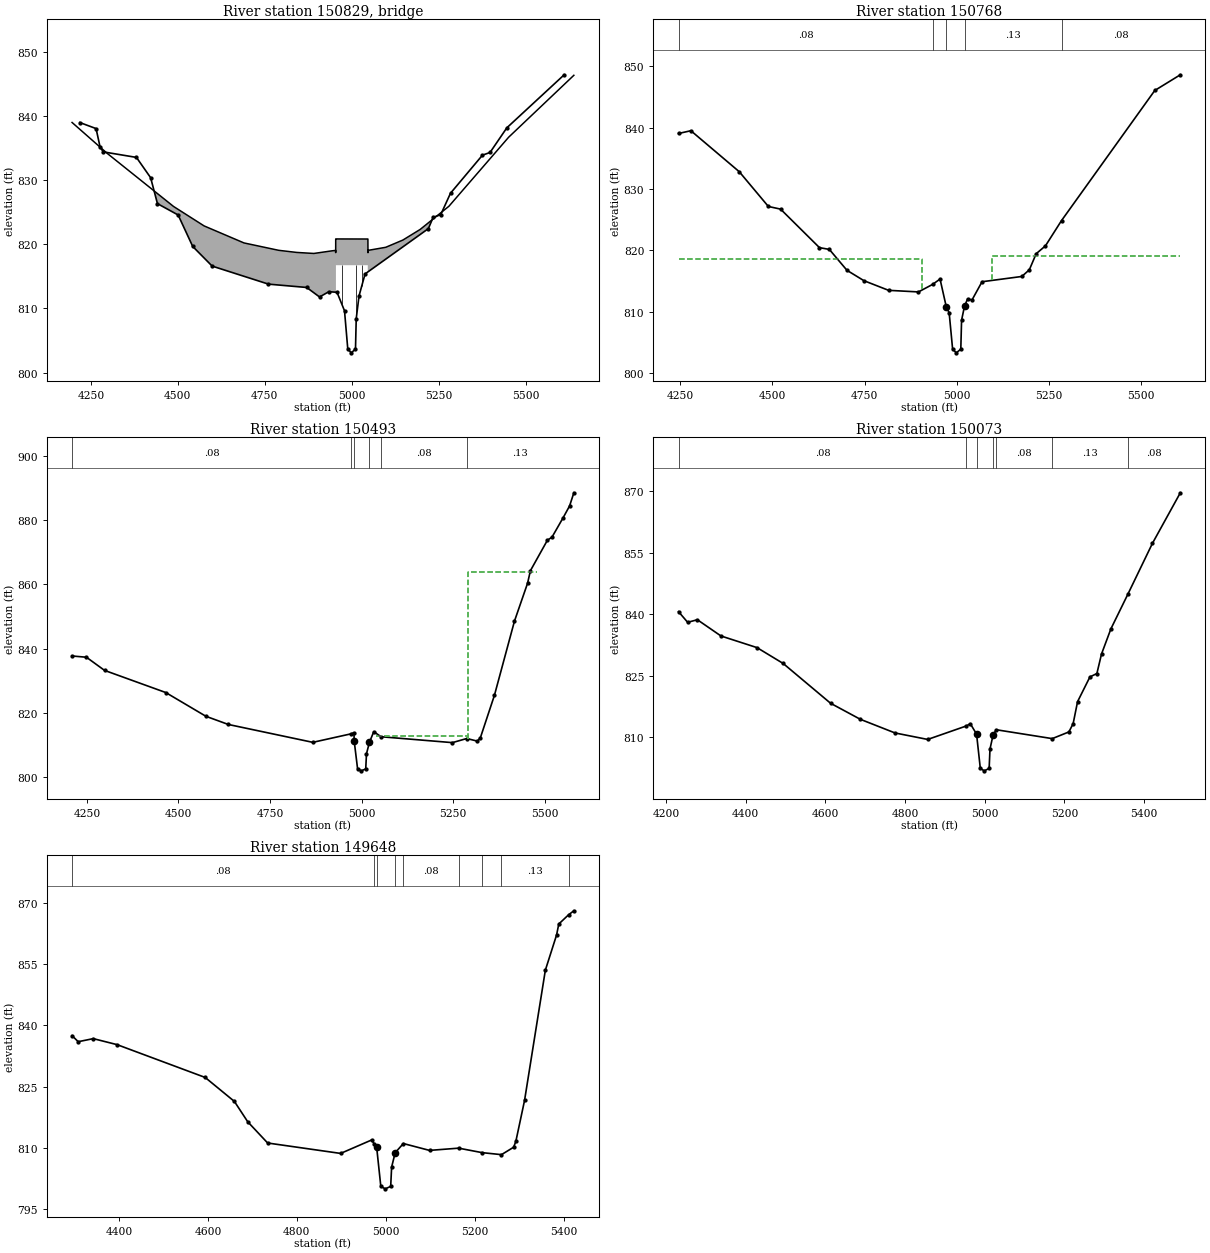
Type RM Length L Ch R =3,150829,,,
BEGIN DESCRIPTION:
Chipley Ford Rd (FC) TOR
Structure ID: I_FC_17
Detailed Survey Structure
END DESCRIPTION:
Bridge Culvert--1,0,-1,-1,0
Deck Dist Width WeirC Skew NumUp NumDn MinLoCord MaxHiCord MaxSubmerge Is_Ogee
33,26,3,,25,25,,,,0,1,1,,,
  4196.1  4296.4  4487.9  4575.8  4690.4  4790.2  4842.1  4891.3  4944.9  4954.1
  4954.1  4954.2  4954.8  4954.8  5046.4  5046.4  5046.8  5047.0  5047.0  5098.1
  5147.4  5197.0  5279.7  5451.4  5639.0
  838.97  834.19  825.89  822.86  820.21  819.06  818.73  818.57  818.99  819.04
  818.70  820.83  820.83  820.83  820.82  820.82  820.82  818.69  819.05  819.53
  820.66  822.31  825.92  836.67  846.32
  783.09  783.09  783.09  783.09  783.09  783.09  783.09  783.09  783.09  783.09
  783.09  783.09  783.09  816.74  816.74  783.09  783.09  783.09  783.09  783.09
  783.09  783.09  783.09  783.09  783.09
  4196.1  4296.4  4487.9  4575.8  4690.4  4790.2  4842.1  4891.3  4944.9  4954.1
  4954.1  4954.2  4954.8  4954.8  5046.4  5046.4  5046.8  5047.0  5047.0  5098.1
  5147.4  5197.0  5279.7  5451.4  5639.0
  838.97  834.19  825.89  822.86  820.21  819.06  818.73  818.57  818.99  819.04
  818.70  820.83  820.83  820.83  820.82  820.82  820.82  818.69  819.05  819.53
  820.66  822.31  825.92  836.67  846.32
  783.09  783.09  783.09  783.09  783.09  783.09  783.09  783.09  783.09  783.09
  783.09  783.09  783.09  816.74  816.74  783.09  783.09  783.09  783.09  783.09
  783.09  783.09  783.09  783.09  783.09
Pier Skew, UpSta & Num, DnSta & Num=,4971.9,2,4971.9,2,0,0,0,0,0
       1       1
  811.54  817.74
       1       1
  811.72  817.74
Pier Skew, UpSta & Num, DnSta & Num=,5013.2,2,5013.2,2,0,0,0,0,0
       1       1
  809.41  817.74
       1       1
  809.59  817.74
Pier Skew, UpSta & Num, DnSta & Num=,5028.9,2,5028.9,2,0,0,0,0,0
       1       1
  812.78  817.74
       1       1
  812.96  817.74
BR Coef=1,1,0,1.25,0,,,0.8,0,2,0,
WSPro=,,,, 1 ,,,, 0 ,,,, 0 ,,,,-1 ,-1 ,-1 , 0 , 0 , 0 , 0 , 0
BC Design=,,0,,0,,,,,,

Type RM Length L Ch R = 1,150768,265,275,281
BEGIN DESCRIPTION:
Chipley Ford Rd (FC) ds
END DESCRIPTION:
XS GIS Cut Line= 3
      1435117.70       764548.90      1434858.37       764064.21
      1434321.16       763455.99
#Sta/Elev= 30
  4245.4  839.03  4278.9  839.48  4410.1  832.80  4489.1  827.13  4522.2  826.70
  4627.7  820.42  4654.5  820.13  4702.4  816.72  4748.4  815.03  4815.2  813.46
  4896.2  813.20  4934.4  814.42  4954.8  815.30  4971.9  810.72  4979.5  809.82
  4988.9  803.87  4998.9  803.27  5011.1  803.87  5013.2  808.59  5021.2  810.89
  5029.7  812.07  5041.5  811.89  5068.7  814.86  5176.6  815.72  5197.0  816.81
  5215.6  819.43  5240.7  820.71  5284.3  824.83  5537.3  846.04  5606.6  848.60
#Mann=5,-1,0
  4245.4    0.08       0  4934.4    0.13       0  4971.9   0.042       0
  5021.2    0.13       0  5284.3    0.08       0
#XS Ineff=2,0
    0.00 4906.80  818.57 5094.40    0.00  819.04
Permanent Ineff=
       F       F
Bank Sta=4971.9,5021.2
XS Rating Curve= 0
Exp/Cntr=0.5,0.3

Type RM Length L Ch R = 1,150493,420,420,431
BEGIN DESCRIPTION:
Fourth Creek 244.0
END DESCRIPTION:
XS GIS Cut Line= 3
      1435404.74       764449.29      1434969.00       763789.96
      1434653.20       763304.55
#Sta/Elev= 30
  4209.7  837.73  4248.9  837.34  4298.3  833.25  4465.3  826.37  4575.0  818.98
  4636.0  816.44  4866.7  810.88  4971.6  813.54  4979.1  813.88  4979.5  811.42
  4988.9  802.62  4998.9  802.02  5011.1  802.62  5013.2  807.34  5021.2  810.87
  5033.0  814.19  5053.0  812.62  5247.6  810.79  5286.9  812.07  5315.9  811.25
  5323.9  812.28  5362.3  825.49  5417.1  848.60  5452.7  860.32  5460.5  864.24
  5507.0  873.74  5519.4  874.67  5549.9  880.73  5567.4  884.37  5579.1  888.47
#Mann=6,-1,0
  4209.7    0.08       0  4971.6    0.13       0  4979.5   0.042       0
  5021.2    0.13       0  5053.0    0.08       0  5286.9    0.13       0
#XS Ineff=3,-1
 4660.50 4963.70  812.81 5289.50 5478.90  863.71 5040.00 5289.40  812.73
Permanent Ineff=
       F       F       F
Bank Sta=4979.5,5021.2
XS Rating Curve= 0
Exp/Cntr=0.3,0.1

Type RM Length L Ch R = 1,150073,411,425,410
BEGIN DESCRIPTION:
Fourth Creek 243.0
END DESCRIPTION:
XS GIS Cut Line= 4
      1435780.98       764203.90      1435323.12       763571.86
      1435253.45       763392.69      1435208.65       763109.00
#Sta/Elev= 30
  4231.2  840.63  4254.1  838.03  4278.5  838.66  4337.7  834.70  4428.2  831.86
  4493.8  828.00  4613.0  818.28  4687.7  814.37  4774.8  811.04  4856.8  809.46
  4953.6  812.74  4963.8  813.30  4979.5  810.76  4988.9  802.40  4998.9  801.80
  5011.1  802.40  5013.2  807.12  5021.2  810.65  5029.3  811.82  5169.5  809.66
  5211.3  811.29  5222.0  813.32  5233.1  818.68  5264.1  824.71  5281.6  825.54
  5293.2  830.29  5316.8  836.44  5359.2  844.85  5421.2  857.32  5491.1  869.63
#Mann=7,-1,0
  4231.2    0.08       0  4953.6    0.13       0  4979.5   0.042       0
  5021.2    0.13       0  5029.3    0.08       0  5169.5    0.13       0
  5359.2    0.08       0
Bank Sta=4979.5,5021.2
XS Rating Curve= 0
Exp/Cntr=0.3,0.1

Type RM Length L Ch R = 1,149648,578,543,509
BEGIN DESCRIPTION:
Fourth Creek 242.0
END DESCRIPTION:
XS GIS Cut Line= 3
      1436019.91       764024.79      1435711.33       763397.66
      1435482.37       763034.32
#Sta/Elev= 30
  4294.6  837.49  4308.4  836.01  4342.3  836.76  4395.8  835.29  4593.9  827.26
  4659.7  821.38  4689.6  816.41  4734.4  811.21  4898.5  808.66  4968.4  811.96
  4973.9  811.03  4979.5  810.22  4988.9  800.59  4998.9  799.99  5011.1  800.59
  5013.2  805.31  5021.2  808.84  5039.6  811.08  5098.4  809.40  5163.9  809.95
  5216.8  808.85  5260.2  808.36  5287.6  810.18  5292.6  811.64  5312.1  821.62
  5358.9  853.52  5384.1  862.12  5389.1  864.82  5411.0  867.07  5423.0  868.06
#Mann=9,-1,0
  4294.6    0.08       0  4973.9    0.13       0  4979.5   0.042       0
  5021.2    0.13       0  5039.6    0.08       0  5163.9    0.13       0
  5216.8    0.08       0  5260.2    0.13       0  5411.0    0.08       0
Bank Sta=4979.5,5021.2
XS Rating Curve= 0
Exp/Cntr=0.3,0.1