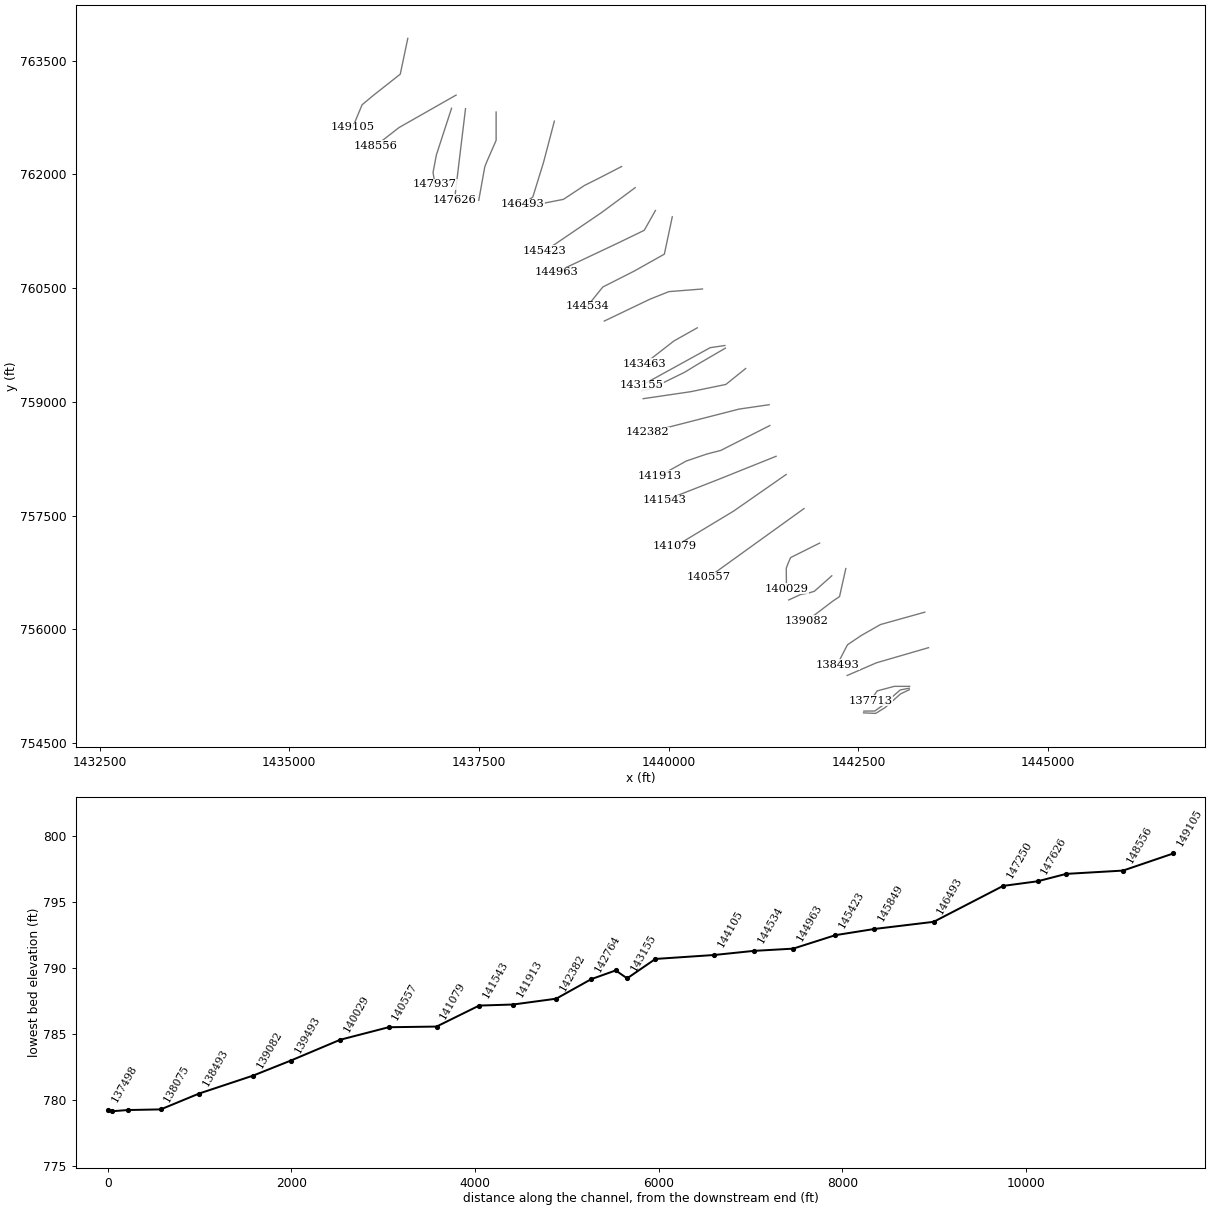
HEC-RAS study Fourth Creek.prj: Fourth Creek Detailed Study

--- Fourth Creek.g01 (geometry) --- (continued)

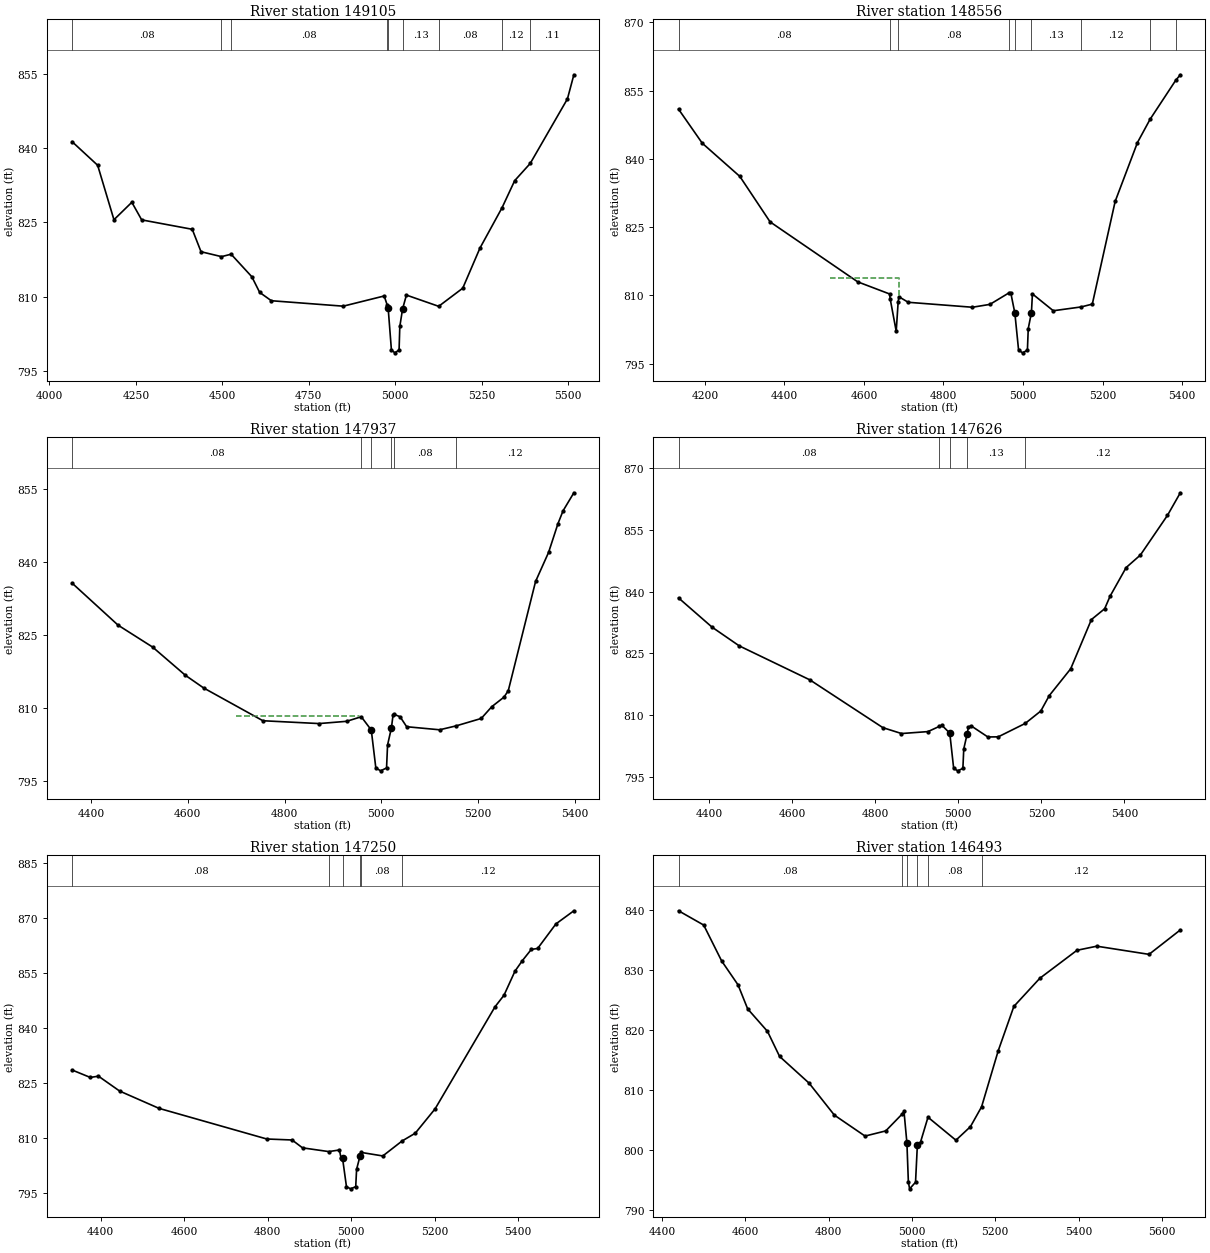
Type RM Length L Ch R = 1,149105,564,549,543
BEGIN DESCRIPTION:
Fourth Creek 241.0
END DESCRIPTION:
XS GIS Cut Line= 5
      1436562.38       763795.77      1436462.85       763323.01
      1436109.48       763044.30      1435960.18       762919.87
      1435835.77       762621.29
#Sta/Elev= 30
  4065.5  841.28  4139.5  836.51  4186.6  825.52  4238.3  829.04  4266.8  825.49
  4413.0  823.59  4438.4  819.06  4497.6  818.07  4525.4  818.56  4585.3  814.01
  4608.0  810.85  4641.7  809.17  4849.6  808.07  4968.1  810.13  4976.5  808.34
  4979.5  807.70  4988.9  799.25  4998.9  798.65  5011.1  799.25  5013.2  803.97
  5021.2  807.50  5032.3  810.31  5125.6  808.04  5195.2  811.70  5245.0  819.80
  5308.9  827.95  5345.4  833.41  5390.3  836.88  5497.9  849.91  5516.5  854.78
#Mann=9,-1,0
  4065.5    0.08       0  4497.6    9.99       0  4525.4    0.08       0
  4976.5    0.13       0  4979.5   0.042       0  5021.2    0.13       0
  5125.6    0.08       0  5308.9    0.12       0  5390.3    0.11       0
Bank Sta=4979.5,5021.2
XS Rating Curve= 0
Exp/Cntr=0.3,0.1

Type RM Length L Ch R = 1,148556,535,619,670
BEGIN DESCRIPTION:
Fourth Creek 240.0
END DESCRIPTION:
XS GIS Cut Line= 3
      1437198.44       763047.29      1436446.92       762619.27
      1436133.36       762375.39
#Sta/Elev= 30
  4133.6  850.90  4193.2  843.43  4287.8  836.12  4363.9  826.13  4584.3  812.95
  4664.4  810.29  4666.0  809.18  4681.1  802.09  4686.0  808.56  4687.8  809.68
  4711.3  808.46  4872.7  807.37  4916.8  808.00  4965.7  810.58  4969.1  810.60
  4979.5  806.09  4988.9  797.95  4998.9  797.35  5011.1  797.95  5013.2  802.67
  5021.2  806.20  5023.7  810.30  5076.2  806.60  5146.4  807.44  5174.3  808.06
  5231.8  830.63  5287.9  843.57  5319.7  848.69  5384.3  857.27  5395.7  858.46
#Mann=9,-1,0
  4133.6    0.08       0  4666.0    0.05       0  4686.0    0.08       0
  4965.7    0.13       0  4979.5   0.042       0  5021.2    0.13       0
  5146.4    0.12       0  5319.7    0.11       0  5384.3    0.12       0
#XS Ineff=1,-1
 4515.50 4688.00  813.70
Permanent Ineff=
       F
Bank Sta=4979.5,5021.2
XS Rating Curve= 0
Exp/Cntr=0.3,0.1

Type RM Length L Ch R = 1,147937,295,311,313
BEGIN DESCRIPTION:
Fourth Creek 239.0
END DESCRIPTION:
XS GIS Cut Line= 4
      1437138.71       762873.07      1436939.64       762260.93
      1436894.85       762027.01      1436919.73       761872.77
#Sta/Elev= 30
  4360.5  835.70  4455.7  827.05  4527.2  822.54  4595.1  816.73  4632.7  814.14
  4755.3  807.40  4871.4  806.82  4928.4  807.28  4958.8  808.22  4979.5  805.49
  4988.9  797.70  4998.9  797.10  5011.1  797.70  5013.2  802.42  5021.2  805.95
  5024.5  808.56  5026.3  808.73  5039.1  808.22  5052.7  806.17  5120.9  805.54
  5154.9  806.34  5207.0  807.87  5228.8  810.29  5254.0  812.25  5262.9  813.57
  5319.4  836.04  5346.3  842.01  5365.7  847.92  5376.3  850.57  5398.6  854.27
#Mann=6,-1,0
  4360.5    0.08       0  4958.8    0.13       0  4979.5   0.042       0
  5021.2    0.13       0  5026.3    0.08       0  5154.9    0.12       0
#XS Ineff=1,-1
 4699.20 4954.90  808.29
Permanent Ineff=
       F
Bank Sta=4979.5,5021.2
XS Rating Curve= 0
Exp/Cntr=0.3,0.1

Type RM Length L Ch R = 1,147626,379,376,357
BEGIN DESCRIPTION:
Fourth Creek 238.0
END DESCRIPTION:
XS GIS Cut Line= 3
      1437322.87       762868.14      1437243.24       762211.16
      1437178.54       761668.69
#Sta/Elev= 30
  4326.5  838.45  4407.1  831.37  4472.6  826.83  4642.8  818.58  4818.4  807.01
  4863.3  805.58  4927.0  806.05  4954.5  807.32  4960.4  807.59  4979.5  805.69
  4988.9  797.14  4998.9  796.54  5011.1  797.14  5013.2  801.86  5021.2  805.39
  5024.5  807.16  5030.8  807.45  5071.2  804.75  5096.2  804.78  5161.0  808.02
  5198.7  811.04  5219.1  814.78  5270.7  821.28  5320.5  833.20  5352.4  835.82
  5365.6  838.89  5404.1  845.80  5438.5  848.85  5503.6  858.45  5534.6  863.93
#Mann=5,-1,0
  4326.5    0.08       0  4954.5    0.13       0  4979.5   0.042       0
  5021.2    0.13       0  5161.0    0.12       0
Bank Sta=4979.5,5021.2
XS Rating Curve= 0
Exp/Cntr=0.3,0.1

Type RM Length L Ch R = 1,147250,747,757,758
BEGIN DESCRIPTION:
Fourth Creek 237.0
END DESCRIPTION:
XS GIS Cut Line= 5
      1437726.00       762823.33      1437726.00       762450.05
      1437606.55       762176.32      1437576.69       762101.66
      1437497.06       761658.71
#Sta/Elev= 30
  4331.4  828.57  4375.1  826.54  4394.6  826.89  4445.4  822.83  4539.7  818.12
  4798.0  809.77  4858.6  809.50  4883.6  807.36  4946.5  806.34  4972.1  806.78
  4975.7  804.66  4979.5  804.54  4988.9  796.79  4998.9  796.19  5011.1  796.79
  5013.2  801.51  5021.2  805.04  5024.7  806.10  5076.0  805.15  5122.1  809.22
  5153.8  811.35  5201.4  818.00  5344.8  845.78  5366.4  848.94  5392.8  855.52
  5410.5  858.38  5431.8  861.42  5447.0  861.68  5490.8  868.37  5533.8  871.95
#Mann=6,-1,0
  4331.4    0.08       0  4946.5    0.13       0  4979.5   0.042       0
  5021.2    0.13       0  5024.7    0.08       0  5122.1    0.12       0
Bank Sta=4979.5,5021.2
XS Rating Curve= 0
Exp/Cntr=0.3,0.1

Type RM Length L Ch R = 1,146493,707,644,567
BEGIN DESCRIPTION:
Fourth Creek 236.0
END DESCRIPTION:
XS GIS Cut Line= 4
      1438493.44       762703.85      1438351.21       762162.01
      1438209.76       761703.51      1438075.41       761608.96
#Sta/Elev= 30
  4439.8  839.79  4500.2  837.41  4543.2  831.44  4582.6  827.45  4605.7  823.45
  4653.3  819.70  4682.3  815.53  4753.1  811.08  4813.8  805.75  4887.4  802.26
  4937.1  803.12  4976.2  805.91  4980.9  806.37  4987.9  801.12  4991.4  794.60
  4994.4  793.47  5008.6  794.57  5013.0  800.78  5020.6  801.26  5038.5  805.40
  5105.5  801.57  5140.4  803.83  5167.1  807.13  5207.1  816.48  5244.6  823.86
  5306.8  828.54  5396.1  833.21  5443.6  833.89  5569.0  832.53  5644.1  836.60
#Mann=6,-1,0
  4439.8    0.08       0  4976.2    0.13       0  4987.9   0.042       0
  5013.0    0.13       0  5038.5    0.08       0  5167.1    0.12       0
Bank Sta=4987.9,5013
XS Rating Curve= 0
Exp/Cntr=0.3,0.1

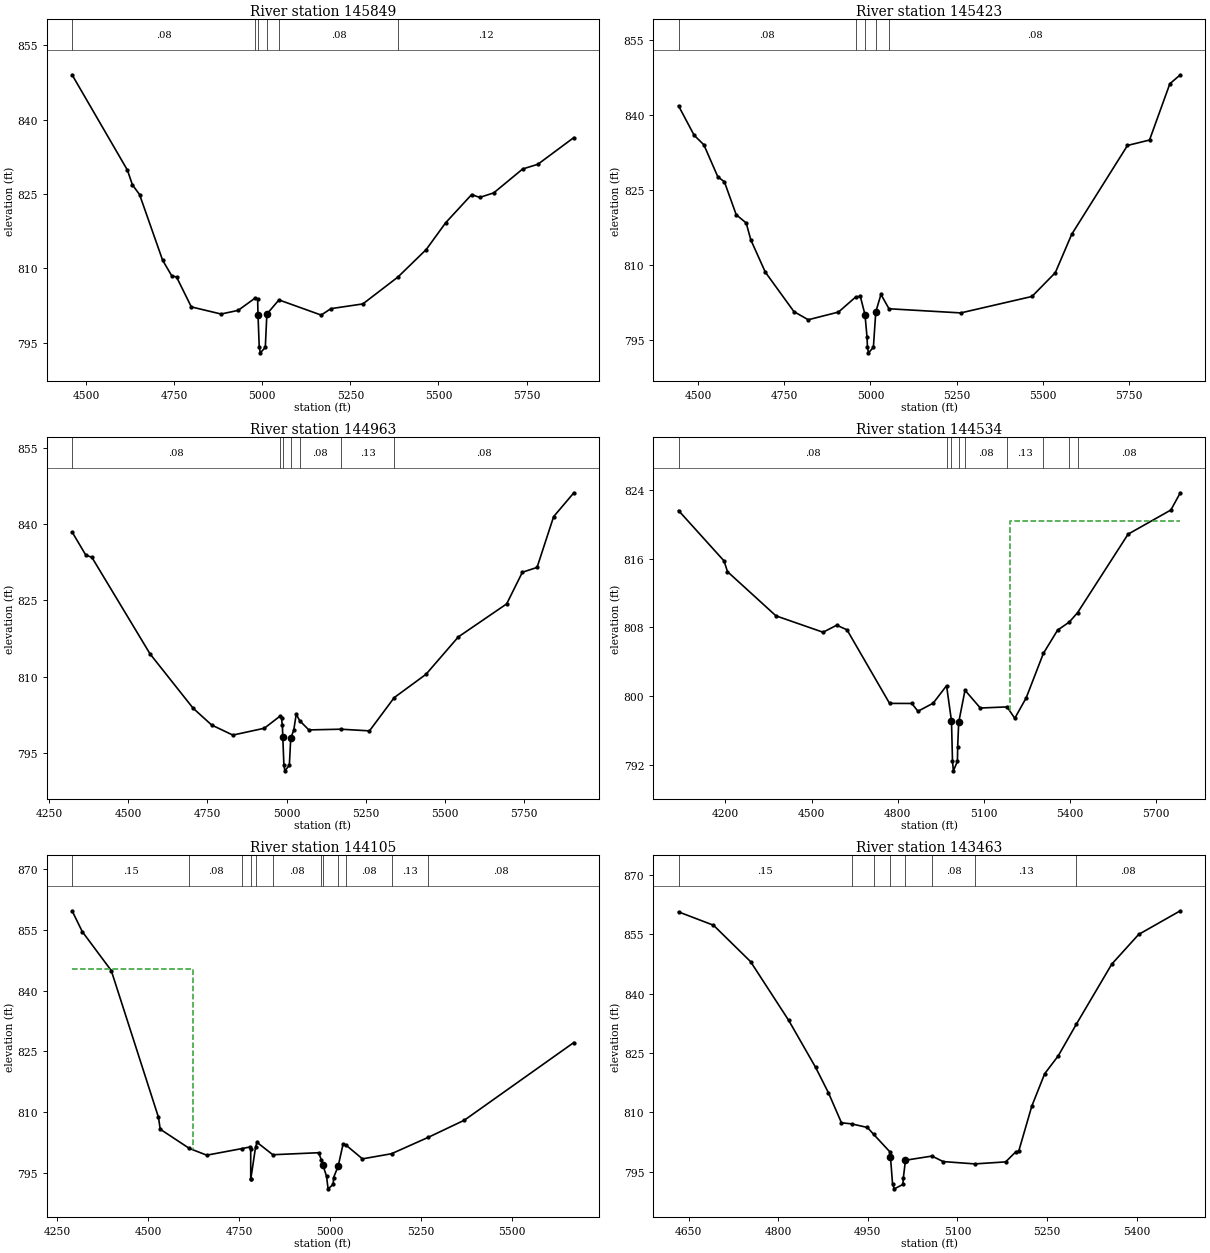
Type RM Length L Ch R = 1,145849,409,426,427
BEGIN DESCRIPTION:
Fourth Creek 235.0
END DESCRIPTION:
XS GIS Cut Line= 5
      1439379.35       762105.15      1439070.78       761945.88
      1438891.61       761856.30      1438612.90       761672.15
      1438080.38       761567.64
#Sta/Elev= 30
  4460.1  849.04  4617.2  829.80  4631.4  826.83  4651.6  824.88  4717.0  811.64
  4743.1  808.46  4756.6  808.24  4798.6  802.20  4883.0  800.76  4931.5  801.50
  4980.0  804.00  4986.8  803.79  4987.9  800.55  4991.4  794.06  4994.4  792.93
  5008.6  794.03  5013.0  800.75  5047.3  803.61  5167.2  800.55  5194.9  801.85
  5285.5  802.80  5385.1  808.23  5465.4  813.78  5520.5  819.18  5594.3  824.87
  5617.1  824.29  5657.0  825.21  5739.1  830.03  5782.2  830.98  5884.4  836.37
#Mann=6,-1,0
  4460.1    0.08       0  4980.0    0.13       0  4987.9   0.042       0
  5013.0    0.13       0  5047.3    0.08       0  5385.1    0.12       0
Bank Sta=4987.9,5013
XS Rating Curve= 0
Exp/Cntr=0.3,0.1

Type RM Length L Ch R = 1,145423,476,460,435
BEGIN DESCRIPTION:
Fourth Creek 234.0
END DESCRIPTION:
XS GIS Cut Line= 3
      1439558.49       761826.42      1439115.57       761497.96
      1438369.04       760990.32
#Sta/Elev= 30
  4443.9  841.89  4489.1  836.00  4517.3  834.09  4557.8  827.68  4576.8  826.69
  4611.1  820.09  4639.9  818.45  4653.4  815.06  4695.3  808.62  4778.3  800.71
  4819.8  799.08  4907.4  800.62  4956.9  803.61  4970.6  803.80  4984.3  800.08
  4990.2  795.55  4991.4  793.59  4994.4  792.46  5008.6  793.56  5015.5  800.64
  5030.5  804.15  5053.8  801.28  5261.8  800.45  5468.2  803.74  5535.8  808.50
  5583.4  816.19  5745.0  833.96  5808.8  835.04  5867.7  846.30  5898.1  848.10
#Mann=5,-1,0
  4443.9    0.08       0  4956.9    0.13       0  4984.3   0.042       0
  5015.5    0.13       0  5053.8    0.08       0
Bank Sta=4984.3,5015.5
XS Rating Curve= 0
Exp/Cntr=0.3,0.1

Type RM Length L Ch R = 1,144963,420,429,435
BEGIN DESCRIPTION:
Fourth Creek 233.0
END DESCRIPTION:
XS GIS Cut Line= 4
      1439825.00       761524.99      1439677.97       761264.04
      1439339.53       761099.80      1438518.37       760711.61
#Sta/Elev= 30
  4322.7  838.49  4366.2  833.91  4385.1  833.50  4569.1  814.45  4704.7  803.78
  4763.2  800.47  4830.2  798.48  4929.6  799.83  4978.3  802.17  4983.9  801.79
  4986.6  800.37  4987.9  798.08  4991.4  792.57  4994.4  791.44  5008.6  792.54
  5013.0  797.88  5022.5  799.47  5030.3  802.60  5041.3  801.31  5070.1  799.50
  5171.3  799.64  5261.5  799.31  5339.6  805.86  5439.9  810.45  5542.1  817.82
  5694.6  824.32  5744.2  830.55  5790.5  831.50  5842.9  841.51  5906.7  846.20
#Mann=7,-1,0
  4322.7    0.08       0  4978.3    0.13       0  4987.9   0.042       0
  5013.0    0.13       0  5041.3    0.08       0  5171.3    0.13       0
  5339.6    0.08       0
Bank Sta=4987.9,5013
XS Rating Curve= 0
Exp/Cntr=0.3,0.1

Type RM Length L Ch R = 1,144534,439,429,425
BEGIN DESCRIPTION:
Fourth Creek 232.0
END DESCRIPTION:
XS GIS Cut Line= 5
      1440047.27       761442.26      1439942.74       760949.50
      1439544.58       760725.53      1439131.78       760516.09
      1438927.43       760262.67
#Sta/Elev= 30
  4036.5  821.60  4195.1  815.73  4207.1  814.48  4376.1  809.33  4540.2  807.42
  4588.0  808.24  4623.7  807.70  4772.1  799.13  4849.7  799.12  4870.9  798.21
  4923.9  799.15  4970.7  801.19  4987.9  797.08  4991.4  792.40  4994.4  791.27
  5008.6  792.37  5009.4  794.03  5013.0  796.91  5035.0  800.66  5088.4  798.59
  5181.6  798.72  5208.4  797.39  5248.2  799.77  5308.1  804.95  5357.8  807.67
  5398.3  808.60  5427.2  809.69  5603.5  818.85  5752.4  821.66  5785.5  823.67
#Mann=9,-1,0
  4036.5    0.08       0  4970.7    0.13       0  4987.9   0.042       0
  5013.0    0.13       0  5035.0    0.08       0  5181.6    0.13       0
  5308.1    0.08       0  5398.3    0.13       0  5427.2    0.08       0
#XS Ineff=2,0
       0                 5191.30    0.00  820.33
Permanent Ineff=
       F       F
Bank Sta=4987.9,5013
XS Rating Curve= 0
Exp/Cntr=0.3,0.1

Type RM Length L Ch R = 1,144105,629,642,660
BEGIN DESCRIPTION:
Fourth Creek 231.0
END DESCRIPTION:
XS GIS Cut Line= 4
      1440445.39       760490.12      1440002.46       760455.28
      1439753.62       760355.74      1439151.43       760067.09
#Sta/Elev= 30
  4290.3  859.77  4318.3  854.62  4398.1  844.97  4528.0  808.64  4532.7  805.72
  4612.9  800.96  4660.7  799.29  4757.4  800.92  4780.7  801.34  4781.6  800.73
  4781.7  793.28  4782.0  793.46  4795.0  801.30  4799.0  802.46  4842.5  799.40
  4968.6  799.90  4975.5  798.21  4980.4  796.79  4990.2  794.05  4994.4  790.96
  5008.6  792.06  5009.4  793.72  5022.3  796.60  5035.5  801.99  5042.4  801.88
  5089.0  798.38  5169.0  799.65  5270.3  803.72  5369.3  807.95  5670.4  827.17
#Mann=12,-1,0
  4290.3    0.15       0  4612.9    0.08       0  4757.4    0.13       0
  4782.0    0.05       0  4795.0    0.13       0  4842.5    0.08       0
  4975.5    0.13       0  4980.4   0.042       0  5022.3    0.13       0
  5042.4    0.08       0  5169.0    0.13       0  5270.3    0.08       0
#XS Ineff=2,0
    0.00 4624.10  845.42               0
Permanent Ineff=
       F       F
Bank Sta=4980.4,5022.3
XS Rating Curve= 0
Exp/Cntr=0.3,0.1

Type RM Length L Ch R = 1,143463,310,308,294
BEGIN DESCRIPTION:
Fourth Creek 230.0
END DESCRIPTION:
XS GIS Cut Line= 3
      1440375.78       759977.52      1440067.16       759803.30
      1439683.96       759504.70
#Sta/Elev= 30
  4633.0  860.63  4691.5  857.26  4753.6  848.07  4817.5  833.21  4862.5  821.35
  4884.1  814.90  4905.8  807.35  4923.0  807.07  4949.3  806.16  4959.8  804.41
  4987.4  799.92  4987.9  798.66  4991.4  791.79  4994.4  790.66  5008.6  791.76
  5009.4  793.42  5013.0  797.89  5057.4  798.94  5076.0  797.55  5129.2  796.96
  5180.7  797.47  5197.8  800.02  5202.6  800.17  5224.5  811.55  5246.1  819.75
  5268.8  824.26  5298.9  832.21  5358.4  847.43  5403.4  854.93  5473.2  860.91
#Mann=8,-1,0
  4633.0    0.15       0  4923.0    0.08       0  4959.8    0.13       0
  4987.9   0.042       0  5013.0    0.13       0  5057.4    0.08       0
  5129.2    0.13       0  5298.9    0.08       0
Bank Sta=4987.9,5013
XS Rating Curve= 0
Exp/Cntr=0.5,0.3

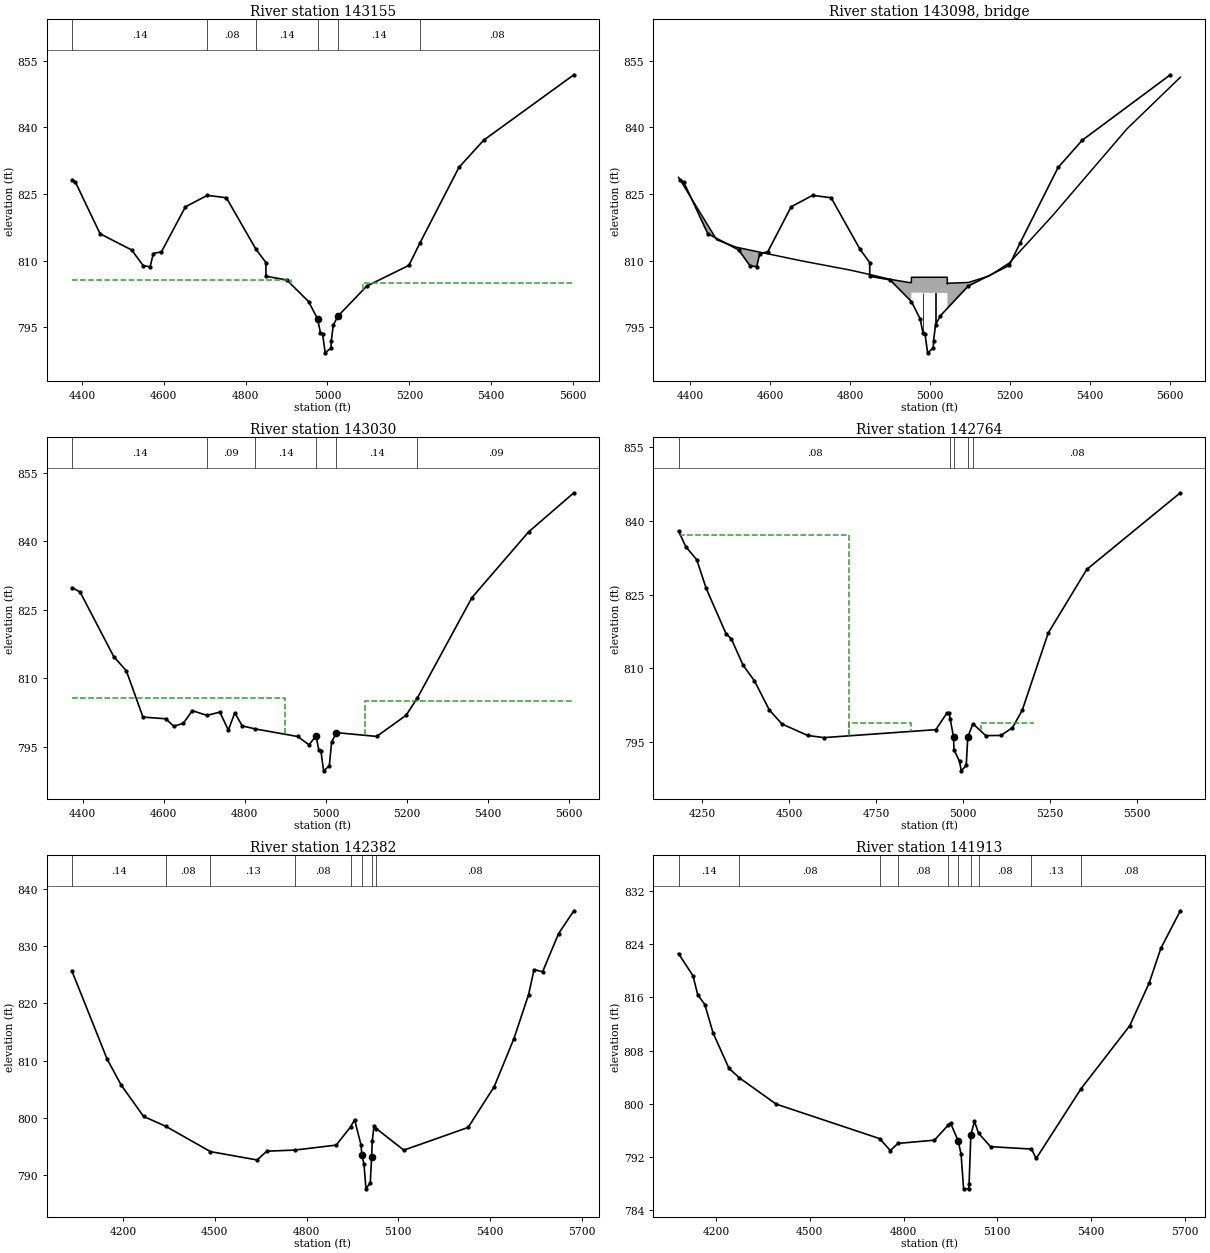
Type RM Length L Ch R = 1,143155,121,125,132
BEGIN DESCRIPTION:
Fort Dobbs Rd (FC) us
END DESCRIPTION:
XS GIS Cut Line= 3
      1440740.42       759744.59      1440546.15       759715.93
      1439644.71       759219.02
#Sta/Elev= 30
  4376.1  828.07  4384.3  827.67  4444.5  816.03  4521.6  812.38  4550.0  808.84
  4566.7  808.59  4574.6  811.58  4594.5  811.97  4653.0  822.11  4706.5  824.69
  4753.0  824.15  4825.3  812.53  4849.6  809.55  4849.7  806.45  4900.5  805.63
  4953.9  800.74  4975.8  796.85  4982.7  793.71  4987.9  793.50  4994.4  789.19
  5008.6  790.29  5009.4  791.95  5014.3  795.51  5026.3  797.54  5095.9  804.23
  5198.9  808.91  5225.8  813.95  5321.0  830.98  5381.3  837.11  5601.8  851.87
#Mann=6,-1,0
  4376.1    0.14       0  4706.5    0.08       0  4825.3    0.14       0
  4975.8   0.045       0  5026.3    0.14       0  5225.8    0.08       0
#XS Ineff=2,0
    0.00 4909.70  805.63 5087.90    0.00  805.03
Permanent Ineff=
       F       F
Bank Sta=4975.8,5026.3
XS Rating Curve= 0
Exp/Cntr=0.5,0.3

Type RM Length L Ch R =3,143098,,,
BEGIN DESCRIPTION:
Fort Dobbs Rd (FC) TOR
Structure ID: I_FC_15
Detailed Survey Structure
END DESCRIPTION:
Bridge Culvert--1,0,-1,-1,0
Deck Dist Width WeirC Skew NumUp NumDn MinLoCord MaxHiCord MaxSubmerge Is_Ogee
44,26,3,,25,25,,,,0,1,1,,,
  4371.2  4466.7  4515.7  4679.1  4799.9  4849.7  4899.9  4950.4  4953.7  4953.7
  4953.9  4953.9  4954.0  5043.5  5043.9  5043.9  5044.0  5044.0  5048.6  5096.9
  5148.9  5198.7  5306.8  5493.6  5626.8
  828.77  814.67  813.00  809.92  807.86  806.85  805.78  805.01  805.04  805.04
  805.04  805.20  806.22  806.23  805.00  805.00  804.69  804.93  804.89  805.06
  806.53  809.44  820.08  839.71  851.31
  769.19  769.19  769.19  769.19  769.19  769.19  769.19  769.19  769.19  802.78
  802.78  802.78  802.78  802.68  802.68  769.19  769.19  769.19  769.19  769.19
  769.19  769.19  769.19  769.19  769.19
  4371.2  4466.7  4515.7  4679.1  4799.9  4849.7  4899.9  4950.4  4953.7  4953.7
  4953.9  4953.9  4954.0  5043.5  5043.9  5043.9  5044.0  5044.0  5048.6  5096.9
  5148.9  5198.7  5306.8  5493.6  5626.8
  828.77  814.67  813.00  809.92  807.86  806.85  805.78  805.01  805.04  805.04
  805.04  805.20  806.22  806.23  805.00  805.00  804.69  804.93  804.89  805.06
  806.53  809.44  820.08  839.71  851.31
  769.19  769.19  769.19  769.19  769.19  769.19  769.19  769.19  769.19  802.78
  802.78  802.78  802.78  802.68  802.68  769.19  769.19  769.19  769.19  769.19
  769.19  769.19  769.19  769.19  769.19
Pier Skew, UpSta & Num, DnSta & Num=,4982.7,2,4982.7,2,0,0,0,0,0
     0.8     0.8
  793.71  802.75
     0.8     0.8
  794.31  802.75
Pier Skew, UpSta & Num, DnSta & Num=,5014.3,2,5014.3,2,0,0,0,0,0
     0.8     0.8
  795.51  802.71
     0.8     0.8
  796.11  802.71
BR Coef=1,1,0,1.25,0,,,0.8,0,2,0,
WSPro=,,,, 1 ,,,, 0 ,,,, 0 ,,,,-1 ,-1 ,-1 , 0 , 0 , 0 , 0 , 0
BC Design=,,0,,0,,,,,,

Type RM Length L Ch R = 1,143030,328,266,254
BEGIN DESCRIPTION:
Fort Dobbs Rd (FC) ds
END DESCRIPTION:
XS GIS Cut Line= 5
      1440746.83       759709.56      1440380.51       759496.14
      1440208.51       759391.03      1439758.30       759170.28
      1439647.93       759152.14
#Sta/Elev= 30
  4373.5  829.85  4393.2  828.89  4476.3  814.78  4507.6  811.63  4548.5  801.54
  4605.0  801.17  4624.5  799.53  4648.0  800.17  4670.3  802.94  4706.5  801.91
  4738.4  802.63  4759.3  798.69  4775.2  802.47  4793.7  799.61  4825.3  798.96
  4930.1  797.30  4958.7  795.48  4975.8  797.45  4982.7  794.31  4987.9  794.10
  4994.4  789.79  5008.6  790.89  5014.3  796.11  5026.3  798.14  5125.6  797.31
  5197.8  801.91  5225.8  805.68  5360.7  827.66  5500.4  842.00  5612.3  850.57
#Mann=6,-1,0
  4373.5    0.14       0  4706.5    0.09       0  4825.3    0.14       0
  4975.8   0.045       0  5026.3    0.14       0  5225.8    0.09       0
#XS Ineff=2,0
    0.00 4899.70  805.78 5097.90    0.00  805.09
Permanent Ineff=
       F       F
Bank Sta=4975.8,5026.3
XS Rating Curve= 0
Exp/Cntr=0.5,0.3

Type RM Length L Ch R = 1,142764,377,382,392
BEGIN DESCRIPTION:
Fourth Creek 228.0
END DESCRIPTION:
XS GIS Cut Line= 4
      1441014.41       759441.38      1440753.19       759231.13
      1440291.33       759135.57      1439663.85       759043.20
#Sta/Elev= 30
  4182.3  837.91  4203.2  834.73  4234.7  832.07  4261.8  826.23  4318.8  817.02
  4333.8  816.00  4367.7  810.62  4400.4  807.43  4442.8  801.54  4479.5  798.65
  4553.5  796.32  4600.0  795.89  4921.3  797.51  4953.3  800.91  4959.5  800.86
  4962.8  799.59  4972.2  795.99  4973.3  793.46  4989.3  791.05  4994.4  789.13
  5008.6  790.23  5013.0  795.99  5027.8  798.72  5064.5  796.30  5108.0  796.33
  5141.4  797.90  5169.4  801.45  5244.0  817.16  5354.7  830.10  5623.5  845.70
#Mann=5,-1,0
  4182.3    0.08       0  4962.8    0.13       0  4972.2   0.042       0
  5013.0    0.13       0  5027.8    0.08       0
#XS Ineff=3,-1
 4158.90 4671.20  837.20 4671.30 4849.40  798.92 5051.20 5202.00  798.92
Permanent Ineff=
       F       F       F
Bank Sta=4972.2,5013
XS Rating Curve= 0
Exp/Cntr=0.3,0.1

Type RM Length L Ch R = 1,142382,472,469,482
BEGIN DESCRIPTION:
Fourth Creek 227.5
END DESCRIPTION:
XS GIS Cut Line= 3
      1441323.33       758963.56      1440928.38       758906.23
      1439724.47       758597.30
#Sta/Elev= 30
  4032.7  825.59  4147.2  810.31  4193.0  805.79  4266.7  800.28  4339.3  798.56
  4485.6  794.14  4638.1  792.69  4670.1  794.22  4761.0  794.41  4897.0  795.28
  4944.1  798.46  4957.2  799.71  4978.0  795.35  4981.2  793.50  4987.9  791.96
  4994.4  787.65  5008.6  788.75  5013.0  793.29  5014.8  795.92  5020.9  798.67
  5028.2  798.17  5118.3  794.40  5328.7  798.36  5414.2  805.49  5478.5  813.85
  5526.6  821.55  5544.4  825.91  5572.4  825.52  5624.8  832.19  5674.7  836.16
#Mann=8,-1,0
  4032.7    0.14       0  4339.3    0.08       0  4485.6    0.13       0
  4761.0    0.08       0  4944.1    0.13       0  4981.2   0.042       0
  5013.0    0.13       0  5028.2    0.08       0
Bank Sta=4981.2,5013
XS Rating Curve= 0
Exp/Cntr=0.3,0.1

Type RM Length L Ch R = 1,141913,353,370,373
BEGIN DESCRIPTION:
Fourth Creek 227.0
END DESCRIPTION:
XS GIS Cut Line= 5
      1441332.23       758688.66      1440685.66       758360.60
      1440500.92       758312.82      1440230.17       758220.45
      1439876.62       758022.97
#Sta/Elev= 30
  4079.5  822.58  4126.0  819.23  4140.9  816.39  4163.7  814.92  4189.9  810.68
  4241.0  805.33  4274.3  803.90  4392.1  799.95  4723.6  794.76  4757.6  792.97
  4782.3  794.04  4899.0  794.53  4942.3  796.75  4950.7  797.09  4974.6  794.46
  4984.2  792.48  4992.3  787.24  5008.4  787.21  5010.0  788.01  5015.6  795.35
  5027.2  797.37  5040.1  795.59  5078.7  793.55  5209.8  793.19  5224.9  791.78
  5368.8  802.29  5524.3  811.73  5586.7  818.17  5623.9  823.36  5686.4  829.02
#Mann=10,-1,0
  4079.5    0.14       0  4274.3    0.08       0  4723.6    0.13       0
  4782.3    0.08       0  4942.3    0.13       0  4974.6   0.042       0
  5015.6    0.13       0  5040.1    0.08       0  5209.8    0.13       0
  5368.8    0.08       0
Bank Sta=4974.6,5015.6
XS Rating Curve= 0
Exp/Cntr=0.3,0.1

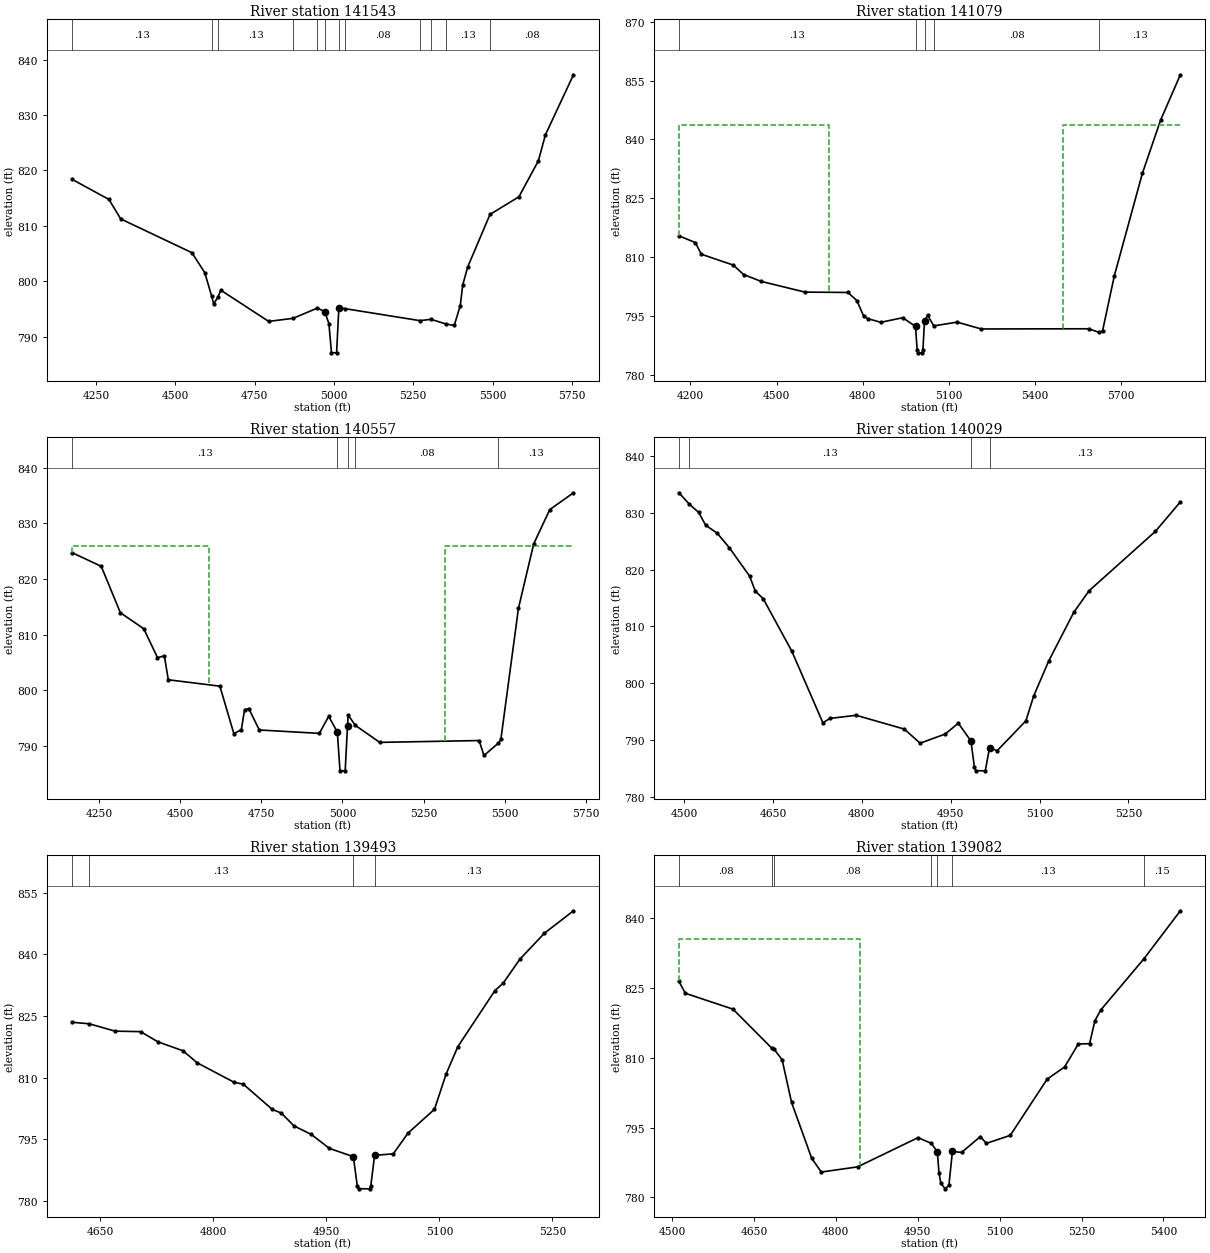
Type RM Length L Ch R = 1,141543,442,464,505
BEGIN DESCRIPTION:
Fourth Creek 226.0
END DESCRIPTION:
XS GIS Cut Line= 3
      1441415.06       758283.50      1440653.81       757977.73
      1439946.64       757700.60
#Sta/Elev= 30
  4174.9  818.41  4291.3  814.77  4328.2  811.27  4552.6  805.18  4593.0  801.59
  4615.0  797.30  4621.2  795.95  4634.0  797.13  4643.7  798.42  4794.3  792.80
  4871.6  793.35  4947.7  795.20  4971.1  794.55  4984.2  792.40  4992.3  787.16
  5008.4  787.13  5015.6  795.27  5035.6  795.09  5271.3  792.93  5305.7  793.17
  5354.2  792.31  5379.1  792.07  5398.1  795.63  5405.7  799.33  5421.6  802.62
  5491.8  812.08  5582.9  815.26  5644.2  821.74  5666.6  826.47  5754.8  837.25
#Mann=12,-1,0
  4174.9    0.13       0  4615.0    0.05       0  4634.0    0.13       0
  4871.6    0.08       0  4947.7    0.13       0  4971.1   0.042       0
  5015.6    0.13       0  5035.6    0.08       0  5271.3    0.13       0
  5305.7    0.08       0  5354.2    0.13       0  5491.8    0.08       0
Bank Sta=4971.1,5015.6
XS Rating Curve= 0
Exp/Cntr=0.3,0.1

Type RM Length L Ch R = 1,141079,515,522,540
BEGIN DESCRIPTION:
Fourth Creek 225.0
END DESCRIPTION:
XS GIS Cut Line= 3
      1441547.63       758043.37      1440853.21       757559.19
      1440082.38       757094.14
#Sta/Elev= 30
  4160.0  815.39  4217.2  813.67  4237.9  810.70  4349.5  807.92  4385.4  805.51
  4447.2  803.75  4599.5  801.03  4748.7  800.94  4780.0  798.87  4803.5  794.92
  4817.9  794.26  4863.5  793.33  4939.8  794.50  4984.2  792.28  4990.0  786.27
  4992.3  785.57  5008.4  785.54  5010.0  786.34  5015.6  793.68  5026.3  795.13
  5047.9  792.42  5129.3  793.37  5213.1  791.63  5587.0  791.68  5624.5  790.74
  5635.7  791.11  5676.8  805.18  5774.5  831.32  5838.0  844.90  5906.8  856.47
#Mann=5,-1,0
  4160.0    0.13       0  4984.2   0.042       0  5015.6    0.13       0
  5047.9    0.08       0  5624.5    0.13       0
#XS Ineff=2,0
    0.00 4682.70  843.74 5499.00    0.00  843.74
Permanent Ineff=
       F       F
Bank Sta=4984.2,5015.6
XS Rating Curve= 0
Exp/Cntr=0.3,0.1

Type RM Length L Ch R = 1,140557,452,528,632
BEGIN DESCRIPTION:
Fourth Creek 224.0
END DESCRIPTION:
XS GIS Cut Line= 3
      1441783.28       757594.21      1441111.21       757110.07
      1440528.32       756689.62
#Sta/Elev= 30
  4165.7  824.74  4255.8  822.28  4314.8  813.93  4386.8  811.06  4429.3  805.86
  4450.5  806.17  4462.6  801.87  4621.8  800.72  4664.9  792.18  4688.0  792.89
  4697.9  796.48  4711.0  796.69  4743.4  792.84  4928.6  792.23  4957.5  795.29
  4984.2  792.45  4992.3  785.52  5008.4  785.49  5015.6  793.63  5017.6  795.54
  5039.3  793.69  5114.9  790.61  5421.6  790.94  5436.6  788.25  5481.2  790.48
  5488.7  791.15  5542.9  814.71  5589.8  826.29  5639.5  832.48  5712.7  835.51
#Mann=5,-1,0
  4165.7    0.13       0  4984.2   0.042       0  5015.6    0.13       0
  5039.3    0.08       0  5481.2    0.13       0
#XS Ineff=2,0
    0.00 4589.50  825.97 5317.60    0.00  825.97
Permanent Ineff=
       F       F
Bank Sta=4984.2,5015.6
XS Rating Curve= 0
Exp/Cntr=0.3,0.1

Type RM Length L Ch R = 1,140029,570,536,503
BEGIN DESCRIPTION:
Fourth Creek 223.0
END DESCRIPTION:
XS GIS Cut Line= 5
      1441988.45       757138.43      1441606.20       756947.30
      1441574.35       756874.04      1441548.87       756807.15
      1441552.05       756539.60
#Sta/Elev= 30
  4491.3  833.54  4508.9  831.53  4524.7  830.07  4536.5  827.82  4555.8  826.43
  4576.2  823.89  4610.5  818.87  4620.2  816.22  4633.7  814.85  4681.8  805.64
  4734.3  793.01  4746.3  793.78  4790.4  794.33  4871.7  791.90  4898.5  789.41
  4940.7  791.02  4962.9  792.93  4984.2  789.81  4990.0  785.27  4992.3  784.57
  5008.4  784.54  5015.6  788.59  5028.5  788.09  5076.9  793.34  5090.3  797.77
  5115.3  803.85  5157.9  812.49  5183.6  816.27  5295.6  826.74  5337.7  831.93
#Mann=4,-1,0
  4491.3    0.08       0  4508.9    0.13       0  4984.2   0.042       0
  5015.6    0.13       0
Bank Sta=4984.2,5015.6
XS Rating Curve= 0
Exp/Cntr=0.3,0.1

Type RM Length L Ch R = 1,139493,436,411,396
BEGIN DESCRIPTION:
Fourth Creek 222.0
END DESCRIPTION:
XS GIS Cut Line= 5
      1442148.94       756707.10      1441919.63       756503.28
      1441842.37       756479.62      1441741.26       756461.87
      1441581.96       756388.59
#Sta/Elev= 30
  4612.4  823.49  4635.2  823.12  4669.5  821.33  4703.4  821.21  4726.5  818.72
  4759.7  816.55  4778.5  813.63  4827.8  808.86  4839.6  808.45  4878.2  802.29
  4890.2  801.40  4907.0  798.28  4929.9  796.21  4954.1  792.80  4985.8  790.80
  4991.0  783.70  4993.1  783.00  5007.6  782.97  5009.0  783.77  5014.0  791.11
  5038.8  791.49  5058.3  796.52  5093.5  802.32  5109.0  810.93  5124.6  817.59
  5173.7  831.19  5184.7  833.01  5207.0  838.86  5239.5  845.16  5278.0  850.61
#Mann=4,-1,0
  4612.4    0.08       0  4635.2    0.13       0  4985.8   0.042       0
  5014.0    0.13       0
Bank Sta=4985.8,5014
XS Rating Curve= 0
Exp/Cntr=0.3,0.1

Type RM Length L Ch R = 1,139082,645,589,585
BEGIN DESCRIPTION:
Fourth Creek 221.0
END DESCRIPTION:
XS GIS Cut Line= 4
      1442333.71       756802.66      1442250.90       756433.20
      1442161.71       756372.68      1441817.73       756111.51
#Sta/Elev= 30
  4512.6  826.43  4524.4  823.88  4611.7  820.46  4683.3  812.01  4686.3  811.95
  4701.6  809.59  4718.9  800.41  4755.7  788.42  4773.3  785.44  4839.7  786.55
  4950.5  792.84  4975.0  791.60  4985.9  789.78  4988.8  785.31  4992.3  783.01
  5000.3  781.83  5007.0  782.56  5013.5  789.87  5030.3  789.66  5064.7  793.07
  5075.6  791.60  5119.5  793.34  5186.9  805.41  5218.8  808.02  5244.1  812.98
  5264.6  813.04  5274.6  818.02  5285.2  820.29  5364.3  831.31  5430.9  841.62
#Mann=7,-1,0
  4512.6    0.08       0  4683.3    0.13       0  4686.3    0.08       0
  4975.0    0.13       0  4985.9   0.045       0  5013.5    0.13       0
  5364.3    0.15       0
#XS Ineff=2,0
    0.00 4844.70  835.46               0
Permanent Ineff=
       F       F
Bank Sta=4985.9,5013.5
XS Rating Curve= 0
Exp/Cntr=0.3,0.1

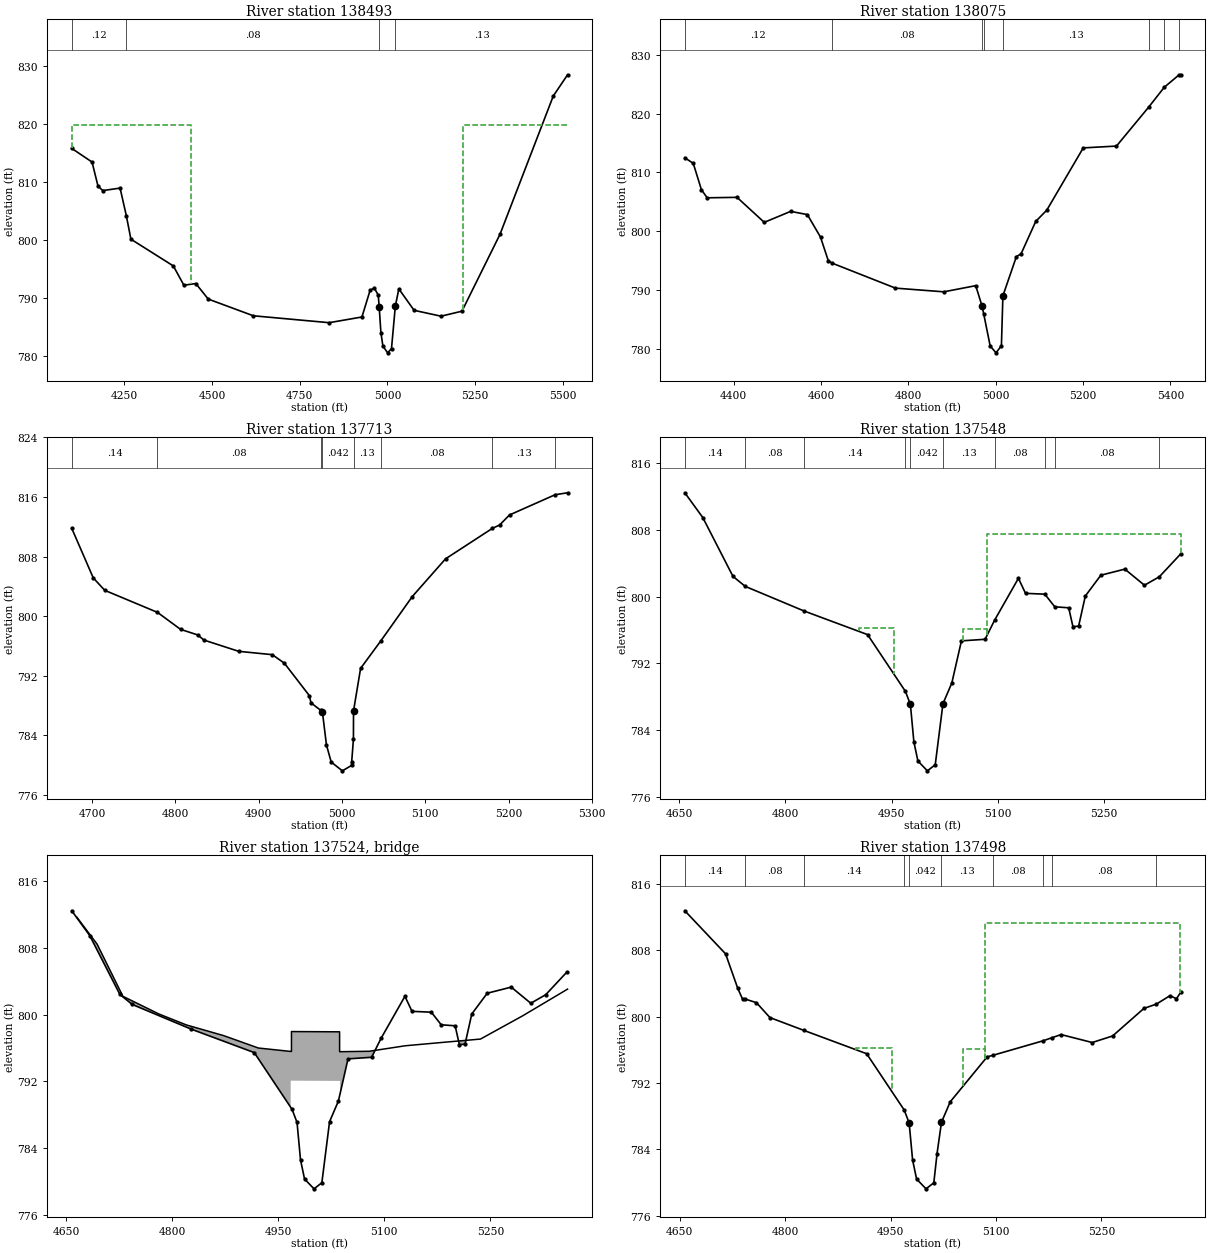
Type RM Length L Ch R = 1,138493,452,418,428
BEGIN DESCRIPTION:
Fourth Creek 220.0
END DESCRIPTION:
XS GIS Cut Line= 5
      1443374.41       756227.63      1442790.86       756064.54
      1442535.82       755919.12      1442355.12       755796.98
      1442220.05       755534.50
#Sta/Elev= 30
  4100.5  815.72  4158.3  813.37  4175.3  809.21  4188.9  808.45  4238.2  808.88
  4256.0  804.11  4269.0  800.07  4390.0  795.45  4420.0  792.13  4454.0  792.42
  4489.4  789.74  4617.9  786.86  4834.0  785.67  4927.3  786.65  4950.8  791.29
  4962.8  791.62  4973.8  790.43  4976.5  788.42  4981.4  783.95  4987.1  781.65
  5000.5  780.47  5011.6  781.20  5022.5  788.51  5032.5  791.50  5076.0  787.80
  5152.7  786.79  5212.3  787.65  5320.7  800.90  5472.6  824.76  5513.3  828.42
#Mann=4,-1,0
  4100.5    0.12       0  4256.0    0.08       0  4976.5   0.042       0
  5022.5    0.13       0
#XS Ineff=2,0
    0.00 4439.80  819.81 5214.50    0.00  819.81
Permanent Ineff=
       F       F
Bank Sta=4976.5,5022.5
XS Rating Curve= 0
Exp/Cntr=0.3,0.1

Type RM Length L Ch R = 1,138075,371,362,359
BEGIN DESCRIPTION:
Fourth Creek 219.0
END DESCRIPTION:
XS GIS Cut Line= 3
      1443423.79       755759.40      1442736.84       755559.64
      1442351.55       755392.47
#Sta/Elev= 30
  4287.9  812.48  4307.2  811.54  4325.9  807.04  4339.1  805.67  4407.4  805.75
  4469.8  801.49  4530.3  803.36  4568.5  802.81  4598.6  798.98  4616.4  794.96
  4625.0  794.55  4770.2  790.29  4881.0  789.66  4954.1  790.71  4968.6  787.22
  4972.4  785.89  4987.1  780.45  5000.5  779.27  5012.9  780.48  5016.3  788.98
  5047.2  795.66  5057.9  796.13  5091.5  801.65  5116.8  803.57  5200.3  814.17
  5276.4  814.48  5350.0  821.10  5385.8  824.49  5419.3  826.58  5423.3  826.62
#Mann=8,-1,0
  4287.9    0.12       0  4625.0    0.08       0  4968.6   0.042       0
  4972.4    0.13       0  5016.3    0.13       0  5350.0    0.08       0
  5385.8    0.13       0  5419.3    0.08       0
Bank Sta=4968.6,5016.3
XS Rating Curve= 0
Exp/Cntr=0.3,0.1

Type RM Length L Ch R = 1,137713,156,165,175
BEGIN DESCRIPTION:
Fourth Creek 218.5
END DESCRIPTION:
XS GIS Cut Line= 4
      1443175.01       755249.25      1442972.74       755249.25
      1442747.03       755189.23      1442657.07       755057.55
#Sta/Elev= 30
  4675.6  811.78  4701.4  805.13  4715.2  803.46  4778.5  800.50  4806.2  798.22
  4826.8  797.47  4834.3  796.78  4876.0  795.27  4916.4  794.82  4930.9  793.67
  4960.8  789.33  4962.8  788.36  4974.3  787.36  4976.5  787.17  4981.4  782.70
  4987.1  780.40  5000.5  779.22  5011.6  779.95  5011.7  780.43  5013.8  783.48
  5013.9  787.26  5022.4  792.98  5047.0  796.72  5084.5  802.63  5124.4  807.69
  5180.6  811.78  5189.3  812.23  5201.2  813.58  5256.0  816.30  5270.9  816.56
#Mann=8,-1,0
  4675.6    0.14       0  4778.5    0.08       0  4974.3    0.13       0
  4976.5   0.042       0  5013.9    0.13       0  5047.0    0.08       0
  5180.6    0.13       0  5256.0    0.08       0
Bank Sta=4976.5,5013.9
XS Rating Curve= 0
Exp/Cntr=0.5,0.3

Type RM Length L Ch R = 1,137548,52,50,54
BEGIN DESCRIPTION:
Pump Station Rd (FC) us
END DESCRIPTION:
XS GIS Cut Line= 5
      1443168.49       755224.20      1443051.02       755202.02
      1442805.74       754988.05      1442715.72       754924.12
      1442570.87       754922.81
#Sta/Elev= 30
  4657.9  812.42  4683.3  809.45  4725.9  802.41  4743.3  801.21  4826.5  798.26
  4916.0  795.44  4969.5  788.64  4976.5  787.08  4981.4  782.61  4987.1  780.31
  5000.5  779.13  5011.6  779.86  5022.5  787.17  5035.0  789.64  5048.6  794.69
  5082.0  794.88  5095.4  797.16  5129.1  802.18  5139.1  800.38  5166.4  800.28
  5180.4  798.77  5200.1  798.65  5206.1  796.39  5214.1  796.45  5223.6  800.06
  5245.5  802.55  5279.4  803.28  5307.1  801.35  5328.2  802.37  5358.2  805.09
#Mann=10,-1,0
  4657.9    0.14       0  4743.3    0.08       0  4826.5    0.14       0
  4969.5    0.13       0  4976.5   0.042       0  5022.5    0.13       0
  5095.4    0.08       0  5166.4    0.13       0  5180.4    0.08       0
  5328.2    0.13       0
#XS Ineff=3,-1
 4903.50 4953.50  796.21 5051.40 5085.30  796.07 5085.40 5360.10  807.54
Permanent Ineff=
       F       F       F
Bank Sta=4976.5,5022.5
XS Rating Curve= 0
Exp/Cntr=0.5,0.3

Type RM Length L Ch R =3,137524,,,
BEGIN DESCRIPTION:
Pump Station Rd (FC) TOR
Structure ID: I_FC_14
Detailed Survey Structure
END DESCRIPTION:
Bridge Culvert--1,0,-1,-1,0
Deck Dist Width WeirC Skew NumUp NumDn MinLoCord MaxHiCord MaxSubmerge Is_Ogee
14,20,3,,21,21,,,,0,1,1,,,
  4665.1  4693.8  4730.2  4781.2  4820.1  4872.5  4921.8  4967.5  4967.5  4968.6
  4968.6  5036.7  5036.7  5037.4  5037.4  5078.6  5129.7  5183.5  5235.9  5295.3
  5359.1
  811.65  808.42  802.18  800.06  798.75  797.48  795.99  795.58  795.58  795.58
  797.96  797.93  795.55  795.55  795.55  795.60  796.26  796.67  797.06  799.83
  803.04
  759.13  759.13  759.13  759.13  759.13  759.13  759.13  759.13  792.08  792.08
  792.08  792.05  792.05  792.05  759.13  759.13  759.13  759.13  759.13  759.13
  759.13
  4665.1  4693.8  4730.2  4781.2  4820.1  4872.5  4921.8  4967.5  4967.5  4968.6
  4968.6  5036.7  5036.7  5037.4  5037.4  5078.6  5129.7  5183.5  5235.9  5295.3
  5359.1
  811.65  808.42  802.18  800.06  798.75  797.48  795.99  795.58  795.58  795.58
  797.96  797.93  795.55  795.55  795.55  795.60  796.26  796.67  797.06  799.83
  803.04
  759.13  759.13  759.13  759.13  759.13  759.13  759.13  759.13  792.08  792.08
  792.08  792.05  792.05  792.05  759.13  759.13  759.13  759.13  759.13  759.13
  759.13
BR Coef=1,1,0,1.25,0,,,0.8,0,2,0,
WSPro=,,,, 1 ,,,, 0 ,,,, 0 ,,,,-1 ,-1 ,-1 , 0 , 0 , 0 , 0 , 0
BC Design=,,0,,0,,,,,,

Type RM Length L Ch R = 1,137498,256,272,276
BEGIN DESCRIPTION:
Pump Station Rd (FC) ds
END DESCRIPTION:
XS GIS Cut Line= 5
      1443169.74       755204.62      1443054.94       755149.83
      1442850.10       754968.48      1442727.46       754892.81
      1442566.99       754899.33
#Sta/Elev= 30
  4657.3  812.79  4715.3  807.59  4732.6  803.43  4739.4  802.13  4743.3  802.13
  4759.2  801.70  4778.4  799.90  4826.5  798.36  4916.0  795.54  4969.5  788.74
  4976.5  787.18  4981.4  782.71  4987.1  780.41  5000.5  779.23  5011.6  779.96
  5016.2  783.49  5022.5  787.27  5035.0  789.74  5087.5  795.16  5095.4  795.34
  5166.4  797.08  5180.4  797.49  5192.7  797.85  5237.0  796.89  5266.0  797.68
  5310.6  801.01  5328.2  801.52  5347.6  802.54  5356.9  802.18  5362.8  802.94
#Mann=10,-1,0
  4657.3    0.14       0  4743.3    0.08       0  4826.5    0.14       0
  4969.5    0.13       0  4976.5   0.042       0  5022.5    0.13       0
  5095.4    0.08       0  5166.4    0.13       0  5180.4    0.08       0
  5328.2    0.13       0
#XS Ineff=3,-1
 4901.50 4951.50  796.22 5053.40 5084.50  796.07 5084.60 5362.40  811.29
Permanent Ineff=
       F       F       F
Bank Sta=4976.5,5022.5
XS Rating Curve= 0
Exp/Cntr=0.5,0.3