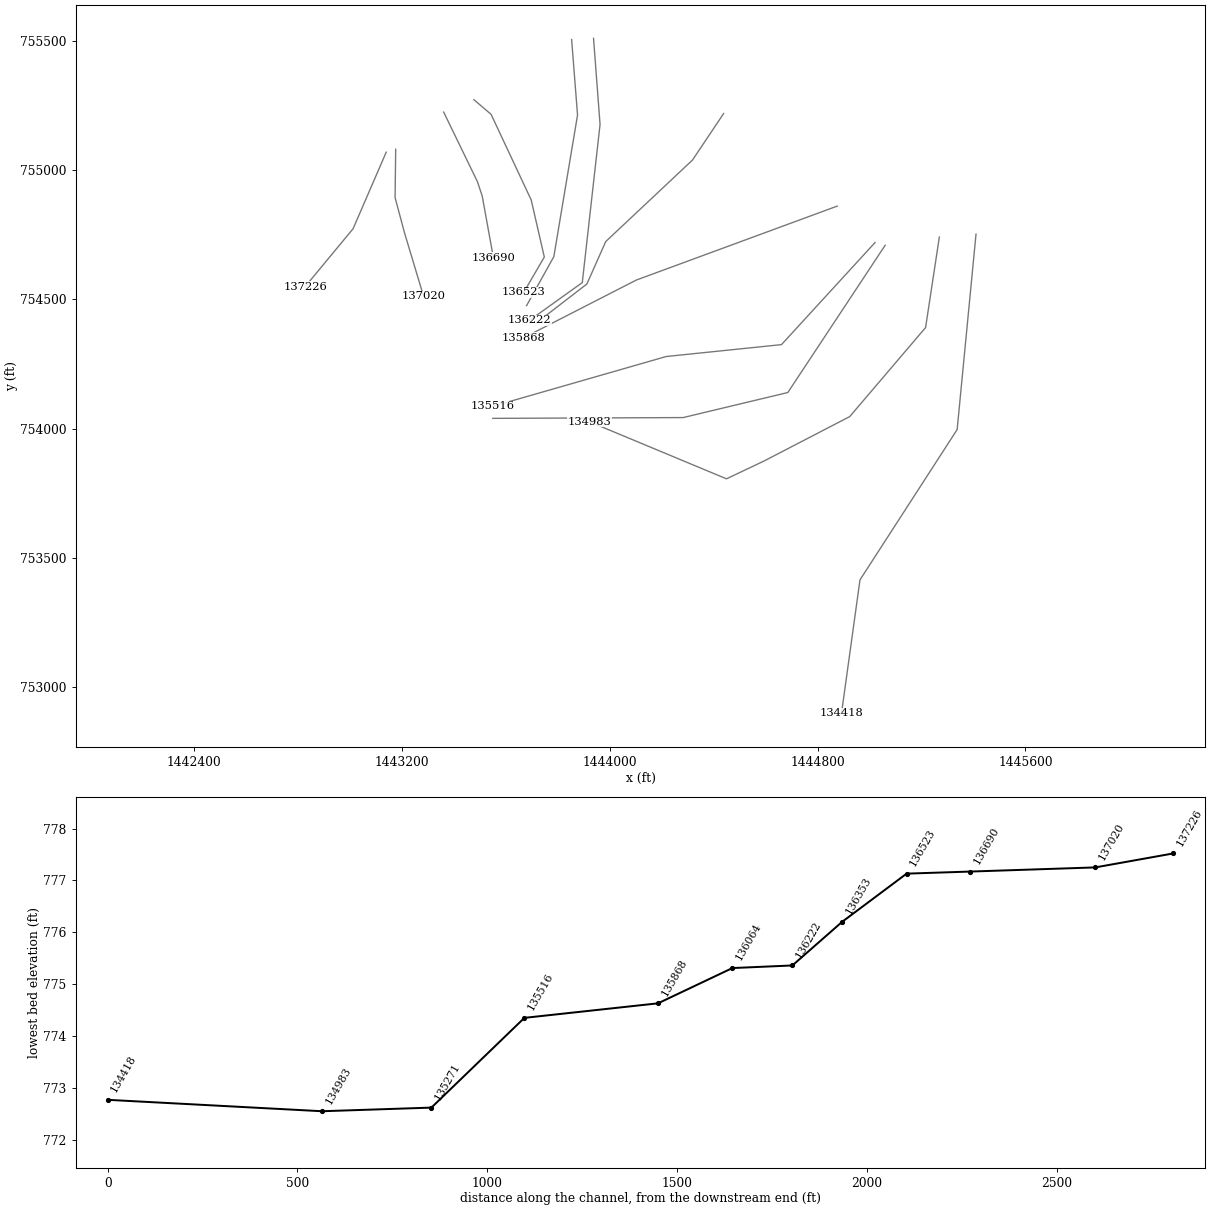
HEC-RAS study Fourth Creek.prj: Fourth Creek Detailed Study

--- Fourth Creek.g01 (geometry) --- (continued)

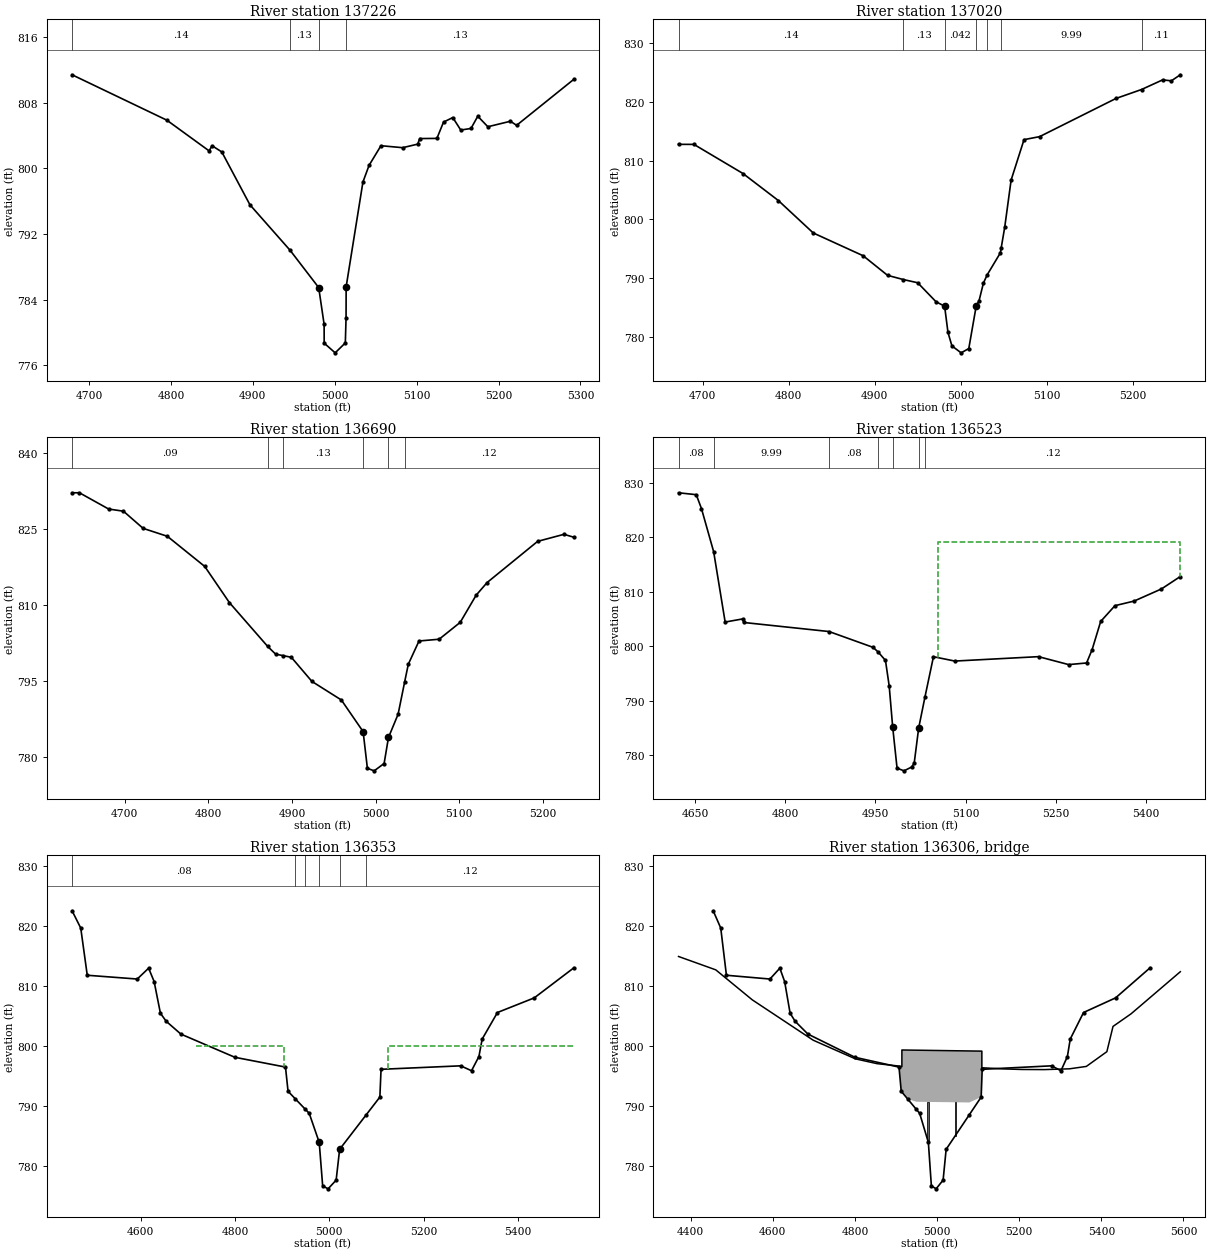
Type RM Length L Ch R = 1,137226,177,206,227
BEGIN DESCRIPTION:
Fourth Creek 218.0
END DESCRIPTION:
XS GIS Cut Line= 3
      1443139.25       755068.44      1443011.80       754772.68
      1442826.90       754548.56
#Sta/Elev= 30
  4679.3  811.39  4795.0  805.86  4846.6  802.12  4850.2  802.75  4862.1  801.99
  4896.4  795.56  4945.4  790.02  4980.4  785.47  4987.0  781.00  4987.1  778.70
  5000.5  777.52  5012.9  778.73  5013.8  781.78  5013.9  785.56  5034.4  798.33
  5041.9  800.36  5056.4  802.75  5082.8  802.51  5101.2  802.94  5103.8  803.62
  5124.7  803.64  5132.8  805.63  5144.1  806.18  5153.8  804.66  5166.3  804.85
  5174.6  806.34  5186.9  805.06  5214.5  805.73  5222.0  805.23  5291.9  810.84
#Mann=4,-1,0
  4679.3    0.14       0  4945.4    0.13       0  4980.4   0.042       0
  5013.9    0.13       0
Bank Sta=4980.4,5013.9
XS Rating Curve= 0
Exp/Cntr=0.3,0.1

Type RM Length L Ch R = 1,137020,327,330,330
BEGIN DESCRIPTION:
Fourth Creek 217.0
END DESCRIPTION:
XS GIS Cut Line= 4
      1443175.74       755079.85      1443173.46       754892.84
      1443209.94       754756.04      1443282.92       754512.03
#Sta/Elev= 30
  4671.9  812.77  4689.8  812.76  4746.8  807.80  4787.9  803.20  4828.5  797.67
  4886.5  793.79  4914.9  790.45  4933.4  789.73  4949.9  789.19  4971.3  785.94
  4981.2  785.20  4985.1  780.73  4989.7  778.43  5000.4  777.25  5009.3  777.98
  5018.0  785.29  5021.2  786.11  5026.3  789.13  5030.7  790.54  5046.0  794.28
  5046.9  795.06  5051.1  798.68  5058.5  806.68  5073.5  813.57  5091.6  814.08
  5180.3  820.58  5210.1  822.11  5234.6  823.75  5244.8  823.59  5255.2  824.62
#Mann=7,-1,0
  4671.9    0.14       0  4933.4    0.13       0  4981.2   0.042       0
  5018.0    0.13       0  5030.7    0.08       0  5046.9    9.99       0
  5210.1    0.11       0
Bank Sta=4981.2,5018
XS Rating Curve= 0
Exp/Cntr=0.3,0.1

Type RM Length L Ch R = 1,136690,164,167,170
BEGIN DESCRIPTION:
Fourth Creek 216.0
END DESCRIPTION:
XS GIS Cut Line= 4
      1443360.44       755223.45      1443490.40       754954.41
      1443508.64       754899.68      1443551.97       754660.25
#Sta/Elev= 30
  4637.2  832.12  4646.0  832.12  4680.9  828.91  4698.6  828.48  4722.1  825.09
  4751.1  823.52  4795.8  817.56  4825.2  810.43  4871.0  801.76  4880.5  800.23
  4888.8  799.96  4899.3  799.61  4923.9  794.84  4959.1  791.17  4985.1  784.92
  4990.2  777.67  4998.3  777.17  5010.2  778.62  5015.4  783.76  5026.9  788.35
  5034.8  794.79  5039.1  798.23  5051.9  802.83  5076.0  803.18  5101.2  806.52
  5120.2  811.88  5133.3  814.38  5193.7  822.52  5225.2  823.91  5237.0  823.33
#Mann=6,-1,0
  4637.2    0.09       0  4871.0    0.13       0  4888.8    0.13       0
  4985.1   0.042       0  5015.4    0.13       0  5034.8    0.12       0
Bank Sta=4985.1,5015.4
XS Rating Curve= 0
Exp/Cntr=0.3,0.1

Type RM Length L Ch R = 1,136523,178,170,162
BEGIN DESCRIPTION:
Fourth Creek 215.5
END DESCRIPTION:
XS GIS Cut Line= 5
      1443476.79       755271.39      1443542.98       755214.65
      1443697.41       754883.73      1443747.84       754663.11
      1443669.06       754527.62
#Sta/Elev= 30
  4622.2  828.17  4651.7  827.82  4660.4  825.26  4680.7  817.34  4699.8  804.44
  4728.7  805.01  4730.9  804.36  4872.8  802.70  4946.0  799.80  4954.4  798.96
  4966.7  797.40  4972.9  792.73  4978.7  785.18  4986.0  777.63  4997.5  777.13
  5010.5  777.84  5014.6  778.58  5022.0  784.99  5032.6  790.76  5046.6  798.08
  5082.1  797.28  5221.5  798.09  5271.7  796.63  5301.5  796.93  5310.7  799.36
  5325.0  804.55  5348.8  807.45  5380.6  808.29  5426.2  810.52  5457.6  812.80
#Mann=7,-1,0
  4622.2    0.08       0  4680.7    9.99       0  4872.8    0.08       0
  4954.4    0.13       0  4978.7    0.04       0  5022.0    0.13       0
  5032.6    0.12       0
#XS Ineff=2,0
       0                 5054.00    0.00  819.20
Permanent Ineff=
       F       F
Bank Sta=4978.7,5022
XS Rating Curve= 0
Exp/Cntr=0.5,0.3

Type RM Length L Ch R = 1,136353,117,131,131
BEGIN DESCRIPTION:
Turnersburg Hwy (FC) us
END DESCRIPTION:
XS GIS Cut Line= 4
      1443852.95       755503.88      1443875.75       755212.06
      1443784.54       754664.83      1443679.64       754475.55
#Sta/Elev= 30
  4454.7  822.56  4473.1  819.68  4486.9  811.81  4592.9  811.18  4617.0  812.99
  4628.7  810.76  4642.0  805.48  4654.2  804.14  4685.4  802.00  4800.0  798.13
  4907.2  796.50  4912.6  792.47  4928.3  791.18  4949.5  789.44  4957.5  788.79
  4978.7  783.95  4986.0  776.70  4997.5  776.20  5014.6  777.65  5022.0  782.79
  5078.5  788.56  5107.3  791.50  5109.8  796.13  5278.7  796.71  5301.6  795.89
  5317.3  798.26  5324.2  801.17  5356.6  805.60  5434.7  808.04  5518.6  813.05
#Mann=6,-1,0
  4454.7    0.08       0  4928.3     0.1       0  4949.5    0.13       0
  4978.7   0.042       0  5022.0    0.13       0  5078.5    0.12       0
#XS Ineff=2,-1
 4716.50 4904.50  800.00 5124.20 5519.00  800.00
Permanent Ineff=
       F       F
Bank Sta=4978.7,5022
XS Rating Curve= 0
Exp/Cntr=0.5,0.3

Type RM Length L Ch R =3,136306,,,
BEGIN DESCRIPTION:
Turnersburg Hwy (FC) TOR
Structure ID: I_FC_13
Detailed Survey Structure
END DESCRIPTION:
Bridge Culvert--1,0,-1,-1,0
Deck Dist Width WeirC Skew NumUp NumDn MinLoCord MaxHiCord MaxSubmerge Is_Ogee
11,72,3,,25,25,,,,0,1,1,,,
  4370.3  4461.0  4549.9  4698.0  4747.4  4801.2  4853.8  4905.0  4914.2  4914.2
  4915.5  4915.5  5109.0  5109.0  5113.2  5113.2  5163.9  5206.1  5261.2  5322.3
  5363.4  5413.4  5428.4  5472.5  5592.3
  814.94  812.71  807.71  800.99  799.49  797.87  797.07  796.69  796.57  799.35
  799.35  799.35  799.16  796.37  796.37  796.37  796.19  796.10  796.08  796.21
  796.61  799.07  803.28  805.39  812.40
  756.20  756.20  756.20  756.20  756.20  756.20  756.20  756.20  756.20  756.20
  756.20  790.75  790.57  790.57  790.57  756.20  756.20  756.20  756.20  756.20
  756.20  756.20  756.20  756.20  756.20
  4370.3  4461.0  4549.9  4698.0  4747.4  4801.2  4853.8  4905.0  4914.2  4914.2
  4915.5  4915.5  5109.0  5109.0  5113.2  5113.2  5163.9  5206.1  5261.2  5322.3
  5363.4  5413.4  5428.4  5472.5  5592.3
  814.94  812.71  807.71  800.99  799.49  797.87  797.07  796.69  796.57  799.35
  799.35  799.35  799.16  796.37  796.37  796.37  796.19  796.10  796.08  796.21
  796.61  799.07  803.28  805.39  812.40
  756.20  756.20  756.20  756.20  756.20  756.20  756.20  756.20  756.20  756.20
  756.20  790.75  790.57  790.57  790.57  756.20  756.20  756.20  756.20  756.20
  756.20  756.20  756.20  756.20  756.20
Pier Skew, UpSta & Num, DnSta & Num=,4977.8,2,4977.8,2,0,0,0,0,0
       3       3
  783.97  790.69
       3       3
  783.38  790.69
Pier Skew, UpSta & Num, DnSta & Num=,5044.4,2,5044.4,2,0,0,0,0,0
       3       3
  784.42  790.63
       3       3
  783.83  790.63
BR Coef=1,1,0,1.25,0,,,0.8,0,2,0,
WSPro=,,,, 1 ,,,, 0 ,,,, 0 ,,,,-1 ,-1 ,-1 , 0 , 0 , 0 , 0 , 0
BC Design=,,0,,0,,,,,,

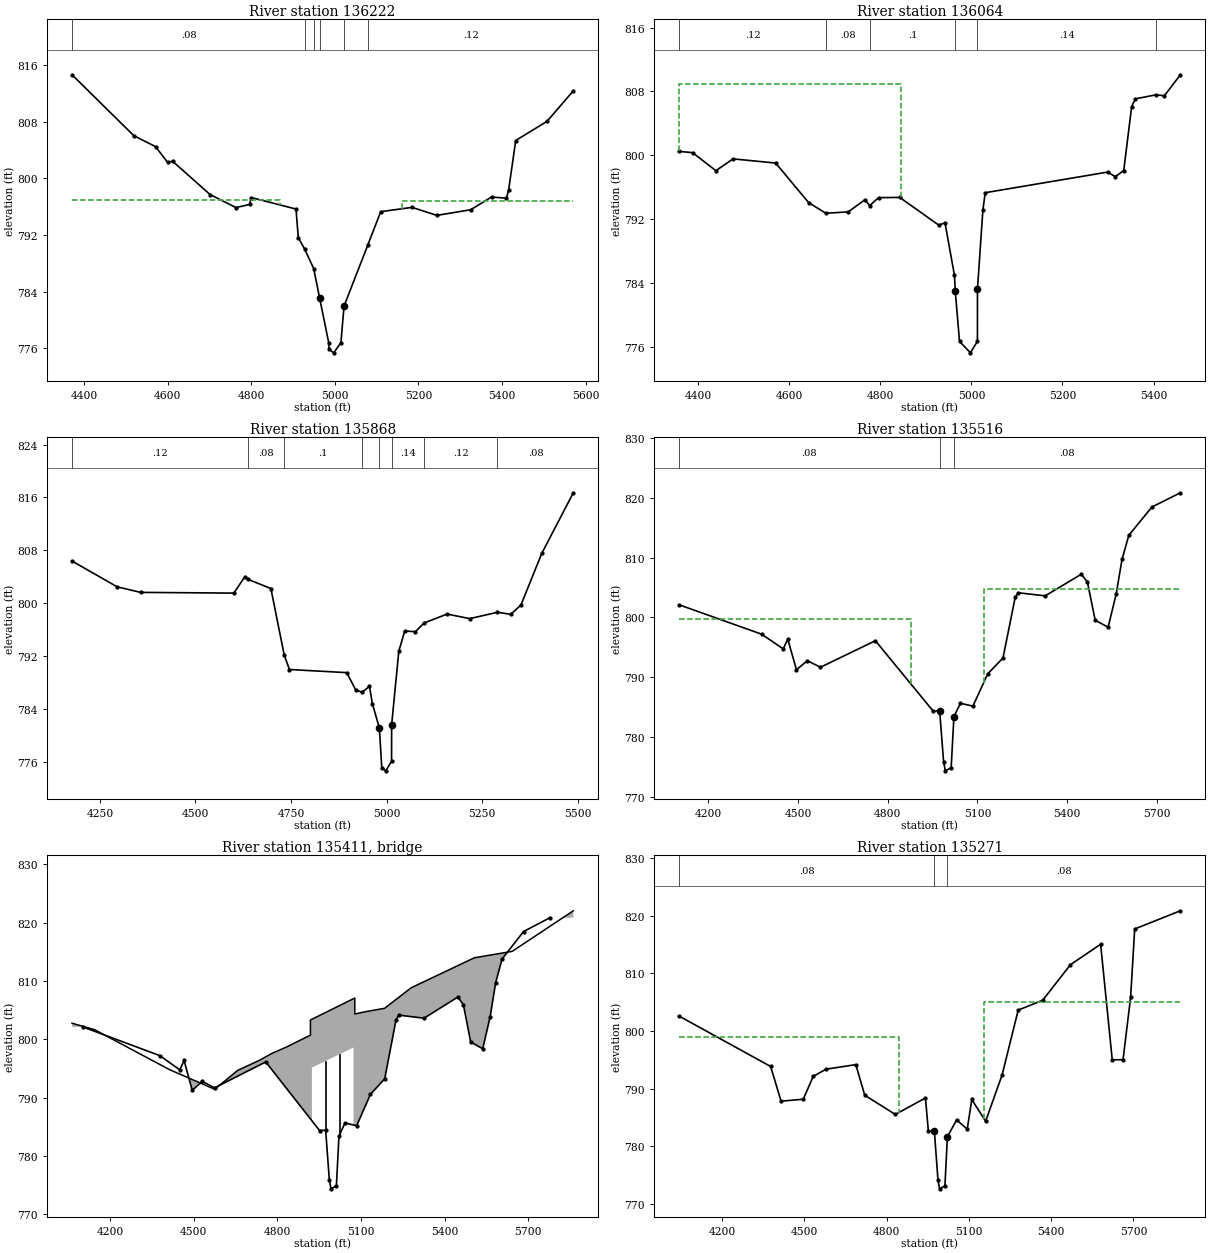
Type RM Length L Ch R = 1,136222,180,158,140
BEGIN DESCRIPTION:
Turnersburg Hwy (FC) ds
END DESCRIPTION:
XS GIS Cut Line= 4
      1443937.31       755508.45      1443962.39       755175.58
      1443893.99       754564.50      1443691.03       754418.55
#Sta/Elev= 30
  4371.6  814.62  4519.4  806.02  4571.4  804.47  4600.0  802.26  4612.1  802.41
  4701.7  797.71  4763.5  795.87  4796.1  796.31  4800.0  797.29  4907.2  795.66
  4912.6  791.63  4928.3  789.96  4949.5  787.25  4963.6  783.11  4985.4  776.79
  4986.0  775.86  4997.5  775.36  5014.6  776.81  5022.0  781.95  5078.5  790.53
  5109.8  795.29  5184.6  795.90  5244.0  794.77  5324.7  795.56  5374.7  797.36
  5410.3  797.19  5415.5  798.30  5432.6  805.34  5507.5  808.05  5570.3  812.36
#Mann=6,-1,0
  4371.6    0.08       0  4928.3     0.1       0  4949.5    0.13       0
  4963.6   0.042       0  5022.0    0.13       0  5078.5    0.12       0
#XS Ineff=2,0
    0.00 4868.50  796.96 5160.20    0.00  796.80
Permanent Ineff=
       F       F
Bank Sta=4963.6,5022
XS Rating Curve= 0
Exp/Cntr=0.5,0.3

Type RM Length L Ch R = 1,136064,212,196,192
BEGIN DESCRIPTION:
Fourth Creek 215.1
END DESCRIPTION:
XS GIS Cut Line= 5
      1444438.05       755217.81      1444318.28       755038.16
      1443984.21       754722.99      1443911.72       754559.11
      1443716.33       754407.84
#Sta/Elev= 30
  4357.5  800.51  4387.3  800.35  4438.4  798.09  4476.0  799.57  4569.7  799.05
  4642.2  794.10  4680.1  792.77  4729.2  792.94  4765.6  794.45  4776.5  793.73
  4795.9  794.72  4842.4  794.75  4928.2  791.28  4941.8  791.58  4962.6  785.01
  4964.4  783.06  4973.7  776.74  4997.8  775.31  5013.1  776.76  5013.2  783.30
  5025.1  793.18  5030.2  795.34  5299.3  797.92  5316.0  797.35  5334.6  798.11
  5352.0  806.12  5360.2  807.08  5405.3  807.58  5424.0  807.47  5459.0  810.09
#Mann=6,-1,0
  4357.5    0.12       0  4680.1    0.08       0  4776.5     0.1       0
  4964.4    0.04       0  5013.2    0.14       0  5405.3    0.08       0
#XS Ineff=2,0
    0.00 4844.70  808.93               0
Permanent Ineff=
       F       F
Bank Sta=4964.4,5013.2
XS Rating Curve= 0
Exp/Cntr=0.3,0.1

Type RM Length L Ch R = 1,135868,351,352,344
BEGIN DESCRIPTION:
Fourth Creek 215.0
END DESCRIPTION:
XS GIS Cut Line= 3
      1444875.38       754860.09      1444102.27       754574.45
      1443668.83       754351.52
#Sta/Elev= 30
  4177.0  806.37  4295.1  802.47  4356.4  801.63  4600.5  801.52  4628.8  803.98
  4638.4  803.58  4697.3  802.21  4731.9  792.22  4745.7  789.96  4895.7  789.49
  4919.4  786.86  4936.2  786.52  4955.2  787.42  4962.8  784.80  4981.1  781.11
  4987.4  775.13  4997.8  774.63  5013.1  776.08  5013.2  781.57  5032.0  792.73
  5047.4  795.78  5075.6  795.69  5097.7  796.99  5158.3  798.35  5217.6  797.66
  5290.2  798.62  5325.1  798.31  5351.5  799.72  5406.3  807.56  5488.6  816.70
#Mann=8,-1,0
  4177.0    0.12       0  4638.4    0.08       0  4731.9     0.1       0
  4936.2    0.14       0  4981.1   0.042       0  5013.2    0.14       0
  5097.7    0.12       0  5290.2    0.08       0
Bank Sta=4981.1,5013.2
XS Rating Curve= 0
Exp/Cntr=0.5,0.3

Type RM Length L Ch R = 1,135516,239,245,256
BEGIN DESCRIPTION:
I-40 (FC) us
END DESCRIPTION:
XS GIS Cut Line= 4
      1445021.04       754719.44      1444660.73       754324.76
      1444217.15       754278.87      1443549.61       754086.37
#Sta/Elev= 30
  4103.0  802.12  4378.9  797.20  4450.9  794.75  4466.3  796.36  4495.3  791.25
  4531.7  792.77  4575.4  791.67  4759.0  796.11  4951.9  784.35  4973.7  784.40
  4987.0  775.84  4992.7  774.35  5012.2  774.86  5021.4  783.40  5043.2  785.65
  5084.8  785.17  5134.4  790.57  5185.4  793.22  5226.1  803.34  5236.7  804.13
  5326.4  803.61  5447.2  807.23  5467.4  805.94  5493.5  799.54  5536.7  798.37
  5563.5  803.88  5583.2  809.71  5605.9  813.74  5683.1  818.47  5778.1  820.85
#Mann=3,-1,0
  4103.0    0.08       0  4973.7   0.042       0  5021.4    0.08       0
#XS Ineff=2,0
    0.00 4877.50  799.72 5120.60    0.00  804.76
Permanent Ineff=
       F       F
Bank Sta=4973.7,5021.4
XS Rating Curve= 0
Exp/Cntr=0.5,0.3

Type RM Length L Ch R =3,135411,,,
BEGIN DESCRIPTION:
I-40 (FC) TOR
Structure ID: I_FC_12
Detailed Survey Structure
END DESCRIPTION:
Bridge Culvert--1,0,-1,-1,0
Deck Dist Width WeirC Skew NumUp NumDn MinLoCord MaxHiCord MaxSubmerge Is_Ogee
47,116,3,,23,23,,,,0,1,1,,,
  4064.6  4145.0  4414.0  4576.2  4658.0  4736.3  4780.8  4833.7  4919.1  4919.1
  4924.5  4924.5  5073.6  5073.6  5078.2  5078.2  5118.1  5185.1  5280.0  5382.5
  5506.6  5642.4  5861.5
  802.75  801.65  794.79  791.42  794.65  796.39  797.57  798.68  800.71  803.30
  803.43  803.43  806.96  806.96  807.07  804.33  804.74  805.31  808.82  811.15
  813.97  815.07  822.03
  754.35  754.35  754.35  754.35  754.35  754.35  754.35  754.35  754.35  754.35
  754.35  795.14  798.59  754.35  754.35  754.35  754.35  754.35  754.35  754.35
  754.35  754.35  754.35
  4064.6  4145.0  4414.0  4576.2  4658.0  4736.3  4780.8  4833.7  4919.1  4919.1
  4924.5  4924.5  5073.6  5073.6  5078.2  5078.2  5118.1  5185.1  5280.0  5382.5
  5506.6  5642.4  5861.5
  802.75  801.65  794.79  791.42  794.65  796.39  797.57  798.68  800.71  803.30
  803.43  803.43  806.96  806.96  807.07  804.33  804.74  805.31  808.82  811.15
  813.97  815.07  822.03
  754.35  754.35  754.35  754.35  754.35  754.35  754.35  754.35  754.35  754.35
  754.35  795.14  798.59  754.35  754.35  754.35  754.35  754.35  754.35  754.35
  754.35  754.35  754.35
Pier Skew, UpSta & Num, DnSta & Num=,4973.2,2,4973.2,2,0,0,0,0,0
     2.5     2.5
  784.50  796.27
     2.5     2.5
  782.77  796.27
Pier Skew, UpSta & Num, DnSta & Num=,5023.4,2,5023.4,2,0,0,0,0,0
     2.5     2.5
  783.83  797.43
     2.5     2.5
  782.10  797.43
BR Coef=1,1,0,1.25,0,,,0.8,0,2,0,
WSPro=,,,, 1 ,,,, 0 ,,,, 0 ,,,,-1 ,-1 ,-1 , 0 , 0 , 0 , 0 , 0
BC Design=,,0,,0,,,,,,

Type RM Length L Ch R = 1,135271,340,288,271
BEGIN DESCRIPTION:
I-40 (FC) ds
END DESCRIPTION:
XS GIS Cut Line= 4
      1445059.92       754708.82      1444685.23       754139.72
      1444282.35       754042.91      1443549.67       754039.81
#Sta/Elev= 30
  4042.6  802.58  4376.6  793.84  4414.6  787.82  4495.6  788.16  4532.0  792.13
  4578.7  793.37  4687.3  794.16  4719.8  788.85  4831.3  785.52  4941.2  788.38
  4951.9  782.62  4973.7  782.67  4987.0  774.11  4992.7  772.62  5012.2  773.13
  5021.4  781.67  5054.9  784.57  5093.7  782.97  5110.3  788.12  5160.8  784.34
  5221.1  792.42  5279.5  803.61  5369.1  805.33  5470.1  811.49  5580.2  815.03
  5622.6  794.99  5662.0  795.02  5689.7  805.89  5704.4  817.68  5871.0  820.84
#Mann=3,-1,0
  4042.6    0.08       0  4973.7   0.042       0  5021.4    0.08       0
#XS Ineff=2,0
    0.00 4843.50  798.91 5154.60    0.00  805.05
Permanent Ineff=
       F       F
Bank Sta=4973.7,5021.4
XS Rating Curve= 0
Exp/Cntr=0.5,0.3

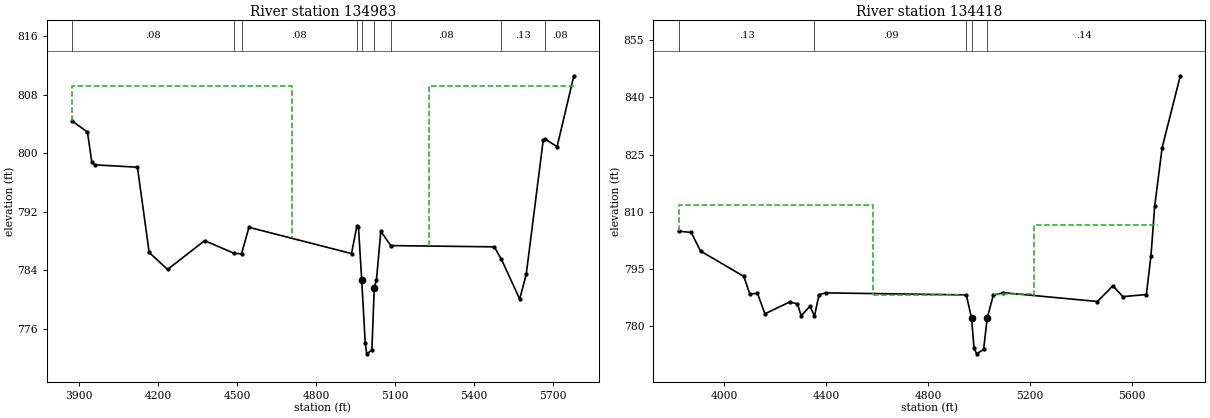
Type RM Length L Ch R = 1,134983,484,565,699
BEGIN DESCRIPTION:
Fourth Creek 213.0
END DESCRIPTION:
XS GIS Cut Line= 6
      1445268.49       754740.68      1445215.46       754390.70
      1444923.46       754046.67      1444593.54       753874.97
      1444449.18       753806.19      1443922.62       754026.39
#Sta/Elev= 30
  3872.4  804.40  3930.8  802.87  3947.4  798.78  3958.3  798.39  4120.9  798.07
  4165.5  786.41  4235.6  784.09  4376.4  788.03  4488.7  786.29  4516.7  786.23
  4544.9  789.85  4934.9  786.26  4955.2  790.02  4961.4  789.83  4973.7  782.60
  4987.0  774.04  4992.7  772.55  5012.2  773.06  5021.4  781.60  5029.5  782.59
  5046.2  789.30  5084.2  787.35  5477.7  787.18  5505.0  785.45  5574.3  780.04
  5599.1  783.42  5663.8  801.79  5671.2  801.91  5716.4  800.88  5780.2  810.57
#Mann=9,-1,0
  3872.4    0.08       0  4488.7    0.13       0  4516.7    0.08       0
  4955.2    0.13       0  4973.7   0.042       0  5021.4    0.13       0
  5084.2    0.08       0  5505.0    0.13       0  5671.2    0.08       0
#XS Ineff=2,0
    0.00 4707.20  809.23 5228.60    0.00  809.23
Permanent Ineff=
       F       F
Bank Sta=4973.7,5021.4
XS Rating Curve= 0
Exp/Cntr=0.5,0.3

Type RM Length L Ch R = 1,134418,149,98,110
BEGIN DESCRIPTION:
Free Nancy Ave (FC) us
END DESCRIPTION:
XS GIS Cut Line= 4
      1445409.60       754751.90      1445336.98       753996.63
      1444962.95       753415.62      1444891.74       752899.75
#Sta/Elev= 30
  3819.7  804.93  3869.6  804.59  3906.2  799.71  4075.9  793.08  4099.5  788.46
  4129.7  788.63  4159.0  783.26  4255.7  786.36  4286.7  785.86  4301.1  782.75
  4335.8  785.23  4353.5  782.67  4371.3  788.26  4397.3  788.75  4950.0  788.22
  4970.3  782.08  4980.1  774.33  4990.4  772.77  5017.7  773.92  5031.6  782.05
  5055.5  788.08  5094.7  788.81  5464.6  786.49  5525.2  790.59  5564.5  787.77
  5656.8  788.31  5674.9  798.45  5689.6  811.52  5718.8  826.84  5790.2  845.66
#Mann=5,-1,0
  3819.7    0.13       0  4353.5    0.09       0  4950.0    0.14       0
  4970.3   0.045       0  5031.6    0.14       0
#XS Ineff=4,-1
 4581.60 4937.60  788.29 5063.90 5214.60  788.37 5214.70 5700.60  806.43
 3821.10 4581.50  811.66
Permanent Ineff=
       F       F       F       F
Bank Sta=4970.3,5031.6
XS Rating Curve= 0
Exp/Cntr=0.5,0.3