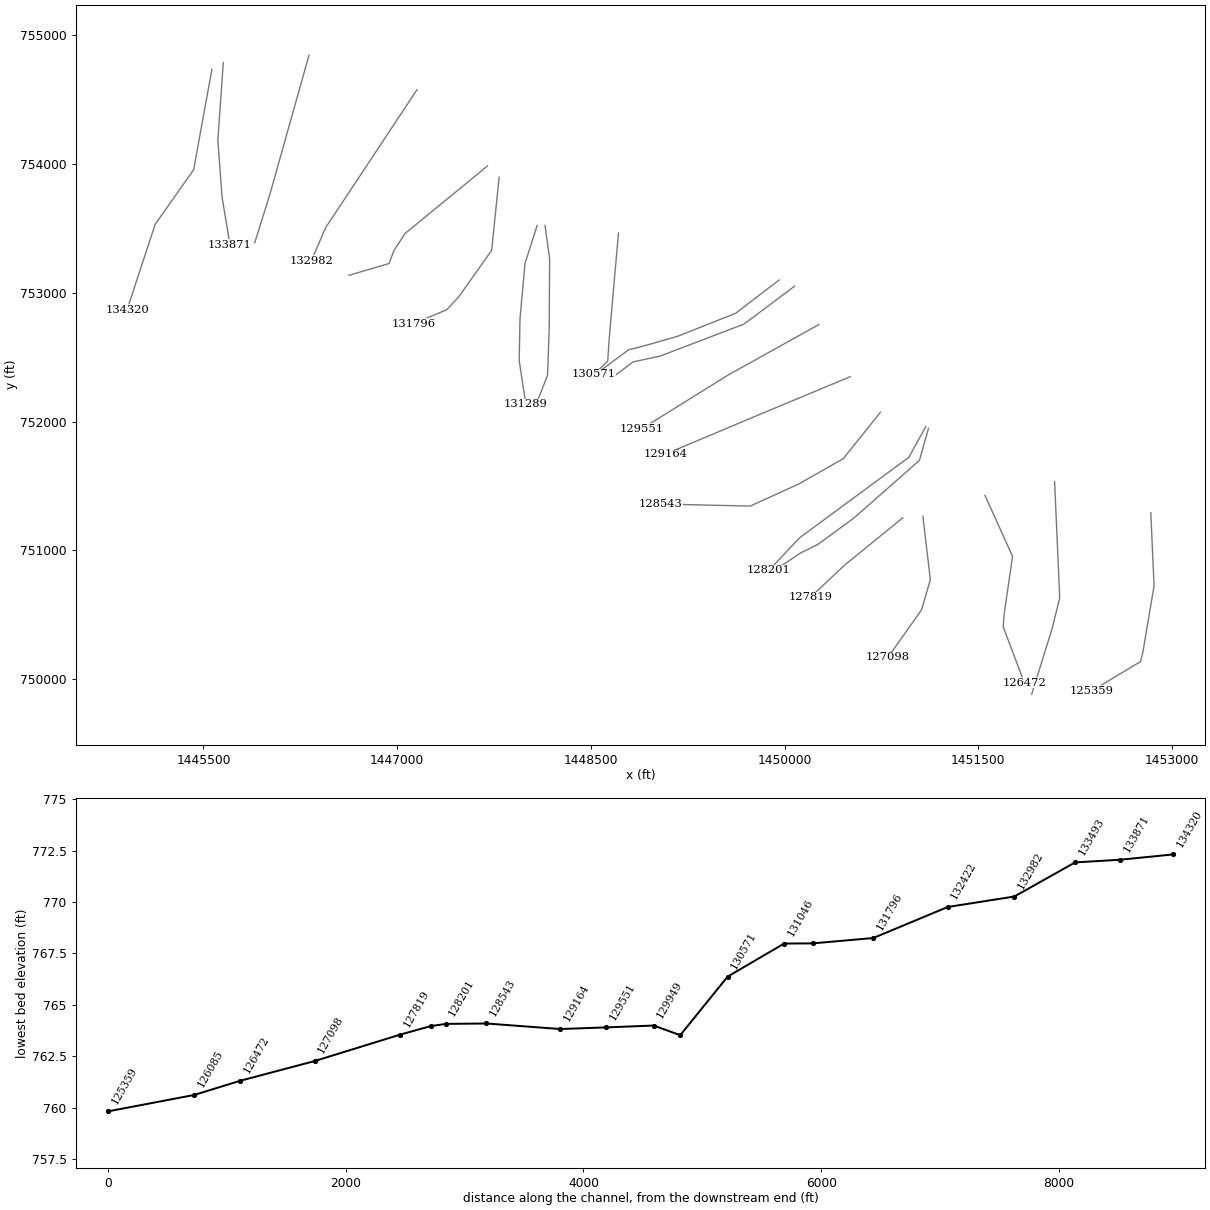
HEC-RAS study Fourth Creek.prj: Fourth Creek Detailed Study

--- Fourth Creek.g01 (geometry) --- (continued)

Type RM Length L Ch R =3,134368,,,
BEGIN DESCRIPTION:
Free Nancy Ave (FC) TOR
Structure ID: I_FC_10
Detailed Survey Structure
END DESCRIPTION:
Bridge Culvert--1,0,-1,-1,0
Deck Dist Width WeirC Skew NumUp NumDn MinLoCord MaxHiCord MaxSubmerge Is_Ogee
17.5,65,3,,31,31,,,,0,1,1,,,
  3799.7  3933.4  4078.3  4153.9  4229.7  4318.4  4369.3  4587.0  4750.7  4792.9
  4839.4  4886.3  4951.1  4951.1  4955.1  4955.1  5046.4  5046.4  5049.6  5049.6
  5070.3  5119.4  5164.3  5212.0  5248.7  5291.9  5563.5  5628.5  5676.8  5759.6
  5821.5
  805.64  798.13  791.09  784.55  785.90  786.39  788.56  787.84  787.91  788.02
  788.25  788.32  788.28  790.88  790.88  790.88  790.87  790.87  790.87  788.30
  788.34  788.30  788.16  787.90  787.58  787.69  791.19  788.13  795.64  833.45
  845.47
  752.77  752.77  752.77  752.77  752.77  752.77  752.77  752.77  752.77  752.77
  752.77  752.77  752.77  752.77  752.77  785.05  785.06  752.77  752.77  752.77
  752.77  752.77  752.77  752.77  752.77  752.77  752.77  752.77  752.77  752.77
  752.77
  3799.7  3933.4  4078.3  4153.9  4229.7  4318.4  4369.3  4587.0  4750.7  4792.9
  4839.4  4886.3  4951.1  4951.1  4955.1  4955.1  5046.4  5046.4  5049.6  5049.6
  5070.3  5119.4  5164.3  5212.0  5248.7  5291.9  5563.5  5628.5  5676.8  5759.6
  5821.5
  805.64  798.13  791.09  784.55  785.90  786.39  788.56  787.84  787.91  788.02
  788.25  788.32  788.28  790.88  790.88  790.88  790.87  790.87  790.87  788.30
  788.34  788.30  788.16  787.90  787.58  787.69  791.19  788.13  795.64  833.45
  845.47
  752.77  752.77  752.77  752.77  752.77  752.77  752.77  752.77  752.77  752.77
  752.77  752.77  752.77  752.77  752.77  785.05  785.06  752.77  752.77  752.77
  752.77  752.77  752.77  752.77  752.77  752.77  752.77  752.77  752.77  752.77
  752.77
Pier Skew, UpSta & Num, DnSta & Num=,4980.1,2,4980.1,2,0,0,0,0,0
       1       1
  774.33  785.05
       1       1
  773.88  785.05
Pier Skew, UpSta & Num, DnSta & Num=,5018.3,2,5018.3,2,0,0,0,0,0
       1       1
  774.49  785.06
       1       1
  774.04  785.06
BR Coef=1,1,0,1.25,0,,,0.8,0,2,0,
WSPro=,,,, 1 ,,,, 0 ,,,, 0 ,,,,-1 ,-1 ,-1 , 0 , 0 , 0 , 0 , 0
BC Design=,,0,,0,,,,,,

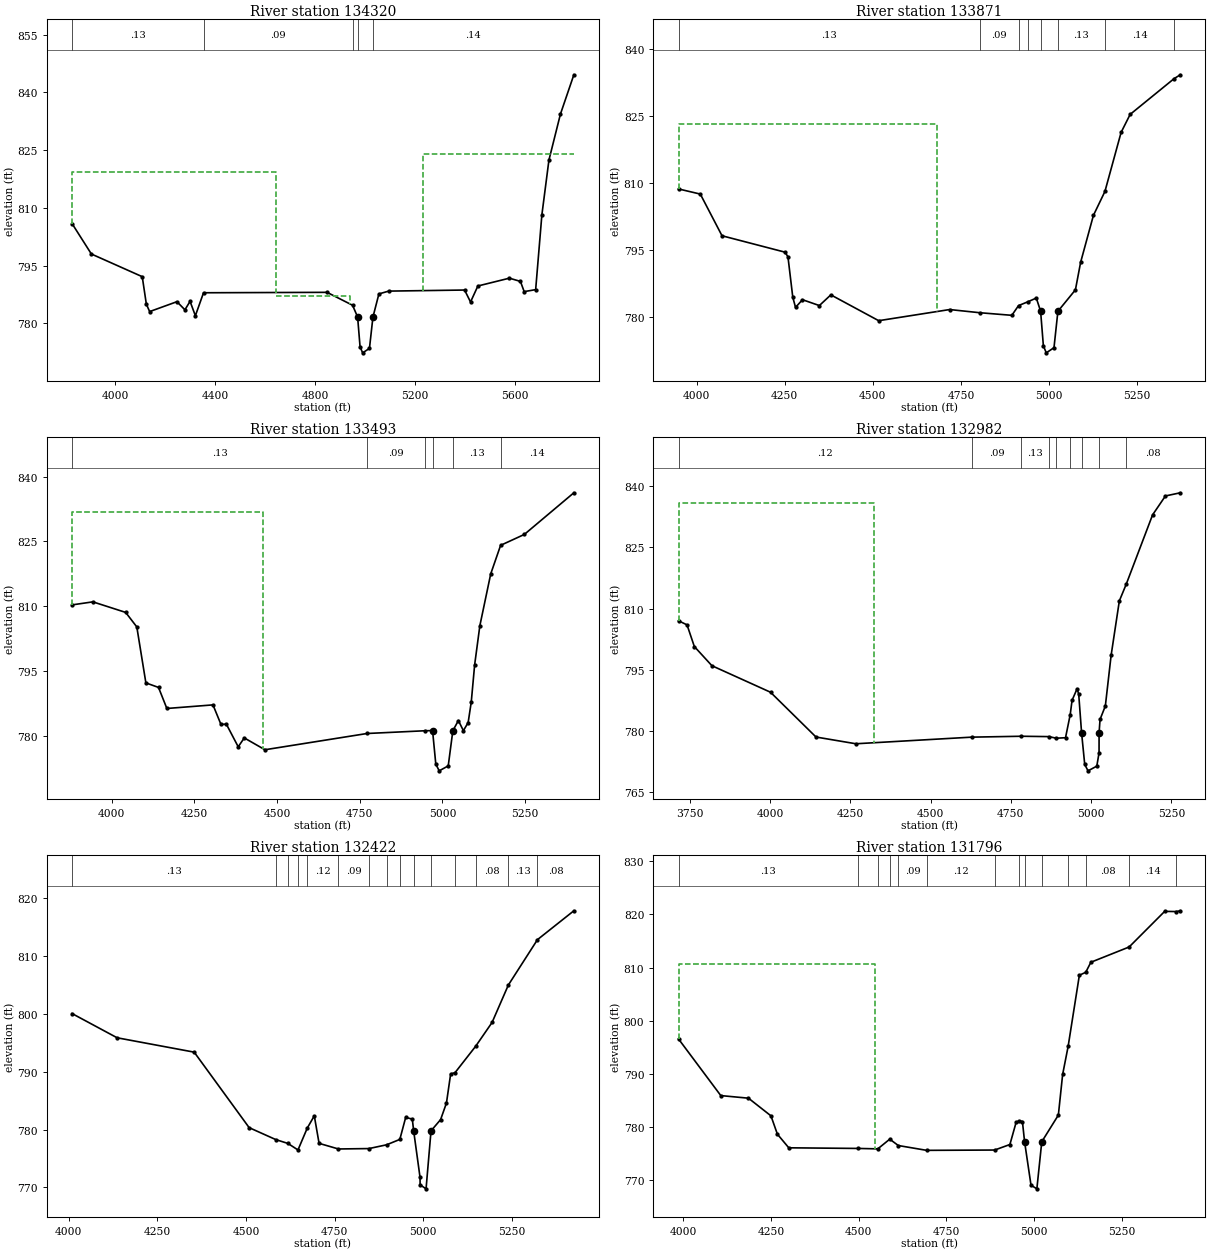
Type RM Length L Ch R = 1,134320,482,449,463
BEGIN DESCRIPTION:
Free Nancy Ave (FC) ds
END DESCRIPTION:
XS GIS Cut Line= 4
      1445565.75       754737.42      1445424.13       753956.69
      1445126.16       753532.30      1444909.22       752870.37
#Sta/Elev= 30
  3827.3  805.90  3904.6  798.00  4108.2  792.11  4124.7  784.94  4137.9  783.04
  4247.1  785.61  4279.0  783.50  4299.6  785.70  4320.9  781.96  4353.5  787.93
  4847.9  788.04  4950.0  784.69  4970.3  781.63  4980.1  773.88  4990.4  772.32
  5017.7  773.47  5031.6  781.60  5055.5  787.63  5094.7  788.36  5398.5  788.64
  5422.3  785.53  5451.7  789.69  5577.8  791.72  5622.1  790.88  5637.0  788.23
  5683.0  788.74  5707.9  808.19  5736.1  822.40  5782.2  834.36  5835.9  844.57
#Mann=5,-1,0
  3827.3    0.13       0  4353.5    0.09       0  4950.0    0.14       0
  4970.3   0.045       0  5031.6    0.14       0
#XS Ineff=4,-1
 4645.40 4939.60  787.00 5061.90 5232.10  787.00 3820.90 4645.30  819.34
 5232.20 5870.20  824.11
Permanent Ineff=
       F       F       F       F
Bank Sta=4970.3,5031.6
XS Rating Curve= 0
Exp/Cntr=0.5,0.3

Type RM Length L Ch R = 1,133871,440,378,363
BEGIN DESCRIPTION:
Fourth Creek 211.0
END DESCRIPTION:
XS GIS Cut Line= 4
      1445653.74       754788.45      1445611.40       754186.20
      1445644.33       753743.96      1445705.49       753372.26
#Sta/Elev= 30
  3948.8  808.67  4010.6  807.52  4072.2  798.21  4250.8  794.55  4259.3  793.52
  4273.0  784.48  4280.8  782.21  4300.5  783.93  4348.4  782.62  4381.0  785.01
  4516.8  779.24  4718.1  781.73  4803.7  781.02  4894.6  780.44  4913.6  782.61
  4941.5  783.51  4964.0  784.30  4976.2  781.37  4984.1  773.62  4992.3  772.06
  5014.2  773.21  5025.3  781.34  5075.0  786.13  5089.8  792.29  5126.1  802.77
  5158.7  808.10  5204.7  821.31  5230.3  825.32  5355.2  833.32  5372.7  834.17
#Mann=8,-1,0
  3948.8    0.13       0  4803.7    0.09       0  4913.6    0.08       0
  4941.5    0.13       0  4976.2   0.045       0  5025.3    0.13       0
  5158.7    0.14       0  5355.2    0.11       0
#XS Ineff=2,0
    0.00 4682.40  823.19               0
Permanent Ineff=
       F       F
Bank Sta=4976.2,5025.3
XS Rating Curve= 0
Exp/Cntr=0.3,0.1

Type RM Length L Ch R = 1,133493,587,511,501
BEGIN DESCRIPTION:
Fourth Creek 210.0
END DESCRIPTION:
XS GIS Cut Line= 3
      1446317.53       754846.81      1446015.41       753769.06
      1445897.19       753389.65
#Sta/Elev= 30
  3880.7  810.33  3943.6  811.03  4042.7  808.59  4076.4  805.23  4103.8  792.28
  4142.0  791.23  4167.2  786.36  4306.6  787.19  4330.8  782.66  4347.0  782.74
  4382.9  777.49  4401.2  779.55  4463.7  776.81  4772.3  780.57  4948.4  781.21
  4970.3  781.24  4980.1  773.49  4990.4  771.93  5017.7  773.08  5031.6  781.21
  5048.4  783.57  5063.5  781.22  5077.9  783.11  5087.3  787.86  5097.5  796.45
  5113.3  805.53  5146.1  817.50  5176.0  824.11  5247.7  826.63  5397.4  836.27
#Mann=6,-1,0
  3880.7    0.13       0  4772.3    0.09       0  4948.4    0.14       0
  4970.3   0.045       0  5031.6    0.13       0  5176.0    0.14       0
#XS Ineff=2,0
    0.00 4457.40  831.75               0
Permanent Ineff=
       F       F
Bank Sta=4970.3,5031.6
XS Rating Curve= 0
Exp/Cntr=0.3,0.1

Type RM Length L Ch R = 1,132982,551,560,561
BEGIN DESCRIPTION:
Fourth Creek 209.0
END DESCRIPTION:
XS GIS Cut Line= 3
      1447153.72       754578.24      1446447.11       753508.23
      1446336.07       753250.83
#Sta/Elev= 30
  3715.2  807.02  3741.7  806.01  3764.4  800.71  3819.2  796.01  4001.6  789.52
  4143.3  778.55  4267.4  776.90  4627.9  778.52  4782.7  778.74  4868.8  778.65
  4891.2  778.26  4920.3  778.38  4934.9  784.03  4940.7  787.55  4956.4  790.38
  4961.4  789.03  4970.3  779.58  4980.1  771.83  4990.4  770.27  5017.7  771.42
  5024.7  774.68  5024.8  779.55  5027.8  782.86  5044.3  786.15  5062.3  798.56
  5087.9  811.89  5109.2  815.94  5191.4  832.95  5231.4  837.58  5277.8  838.36
#Mann=9,-1,0
  3715.2    0.12       0  4627.9    0.09       0  4782.7    0.13       0
  4868.8    0.09       0  4891.2    0.08       0  4934.9    0.13       0
  4970.3   0.042       0  5024.8    0.13       0  5109.2    0.08       0
#XS Ineff=2,0
    0.00 4322.50  835.94               0
Permanent Ineff=
       F       F
Bank Sta=4970.3,5024.8
XS Rating Curve= 0
Exp/Cntr=0.3,0.1

Type RM Length L Ch R = 1,132422,619,626,609
BEGIN DESCRIPTION:
Fourth Creek 208.0
END DESCRIPTION:
XS GIS Cut Line= 5
      1447699.25       753985.95      1447062.87       753462.81
      1446975.65       753330.19      1446936.89       753228.11
      1446626.80       753136.38
#Sta/Elev= 30
  4009.6  800.01  4136.7  795.83  4354.0  793.35  4509.0  780.32  4584.5  778.25
  4618.2  777.60  4646.7  776.47  4672.9  780.25  4692.7  782.36  4706.2  777.61
  4760.8  776.64  4846.8  776.71  4896.6  777.36  4933.9  778.29  4950.4  782.08
  4969.1  781.80  4972.9  779.77  4990.8  771.79  4991.2  770.45  5007.9  769.76
  5021.9  779.77  5048.9  781.71  5065.4  784.57  5077.2  789.58  5089.7  789.82
  5147.8  794.37  5194.0  798.47  5240.0  804.94  5322.1  812.77  5424.7  817.75
#Mann=15,-1,0
  4009.6    0.13       0  4584.5     0.1       0  4618.2   0.035       0
  4646.7    0.09       0  4672.9    0.12       0  4760.8    0.09       0
  4846.8    0.12       0  4896.6    0.08       0  4933.9    0.13       0
  4972.9   0.045       0  5021.9    0.13       0  5089.7    0.11       0
  5147.8    0.08       0  5240.0    0.13       0  5322.1    0.08       0
Bank Sta=4972.9,5021.9
XS Rating Curve= 0
Exp/Cntr=0.3,0.1

Type RM Length L Ch R = 1,131796,407,507,523
BEGIN DESCRIPTION:
Fourth Creek 207.0
END DESCRIPTION:
XS GIS Cut Line= 5
      1447789.66       753898.70      1447731.52       753330.19
      1447476.33       752968.40      1447382.66       752868.27
      1447124.21       752761.66
#Sta/Elev= 30
  3986.1  796.52  4106.6  785.84  4185.5  785.35  4249.6  782.02  4268.0  778.56
  4300.5  775.99  4498.8  775.87  4554.3  775.79  4588.4  777.62  4612.8  776.42
  4693.7  775.51  4887.6  775.57  4931.0  776.61  4948.9  780.83  4958.2  781.08
  4966.7  780.95  4972.9  777.13  4991.2  768.94  5007.9  768.25  5021.9  777.13
  5069.2  782.16  5081.4  789.82  5097.1  795.13  5129.1  808.54  5147.3  809.10
  5161.9  810.99  5271.0  813.87  5372.4  820.59  5405.9  820.55  5417.0  820.70
#Mann=14,-1,0
  3986.1    0.13       0  4498.8   0.035       0  4554.3    0.09       0
  4588.4    0.12       0  4612.8    0.09       0  4693.7    0.12       0
  4887.6    0.08       0  4958.2    0.13       0  4972.9   0.045       0
  5021.9    0.13       0  5097.1    0.12       0  5147.3    0.08       0
  5271.0    0.14       0  5405.9    0.08       0
#XS Ineff=2,0
    0.00 4547.30  810.60               0
Permanent Ineff=
       F       F
Bank Sta=4972.9,5021.9
XS Rating Curve= 0
Exp/Cntr=0.5,0.3

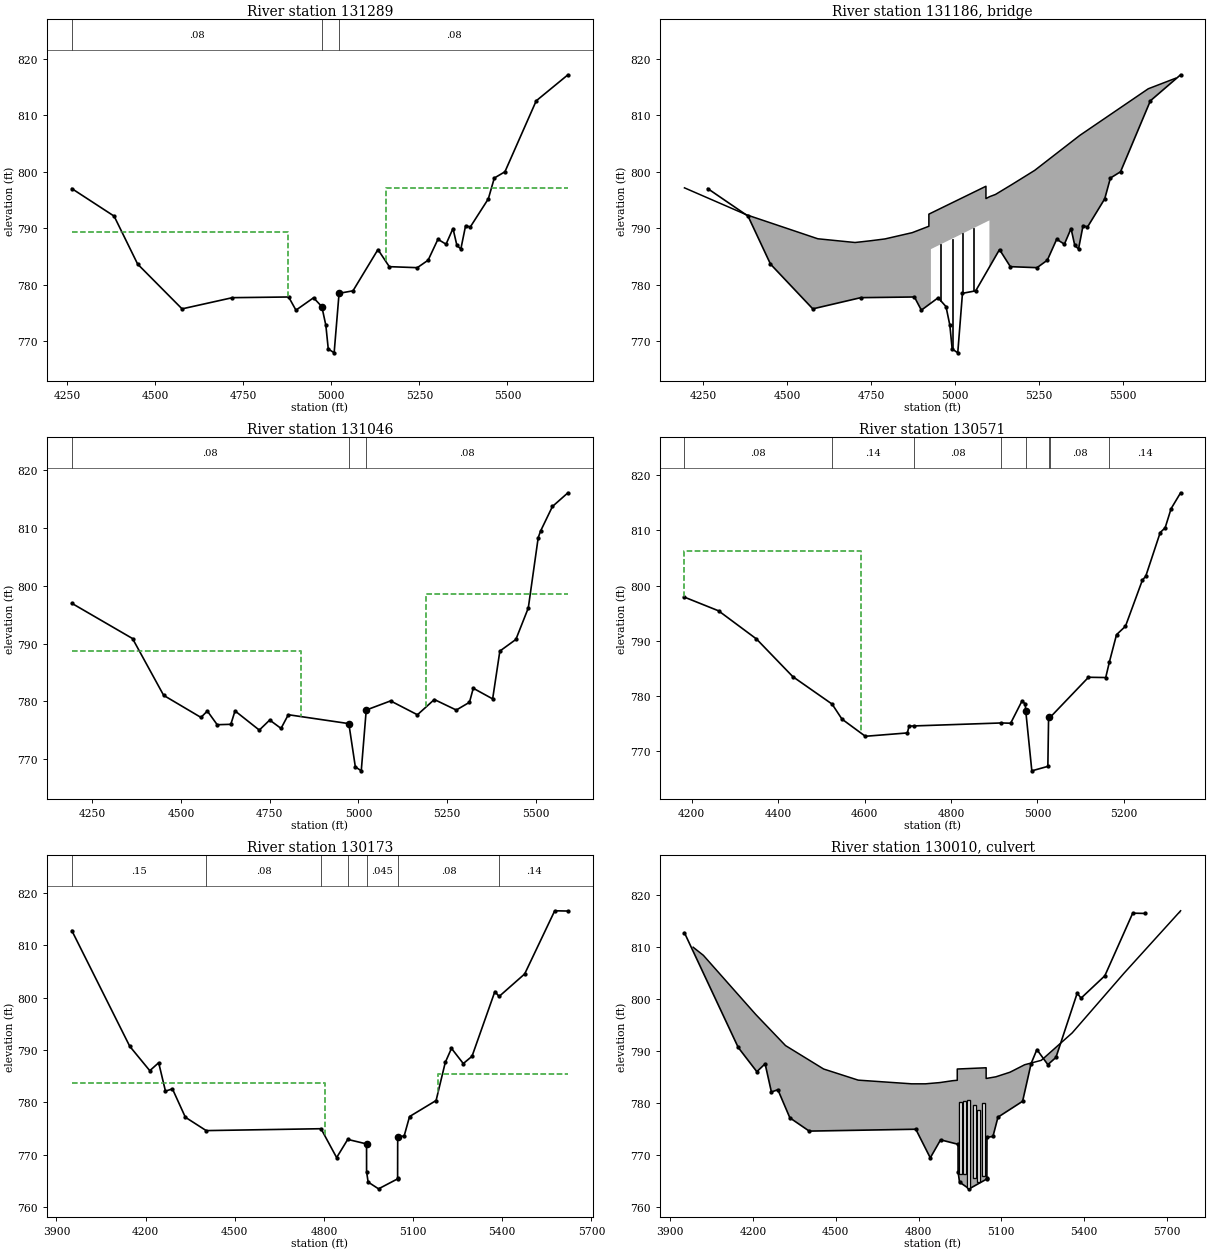
Type RM Length L Ch R = 1,131289,347,243,246
BEGIN DESCRIPTION:
I-77 (FC) us
END DESCRIPTION:
XS GIS Cut Line= 5
      1448083.60       753523.33      1447989.94       753229.40
      1447951.17       752799.79      1447944.71       752473.54
      1447996.40       752134.32
#Sta/Elev= 30
  4262.7  797.02  4382.9  792.15  4449.8  783.67  4575.9  775.76  4718.9  777.74
  4878.7  777.86  4899.4  775.53  4949.4  777.72  4972.9  776.16  4984.3  772.87
  4991.2  768.68  5007.9  767.99  5021.9  778.51  5061.4  778.95  5132.3  786.24
  5164.6  783.22  5244.1  783.04  5274.8  784.36  5302.7  788.06  5325.7  787.19
  5345.5  789.96  5356.6  786.97  5367.8  786.34  5381.3  790.47  5394.5  790.22
  5445.9  795.21  5462.8  798.88  5493.0  799.99  5581.9  812.53  5672.0  817.13
#Mann=3,-1,0
  4262.7    0.08       0  4972.9   0.045       0  5021.9    0.08       0
#XS Ineff=2,0
    0.00 4876.40  789.33 5153.80    0.00  797.18
Permanent Ineff=
       F       F
Bank Sta=4972.9,5021.9
XS Rating Curve= 0
Exp/Cntr=0.5,0.3

Type RM Length L Ch R =3,131186,,,
BEGIN DESCRIPTION:
I-77 (FC) TOR
Structure ID: I_FC_09
Detailed Survey Structure
END DESCRIPTION:
Bridge Culvert--1,0,-1,-1,0
Deck Dist Width WeirC Skew NumUp NumDn MinLoCord MaxHiCord MaxSubmerge Is_Ogee
51.5,103,3,,21,21,,,,0,1,1,,,
  4193.4  4377.8  4590.8  4701.8  4746.9  4790.9  4872.2  4921.8  4921.8  4927.9
  4927.9  5091.9  5091.9  5102.3  5102.3  5120.2  5170.4  5237.2  5371.6  5575.6
  5657.6
  797.15  792.40  788.15  787.49  787.79  788.12  789.23  790.36  792.50  792.68
  792.68  797.43  795.25  795.58  795.58  795.98  797.78  800.24  806.42  814.66
  816.53
  747.99  747.99  747.99  747.99  747.99  747.99  747.99  747.99  747.99  747.99
  786.32  791.10  791.10  791.40  747.99  747.99  747.99  747.99  747.99  747.99
  747.99
  4193.4  4377.8  4590.8  4701.8  4746.9  4790.9  4872.2  4921.8  4921.8  4927.9
  4927.9  5091.9  5091.9  5102.3  5102.3  5120.2  5170.4  5237.2  5371.6  5575.6
  5657.6
  797.15  792.40  788.15  787.49  787.79  788.12  789.23  790.36  792.50  792.68
  792.68  797.43  795.25  795.58  795.58  795.98  797.78  800.24  806.42  814.66
  816.53
  747.99  747.99  747.99  747.99  747.99  747.99  747.99  747.99  747.99  747.99
  786.32  791.10  791.10  791.40  747.99  747.99  747.99  747.99  747.99  747.99
  747.99
Pier Skew, UpSta & Num, DnSta & Num=,4957.8,2,4957.8,2,0,0,0,0,0
       3       3
  777.41  787.19
       3       3
  778.90  787.19
Pier Skew, UpSta & Num, DnSta & Num=,4990.8,2,4990.8,2,0,0,0,0,0
       3       3
  770.02  788.15
       3       3
  771.51  788.15
Pier Skew, UpSta & Num, DnSta & Num=,5022.9,2,5022.9,2,0,0,0,0,0
       3       3
  778.09  789.09
       3       3
  779.58  789.09
Pier Skew, UpSta & Num, DnSta & Num=,5055.1,2,5055.1,2,0,0,0,0,0
       3       3
  779.12  790.03
       3       3
  780.61  790.03
Abutment Skew #Up #Dn=,2,2
  4927.9  4949.4
  786.32  777.72
  4927.9  4949.4
  786.32  779.21
Abutment Skew #Up #Dn=,2,2
  5061.4  5102.3
  778.95  791.40
  5061.4  5102.3
  780.44  791.40
BR Coef=1,1,0,1.25,0,,,0.8,0,2,0,
WSPro=,,,, 1 ,,,, 0 ,,,, 0 ,,,,-1 ,-1 ,-1 , 0 , 0 , 0 , 0 , 0
BC Design=,,0,,0,,,,,,

Type RM Length L Ch R = 1,131046,487,475,472
BEGIN DESCRIPTION:
I-77 (FC) ds
END DESCRIPTION:
XS GIS Cut Line= 5
      1448144.98       753523.38      1448180.52       753264.94
      1448177.29       752728.72      1448164.37       752360.48
      1448080.43       752144.17
#Sta/Elev= 30
  4192.5  796.97  4363.6  790.87  4451.3  781.04  4556.4  777.22  4574.3  778.33
  4602.1  775.96  4640.5  776.03  4652.3  778.35  4720.7  775.03  4750.0  776.77
  4781.9  775.32  4802.4  777.69  4972.9  776.15  4991.2  768.67  5007.9  767.98
  5021.9  778.50  5090.5  780.08  5166.1  777.68  5213.7  780.32  5275.6  778.50
  5312.7  779.84  5323.4  782.27  5378.0  780.43  5398.3  788.70  5443.4  790.71
  5478.4  796.16  5506.3  808.32  5512.8  809.44  5546.4  813.72  5590.1  816.09
#Mann=3,-1,0
  4192.5    0.08       0  4972.9   0.045       0  5021.9    0.08       0
#XS Ineff=2,0
    0.00 4839.40  788.78 5190.80    0.00  798.53
Permanent Ineff=
       F       F
Bank Sta=4972.9,5021.9
XS Rating Curve= 0
Exp/Cntr=0.5,0.3

Type RM Length L Ch R = 1,130571,577,398,351
BEGIN DESCRIPTION:
Fourth Creek 204.0
END DESCRIPTION:
XS GIS Cut Line= 4
      1448713.77       753465.56      1448642.44       752654.43
      1448630.38       752469.20      1448522.94       752366.95
#Sta/Elev= 30
  4183.1  797.89  4262.0  795.41  4349.6  790.31  4433.9  783.46  4524.8  778.48
  4547.6  775.76  4601.7  772.64  4699.0  773.25  4702.8  774.48  4714.5  774.52
  4916.8  775.06  4938.0  775.01  4963.8  778.98  4971.7  778.56  4972.9  777.26
  4987.0  766.37  5024.1  767.18  5025.8  776.16  5029.9  776.12  5118.1  783.35
  5158.0  783.30  5166.6  786.16  5183.0  791.08  5203.7  792.61  5242.9  800.99
  5250.6  801.68  5284.1  809.62  5295.5  810.47  5309.3  813.95  5331.3  816.83
#Mann=8,-1,0
  4183.1    0.08       0  4524.8    0.14       0  4714.5    0.08       0
  4916.8    0.14       0  4972.9   0.045       0  5025.8    0.14       0
  5029.9    0.08       0  5166.6    0.14       0
#XS Ineff=2,0
    0.00 4592.00  806.30 5422.50    0.00  809.24
Permanent Ineff=
       F       F
Bank Sta=4972.9,5025.8
XS Rating Curve= 0
Exp/Cntr=0.5,0.3

Type RM Length L Ch R = 1,130173,220,224,229
BEGIN DESCRIPTION:
Davie Ave (FC) us
END DESCRIPTION:
XS GIS Cut Line= 6
      1449957.10       753100.17      1449621.19       752841.78
      1449175.42       752664.12      1448952.54       752599.51
      1448791.03       752557.52      1448497.04       752337.84
#Sta/Elev= 30
  3951.5  812.80  4146.5  790.72  4214.0  786.06  4243.9  787.58  4266.7  782.16
  4290.2  782.59  4333.7  777.18  4403.8  774.63  4790.2  774.99  4842.7  769.48
  4880.1  772.95  4943.4  772.09  4943.5  766.81  4948.7  764.81  4983.8  763.52
  5047.8  765.42  5047.9  765.63  5048.2  773.44  5069.9  773.60  5088.1  777.31
  5177.4  780.37  5208.3  787.64  5229.2  790.32  5268.9  787.42  5298.3  788.81
  5375.2  801.16  5389.4  800.22  5475.5  804.52  5576.6  816.57  5621.1  816.52
#Mann=7,-1,0
  3951.5    0.15       0  4403.8    0.08       0  4790.2    0.14       0
  4880.1    0.08       0  4943.4   0.045       0  5048.2    0.08       0
  5389.4    0.14       0
#XS Ineff=2,0
    0.00 4804.10  783.73 5183.20    0.00  785.50
Permanent Ineff=
       F       F
Bank Sta=4943.4,5048.2
XS Rating Curve= 0
Exp/Cntr=0.5,0.3

Type RM Length L Ch R =2,130010,,,
BEGIN DESCRIPTION:
Davie Ave (FC) TOR
Structure ID: I_FC_07
Detailed Survey Structure
END DESCRIPTION:
Bridge Culvert--1,0,-1,-1,0
Deck Dist Width WeirC Skew NumUp NumDn MinLoCord MaxHiCord MaxSubmerge Is_Ogee
142,42,3,,21,21,,,,0,1,1,,,
  3982.9  4020.1  4210.1  4317.9  4456.1  4581.4  4775.2  4825.1  4877.5  4923.6
  4940.5  4940.5  5045.2  5045.2  5080.4  5131.9  5184.7  5245.1  5357.0  5545.3
  5750.2
  810.02  808.46  797.07  791.09  786.58  784.44  783.73  783.73  783.97  784.33
  784.41  786.58  786.82  784.76  785.08  785.97  787.40  788.25  793.52  805.03
  817.03
  743.52  743.52  743.52  743.52  743.52  743.52  743.52  743.52  743.52  743.52
  743.52  743.52  743.52  743.52  743.52  743.52  743.52  743.52  743.52  743.52
  743.52
  3982.9  4020.1  4210.1  4317.9  4456.1  4581.4  4775.2  4825.1  4877.5  4923.6
  4940.5  4940.5  5045.2  5045.2  5080.4  5131.9  5184.7  5245.1  5357.0  5545.3
  5750.2
  810.02  808.46  797.07  791.09  786.58  784.44  783.73  783.73  783.97  784.33
  784.41  786.58  786.82  784.76  785.08  785.97  787.40  788.25  793.52  805.03
  817.03
  743.99  743.99  743.99  743.99  743.99  743.99  743.99  743.99  743.99  743.99
  743.99  743.99  743.99  743.99  743.99  743.99  743.99  743.99  743.99  743.99
  743.99
Culvert=2,14,11,42,0.012,0.4,1,8,1,766.3,4951.6,766.06,4951.6,Culvert #1,0,142
Culvert Bottom n=0.012
Culvert Bottom Depth=0
Culvert Depth Blocked=0
Culvert=2,14,11,42,0.012,0.4,1,8,1,766.43,4967.1,766.26,4967.1,Culvert #2,0,142
Culvert Bottom n=0.012
Culvert Bottom Depth=0
Culvert Depth Blocked=0
Culvert=2,17,11,42,0.012,0.4,1,8,1,763.59,4982.1,764,4982.1,Culvert #3,0,142
Culvert Bottom n=0.012
Culvert Bottom Depth=0
Culvert Depth Blocked=0
Culvert=2,14,11,42,0.012,0.4,1,8,1,765.67,5001.9,765.55,5001.9,Culvert #4,0,142
Culvert Bottom n=0.012
Culvert Bottom Depth=0
Culvert Depth Blocked=0
Culvert=2,14,11,42,0.012,0.4,1,8,1,764.78,5018.3,766.23,5018.3,Culvert #5,0,142
Culvert Bottom n=0.012
Culvert Bottom Depth=0
Culvert Depth Blocked=0
Culvert=2,14,11,42,0.012,0.4,1,8,1,766.08,5035.7,766.19,5035.7,Culvert #6,0,142
Culvert Bottom n=0.012
Culvert Bottom Depth=0
Culvert Depth Blocked=0
BC Design=,,0,,0,,,,,,

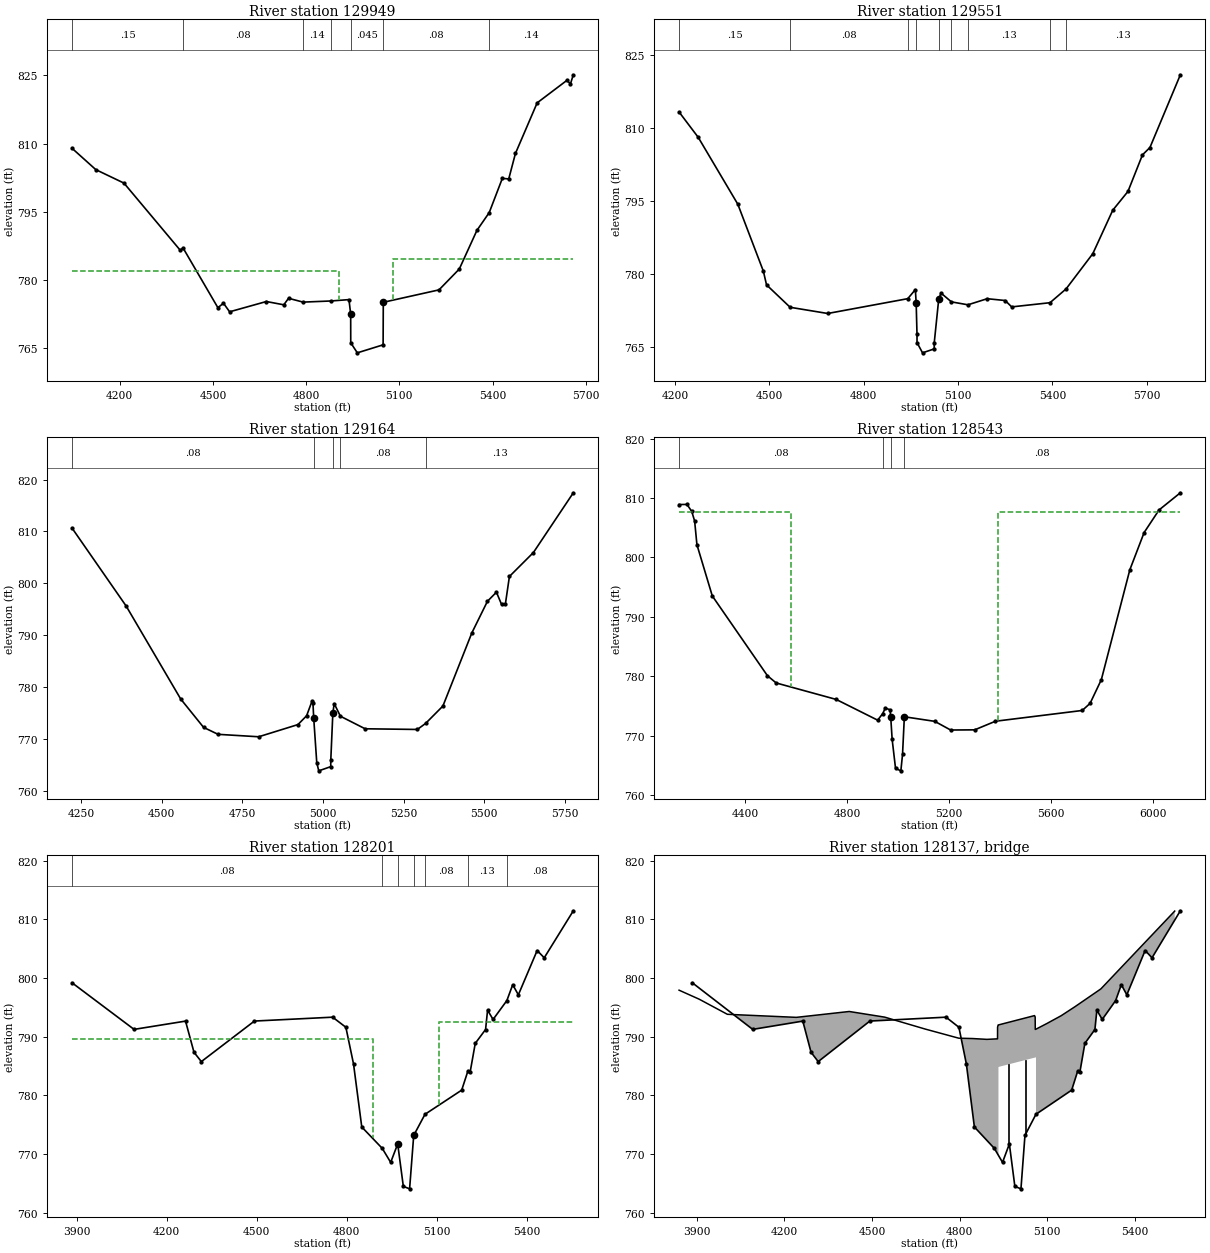
Type RM Length L Ch R = 1,129949,397,398,376
BEGIN DESCRIPTION:
Davie Ave (FC) ds
END DESCRIPTION:
XS GIS Cut Line= 5
      1450076.69       753051.77      1449685.80       752757.79
      1449036.52       752509.07      1448826.56       752463.84
      1448655.40       752334.66
#Sta/Elev= 30
  4046.5  808.95  4123.0  804.26  4213.6  801.30  4395.0  786.52  4403.8  787.05
  4515.9  773.92  4534.0  774.89  4553.7  773.01  4672.0  775.27  4728.1  774.55
  4743.4  775.98  4790.2  775.14  4880.1  775.39  4937.9  775.69  4943.4  772.51
  4943.6  766.20  4964.8  763.99  5047.8  765.75  5048.4  775.10  5227.7  777.83
  5293.0  782.41  5349.8  790.91  5389.4  794.82  5431.6  802.34  5452.2  802.22
  5473.7  807.81  5543.7  818.94  5639.2  823.87  5650.9  823.13  5660.1  825.11
#Mann=7,-1,0
  4046.5    0.15       0  4403.8    0.08       0  4790.2    0.14       0
  4880.1    0.08       0  4943.4   0.045       0  5048.4    0.08       0
  5389.4    0.14       0
#XS Ineff=2,0
    0.00 4906.10  782.00 5081.20    0.00  784.62
Permanent Ineff=
       F       F
Bank Sta=4943.4,5048.4
XS Rating Curve= 0
Exp/Cntr=0.5,0.3

Type RM Length L Ch R = 1,129551,408,387,360
BEGIN DESCRIPTION:
Fourth Creek 202.0
END DESCRIPTION:
XS GIS Cut Line= 3
      1450264.99       752753.78      1449566.54       752364.06
      1448893.47       751944.03
#Sta/Elev= 30
  4213.2  813.29  4274.0  808.10  4399.9  794.38  4481.1  780.65  4491.2  777.84
  4566.2  773.24  4685.6  771.97  4940.1  775.01  4964.2  776.87  4966.8  774.07
  4969.4  767.69  4969.5  766.00  4987.0  763.90  5024.1  764.71  5024.3  766.01
  5038.6  775.01  5046.0  776.14  5078.8  774.35  5131.3  773.75  5192.5  775.00
  5249.7  774.63  5270.3  773.32  5392.1  774.18  5443.1  777.00  5528.2  784.24
  5591.6  793.15  5639.9  797.00  5686.0  804.50  5709.7  806.00  5806.4  820.92
#Mann=9,-1,0
  4213.2    0.15       0  4566.2    0.08       0  4940.1    0.13       0
  4966.8   0.045       0  5038.6    0.13       0  5078.8    0.11       0
  5131.3    0.13       0  5392.1    0.11       0  5443.1    0.13       0
Bank Sta=4966.8,5038.6
XS Rating Curve= 0
Exp/Cntr=0.3,0.1

Type RM Length L Ch R = 1,129164,600,621,625
BEGIN DESCRIPTION:
Fourth Creek 201.0
END DESCRIPTION:
XS GIS Cut Line= 3
      1450507.84       752348.86      1449794.28       752050.28
      1449075.61       751746.62
#Sta/Elev= 30
  4222.3  810.63  4390.2  795.58  4558.9  777.69  4630.0  772.20  4674.9  770.86
  4800.8  770.39  4922.5  772.74  4949.3  774.44  4966.1  777.26  4969.0  776.89
  4971.3  774.03  4980.8  765.39  4987.0  763.82  5024.1  764.63  5024.3  765.93
  5030.6  774.93  5034.8  776.79  5054.1  774.35  5130.7  771.93  5292.5  771.80
  5318.1  772.96  5371.8  776.32  5461.4  790.41  5509.8  796.52  5537.7  798.27
  5553.4  795.93  5565.4  795.98  5577.9  801.30  5652.3  805.92  5776.0  817.44
#Mann=5,-1,0
  4222.3    0.08       0  4971.3   0.045       0  5030.6    0.08       0
  5054.1    0.08       0  5318.1    0.13       0
Bank Sta=4971.3,5030.6
XS Rating Curve= 0
Exp/Cntr=0.3,0.1

Type RM Length L Ch R = 1,128543,350,342,445
BEGIN DESCRIPTION:
Fourth Creek 200.0
END DESCRIPTION:
XS GIS Cut Line= 5
      1450741.68       752072.44      1450454.23       751712.11
      1450106.04       751513.72      1449733.55       751343.67
      1449037.19       751359.86
#Sta/Elev= 30
  4139.4  808.91  4170.5  808.93  4189.1  807.76  4200.5  806.14  4209.5  802.15
  4269.8  793.53  4486.3  780.10  4520.6  778.88  4756.1  776.11  4918.9  772.62
  4938.6  773.71  4949.0  774.66  4967.8  774.36  4970.3  773.08  4975.8  769.39
  4989.1  764.51  5010.0  764.09  5016.6  766.86  5023.7  773.19  5143.1  772.42
  5205.4  770.96  5299.8  770.99  5381.4  772.44  5721.9  774.25  5752.7  775.44
  5796.9  779.43  5908.8  797.93  5964.9  804.20  6023.5  808.00  6107.1  810.89
#Mann=4,-1,0
  4139.4    0.08       0  4938.6    0.13       0  4970.3   0.042       0
  5023.7    0.08       0
#XS Ineff=2,0
    0.00 4580.40  807.60 5393.00    0.00  807.60
Permanent Ineff=
       F       F
Bank Sta=4970.3,5023.7
XS Rating Curve= 0
Exp/Cntr=0.5,0.3

Type RM Length L Ch R = 1,128201,134,128,132
BEGIN DESCRIPTION:
Simonton Rd (FC) us
END DESCRIPTION:
XS GIS Cut Line= 4
      1451093.31       751960.66      1450961.14       751722.23
      1450116.40       751097.75      1449878.03       750843.82
#Sta/Elev= 30
  3884.5  799.18  4091.3  791.24  4262.9  792.65  4291.1  787.34  4315.6  785.75
  4492.6  792.66  4753.4  793.32  4797.5  791.60  4823.0  785.36  4850.5  774.61
  4918.9  770.96  4946.9  768.58  4970.3  771.72  4989.1  764.49  5010.0  764.07
  5023.7  773.17  5061.3  776.77  5183.7  780.89  5203.9  784.07  5211.7  783.92
  5228.9  788.86  5263.3  791.22  5270.0  794.52  5288.3  792.93  5334.3  796.15
  5353.8  798.85  5372.6  797.13  5435.3  804.68  5458.9  803.44  5555.9  811.45
#Mann=7,-1,0
  3884.5    0.08       0  4918.9    0.13       0  4970.3   0.042       0
  5023.7    0.13       0  5061.3    0.08       0  5203.9    0.13       0
  5334.3    0.08       0
#XS Ineff=2,0
    0.00 4886.50  789.56 5108.00    0.00  792.49
Permanent Ineff=
       F       F
Bank Sta=4970.3,5023.7
XS Rating Curve= 0
Exp/Cntr=0.5,0.3

Type RM Length L Ch R =3,128137,,,
BEGIN DESCRIPTION:
Simonton Rd (FC) TOR
Structure ID: I_FC_06
Detailed Survey Structure
END DESCRIPTION:
Bridge Culvert--1,0,-1,-1,0
Deck Dist Width WeirC Skew NumUp NumDn MinLoCord MaxHiCord MaxSubmerge Is_Ogee
46.5,35,3,,27,27,,,,0,1,1,,,
  3839.1  3908.2  4004.5  4240.7  4421.9  4543.2  4681.0  4796.9  4844.9  4893.1
  4929.8  4929.8  4929.9  4931.9  4933.0  4933.0  5056.5  5058.7  5059.0  5059.0
  5061.5  5061.5  5098.3  5147.7  5195.4  5283.7  5536.6
  797.92  796.38  793.81  793.29  794.29  793.33  791.31  789.74  789.68  789.54
  789.63  789.99  791.62  791.99  792.00  792.00  793.59  793.35  791.54  791.23
  791.28  791.28  792.23  793.57  795.12  798.14  811.40
  744.07  744.07  744.07  744.07  744.07  744.07  744.07  744.07  744.07  744.07
  744.07  744.07  744.07  744.07  744.07  784.84  786.42  786.44  786.45  786.45
  786.48  744.07  744.07  744.07  744.07  744.07  744.07
  3839.1  3908.2  4004.5  4240.7  4421.9  4543.2  4681.0  4796.9  4844.9  4893.1
  4929.8  4929.8  4929.9  4931.9  4933.0  4933.0  5056.5  5058.7  5059.0  5059.0
  5061.5  5061.5  5098.3  5147.7  5195.4  5283.7  5536.6
  797.92  796.38  793.81  793.29  794.29  793.33  791.31  789.74  789.68  789.54
  789.63  789.99  791.62  791.99  792.00  792.00  793.59  793.35  791.54  791.23
  791.28  791.28  792.23  793.57  795.12  798.14  811.40
  744.07  744.07  744.07  744.07  744.07  744.07  744.07  744.07  744.07  744.07
  744.07  744.07  744.07  744.07  744.07  784.84  786.42  786.44  786.45  786.45
  786.48  744.07  744.07  744.07  744.07  744.07  744.07
Pier Skew, UpSta & Num, DnSta & Num=,4965.8,2,4965.8,2,0,0,0,0,0
     3.5     3.5
  773.36  785.26
     3.5     3.5
  773.25  785.26
Pier Skew, UpSta & Num, DnSta & Num=,5024.5,2,5024.5,2,0,0,0,0,0
     3.5     3.5
  773.29  786.01
     3.5     3.5
  773.18  786.01
Abutment Skew #Up #Dn=,2,2
  4933.0  4933.1
  784.84  781.25
  4933.0  4933.1
  784.84  781.14
BR Coef=1,1,0,1.25,0,,,0.8,0,2,0,
WSPro=,,,, 1 ,,,, 0 ,,,, 0 ,,,,-1 ,-1 ,-1 , 0 , 0 , 0 , 0 , 0
BC Design=,,0,,0,,,,,,

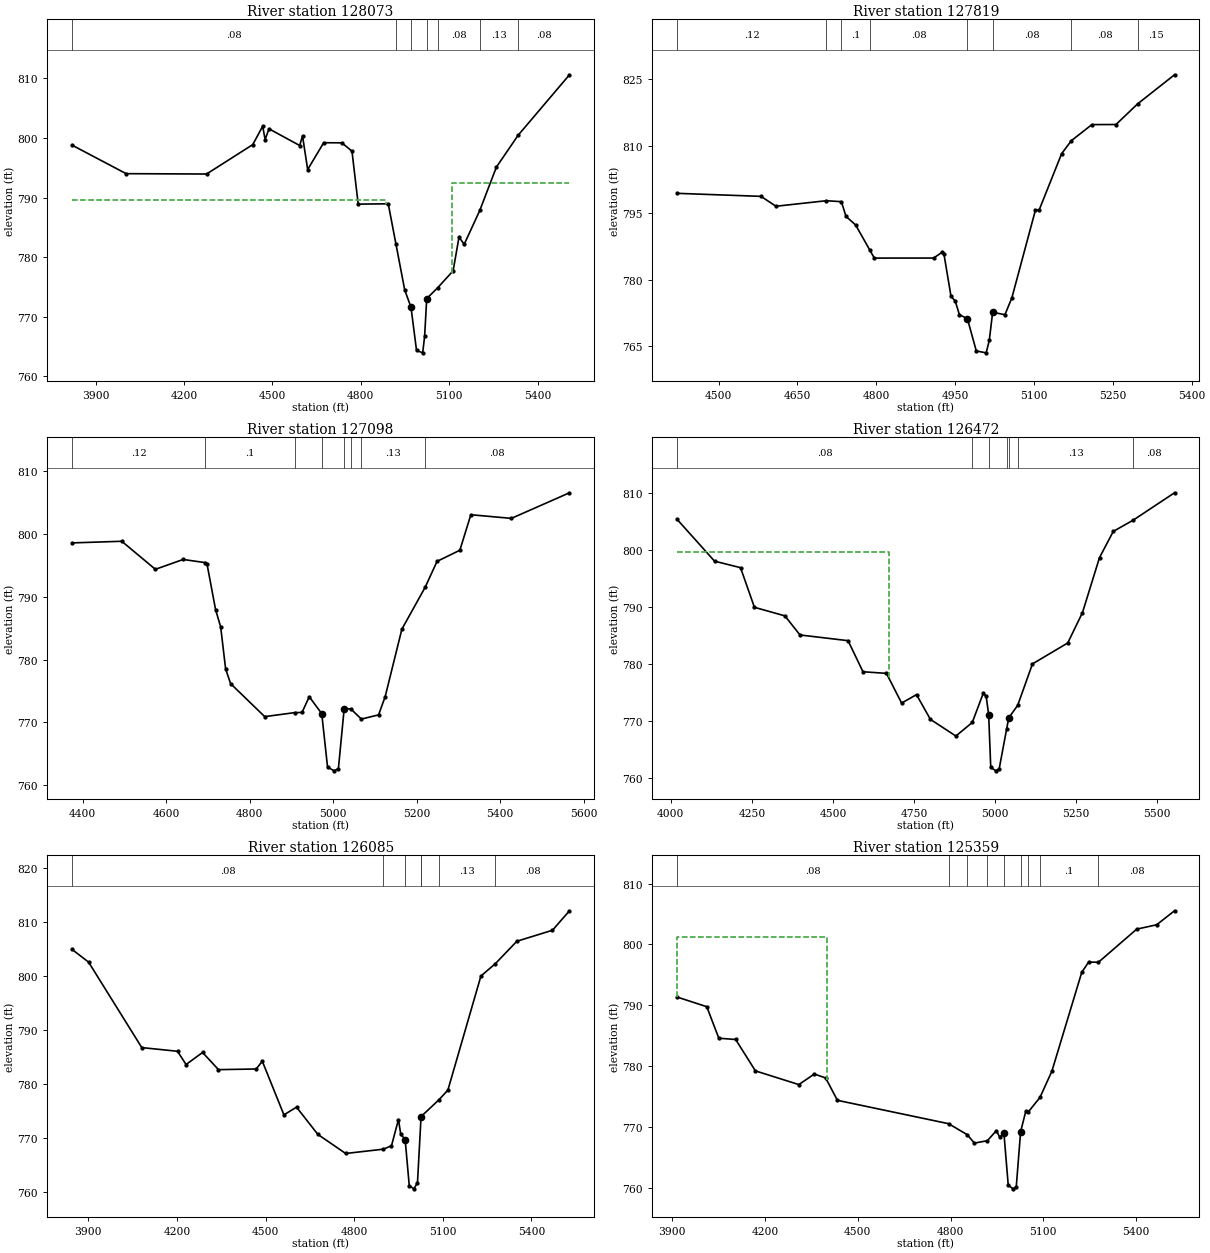
Type RM Length L Ch R = 1,128073,252,254,259
BEGIN DESCRIPTION:
Simonton Rd (FC) ds
END DESCRIPTION:
XS GIS Cut Line= 6
      1451114.03       751947.71      1451044.06       751698.91
      1450536.18       751250.63      1450261.51       751048.51
      1450126.77       750981.14      1449909.13       750836.05
#Sta/Elev= 30
  3819.2  798.80  4003.5  794.00  4276.4  793.94  4433.2  798.87  4466.9  801.95
  4475.2  799.72  4488.3  801.52  4592.5  798.72  4602.2  800.32  4619.6  794.69
  4674.0  799.19  4735.5  799.17  4770.0  797.78  4791.1  788.89  4893.1  788.95
  4918.9  782.29  4949.0  774.51  4970.3  771.61  4989.1  764.38  5010.0  763.96
  5016.6  766.73  5023.7  773.06  5061.3  774.89  5113.3  777.71  5133.3  783.36
  5151.0  782.16  5203.9  787.84  5260.3  795.11  5334.3  800.46  5508.3  810.58
#Mann=7,-1,0
  3819.2    0.08       0  4918.9    0.13       0  4970.3   0.042       0
  5023.7    0.13       0  5061.3    0.08       0  5203.9    0.13       0
  5334.3    0.08       0
#XS Ineff=2,0
    0.00 4886.50  789.56 5108.00    0.00  792.49
Permanent Ineff=
       F       F
Bank Sta=4970.3,5023.7
XS Rating Curve= 0
Exp/Cntr=0.5,0.3

Type RM Length L Ch R = 1,127819,683,721,735
BEGIN DESCRIPTION:
Fourth Creek 198.0
END DESCRIPTION:
XS GIS Cut Line= 3
      1450915.14       751252.72      1450463.10       750883.86
      1450199.11       750634.33
#Sta/Elev= 30
  4420.6  799.34  4580.6  798.66  4609.1  796.44  4704.8  797.68  4733.6  797.47
  4742.2  794.18  4760.7  792.23  4787.6  786.61  4796.2  784.81  4909.0  784.82
  4925.7  786.16  4928.8  785.62  4942.1  776.21  4950.1  775.20  4958.0  772.12
  4973.3  771.20  4990.2  763.97  5009.0  763.55  5014.9  766.32  5021.3  772.65
  5044.7  772.11  5057.9  775.90  5102.6  795.53  5110.0  795.67  5152.6  808.25
  5171.1  811.16  5210.1  814.76  5256.0  814.78  5296.9  819.39  5367.3  825.94
#Mann=8,-1,0
  4420.6    0.12       0  4704.8    0.08       0  4733.6     0.1       0
  4787.6    0.08       0  4973.3   0.042       0  5021.3    0.08       0
  5171.1    0.08       0  5296.9    0.15       0
Bank Sta=4973.3,5021.3
XS Rating Curve= 0
Exp/Cntr=0.3,0.1

Type RM Length L Ch R = 1,127098,619,626,634
BEGIN DESCRIPTION:
Fourth Creek 197.0
END DESCRIPTION:
XS GIS Cut Line= 4
      1451070.61       751263.53      1451128.47       750771.76
      1451059.76       750536.71      1450799.42       750167.89
#Sta/Elev= 30
  4374.4  798.59  4493.9  798.85  4574.4  794.38  4640.8  795.95  4693.5  795.45
  4698.1  795.20  4718.5  787.96  4730.7  785.20  4742.6  778.49  4754.6  776.15
  4836.2  770.90  4908.1  771.54  4925.4  771.56  4942.8  774.07  4972.7  771.38
  4986.6  762.86  5002.4  762.26  5012.6  762.61  5026.4  772.15  5042.3  772.13
  5067.5  770.51  5108.8  771.18  5124.6  774.09  5164.6  784.84  5220.4  791.53
  5248.8  795.65  5303.4  797.42  5329.7  803.08  5426.8  802.50  5565.9  806.58
#Mann=8,-1,0
  4374.4    0.12       0  4693.5     0.1       0  4908.1    0.13       0
  4972.7   0.042       0  5026.4    0.13       0  5042.3    0.08       0
  5067.5    0.13       0  5220.4    0.08       0
Bank Sta=4972.7,5026.4
XS Rating Curve= 0
Exp/Cntr=0.3,0.1

Type RM Length L Ch R = 1,126472,400,387,378
BEGIN DESCRIPTION:
Fourth Creek 196.0
END DESCRIPTION:
XS GIS Cut Line= 5
      1451551.53       751426.31      1451764.90       750952.57
      1451699.81       750504.17      1451692.43       750406.27
      1451855.31       749972.60
#Sta/Elev= 30
  4019.0  805.43  4135.1  798.06  4215.2  796.92  4258.0  789.97  4352.0  788.47
  4398.5  785.12  4546.7  784.12  4592.7  778.67  4665.0  778.39  4711.8  773.18
  4757.7  774.66  4800.4  770.33  4879.1  767.40  4929.6  769.78  4963.3  774.87
  4972.5  774.38  4980.2  771.12  4986.6  761.90  5002.4  761.30  5012.6  761.65
  5035.3  768.56  5042.3  770.61  5069.7  772.79  5115.2  780.05  5224.0  783.72
  5269.4  789.05  5321.9  798.69  5364.4  803.28  5426.3  805.27  5553.1  810.05
#Mann=7,-1,0
  4019.0    0.08       0  4929.6    0.13       0  4980.2   0.042       0
  5035.3    0.08       0  5042.3    0.13       0  5069.7    0.13       0
  5426.3    0.08       0
#XS Ineff=2,0
    0.00 4672.20  799.72               0
Permanent Ineff=
       F       F
Bank Sta=4980.2,5042.3
XS Rating Curve= 0
Exp/Cntr=0.3,0.1

Type RM Length L Ch R = 1,126085,717,726,729
BEGIN DESCRIPTION:
Fourth Creek 195.0 (Survey)
END DESCRIPTION:
XS GIS Cut Line= 4
      1452090.35       751534.73      1452130.13       750630.73
      1452072.27       750395.69      1451913.16       749882.20
#Sta/Elev= 30
  3844.5  804.93  3901.0  802.56  4081.2  786.74  4202.1  786.06  4231.1  783.61
  4287.0  785.84  4340.8  782.66  4468.4  782.78  4489.2  784.22  4562.3  774.30
  4605.0  775.72  4677.4  770.67  4771.4  767.15  4899.4  767.95  4926.5  768.58
  4950.1  773.43  4957.8  770.71  4972.7  769.73  4986.6  761.21  5002.4  760.61
  5014.5  761.77  5026.6  773.98  5026.7  773.99  5087.0  777.08  5117.4  778.88
  5229.2  799.98  5278.0  802.26  5350.8  806.41  5471.5  808.45  5529.0  812.05
#Mann=7,-1,0
  3844.5    0.08       0  4899.4    0.13       0  4972.7   0.042       0
  5026.6    0.13       0  5026.7    0.08       0  5087.0    0.13       0
  5278.0    0.08       0
Bank Sta=4972.7,5026.6
XS Rating Curve= 0
Exp/Cntr=0.3,0.1

Type RM Length L Ch R = 1,125359,627,690,732
BEGIN DESCRIPTION:
Fourth Creek 194.0
END DESCRIPTION:
XS GIS Cut Line= 5
      1452835.27       751292.10      1452860.58       750724.39
      1452773.79       750207.29      1452755.71       750135.33
      1452376.01       749907.14
#Sta/Elev= 30
  3914.7  791.35  4011.4  789.75  4050.3  784.57  4104.8  784.36  4168.8  779.20
  4309.1  776.95  4359.2  778.68  4395.9  778.04  4434.0  774.36  4793.6  770.52
  4854.0  768.71  4877.1  767.33  4919.1  767.72  4948.3  769.38  4958.8  768.32
  4972.7  768.93  4986.6  760.41  5002.4  759.81  5012.6  760.16  5026.6  769.18
  5043.2  772.53  5050.9  772.42  5089.2  774.83  5127.8  779.15  5224.4  795.40
  5246.7  797.09  5278.4  797.06  5402.2  802.50  5466.8  803.22  5524.5  805.52
#Mann=9,-1,0
  3914.7    0.08       0  4793.6    0.13       0  4854.0    0.08       0
  4919.1    0.13       0  4972.7   0.042       0  5026.6    0.13       0
  5050.9    0.08       0  5089.2     0.1       0  5278.4    0.08       0
#XS Ineff=2,0
    0.00 4399.60  801.15               0
Permanent Ineff=
       F       F
Bank Sta=4972.7,5026.6
XS Rating Curve= 0
Exp/Cntr=0.3,0.1