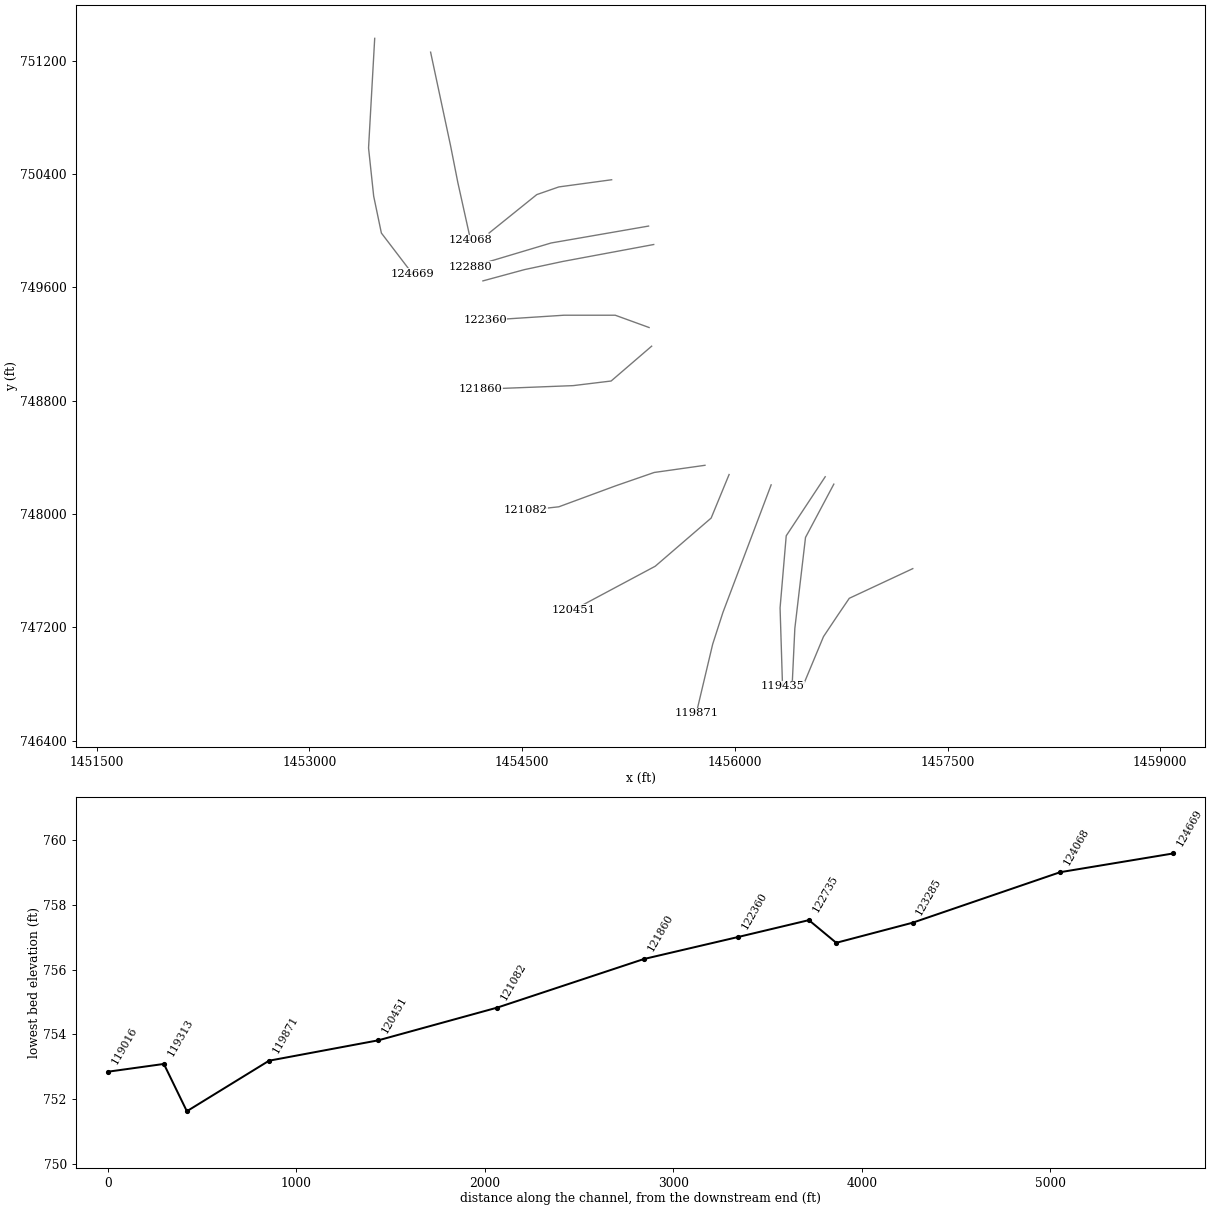
HEC-RAS study Fourth Creek.prj: Fourth Creek Detailed Study

--- Fourth Creek.g01 (geometry) --- (continued)

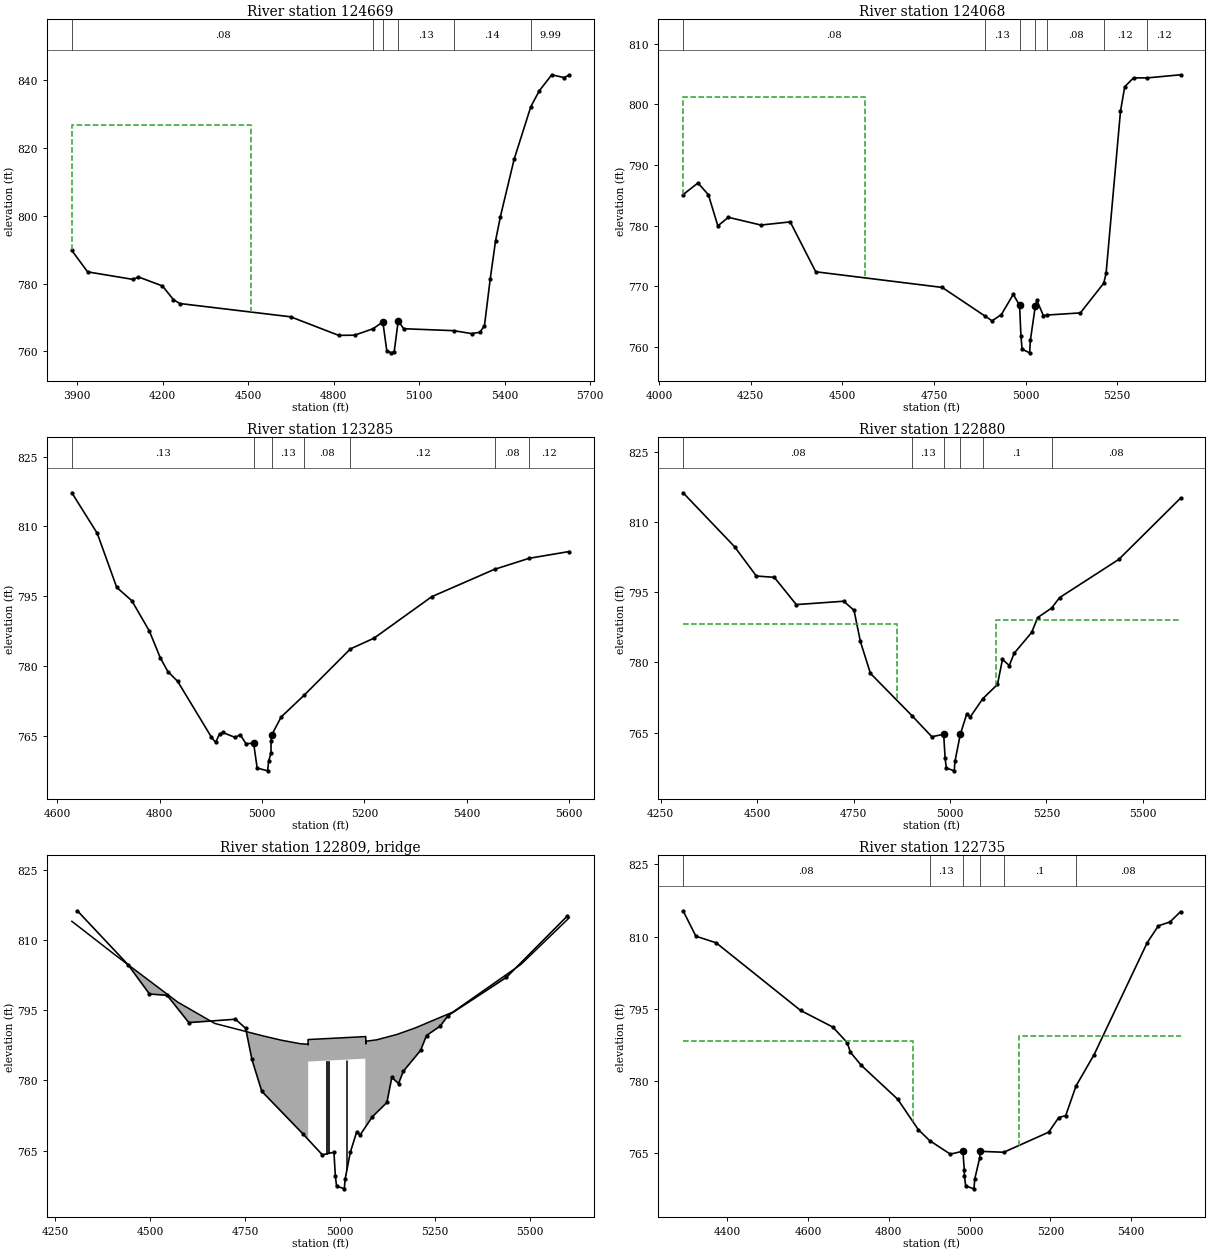
Type RM Length L Ch R = 1,124669,581,601,603
BEGIN DESCRIPTION:
Fourth Creek 192.0
END DESCRIPTION:
XS GIS Cut Line= 5
      1453460.85       751357.23      1453417.46       750583.36
      1453453.62       750243.45      1453507.86       749983.09
      1453728.47       749693.76
#Sta/Elev= 30
  3880.7  789.76  3936.0  783.46  4095.7  781.23  4114.3  781.96  4198.7  779.31
  4237.4  775.27  4259.4  774.13  4649.0  770.21  4817.6  764.74  4873.6  764.79
  4938.8  766.71  4972.7  768.71  4986.6  760.19  5002.4  759.59  5012.6  759.94
  5026.6  768.98  5045.9  766.70  5222.3  766.12  5284.2  765.26  5313.4  765.66
  5329.5  767.56  5349.7  781.35  5368.5  792.62  5385.3  799.68  5433.9  816.71
  5492.2  832.13  5521.8  836.81  5565.8  841.55  5608.5  840.73  5627.4  841.45
#Mann=6,-1,0
  3880.7    0.08       0  4938.8    0.13       0  4972.7   0.042       0
  5026.6    0.13       0  5222.3    0.14       0  5492.2    9.99       0
#XS Ineff=2,0
    0.00 4511.30  826.73               0
Permanent Ineff=
       F       F
Bank Sta=4972.7,5026.6
XS Rating Curve= 0
Exp/Cntr=0.3,0.1

Type RM Length L Ch R = 1,124068,1014,783,714
BEGIN DESCRIPTION:
Fourth Creek 191.0
END DESCRIPTION:
XS GIS Cut Line= 4
      1453855.00       751259.60      1453996.04       750597.83
      1454046.66       750341.08      1454137.06       749932.49
#Sta/Elev= 30
  4065.7  785.11  4106.2  787.03  4134.7  785.09  4160.5  779.95  4189.0  781.37
  4278.0  780.09  4357.9  780.61  4427.5  772.38  4772.5  769.80  4887.8  765.13
  4908.5  764.29  4933.8  765.32  4966.3  768.66  4983.5  766.83  4987.2  761.75
  4990.4  759.61  5010.9  759.01  5012.8  761.05  5026.6  766.81  5030.6  767.69
  5048.3  765.15  5059.6  765.25  5149.3  765.60  5213.0  770.50  5219.4  772.12
  5258.7  798.86  5270.2  802.90  5294.4  804.38  5330.5  804.36  5422.5  804.88
#Mann=7,-1,0
  4065.7    0.08       0  4887.8    0.13       0  4983.5   0.042       0
  5026.6    0.13       0  5059.6    0.08       0  5213.0    0.12       0
  5330.5    0.12       0
#XS Ineff=2,0
    0.00 4561.00  801.27               0
Permanent Ineff=
       F       F
Bank Sta=4983.5,5026.6
XS Rating Curve= 0
Exp/Cntr=0.3,0.1

Type RM Length L Ch R = 1,123285,405,405,407
BEGIN DESCRIPTION:
Fourth Creek 190.0
END DESCRIPTION:
XS GIS Cut Line= 4
      1455131.45       750359.16      1454759.03       750308.54
      1454603.54       750254.30      1454267.21       749983.06
#Sta/Elev= 30
  4628.1  817.25  4677.8  808.52  4715.8  796.91  4745.4  794.03  4779.7  787.50
  4800.9  781.79  4815.8  778.81  4835.0  776.69  4900.8  764.73  4909.3  763.55
  4916.8  765.39  4923.0  765.71  4947.4  764.63  4957.3  765.22  4968.5  763.29
  4983.5  763.39  4990.4  758.05  5010.9  757.45  5012.8  759.49  5017.4  761.30
  5017.6  763.92  5019.2  765.25  5037.4  769.04  5082.2  773.71  5172.7  783.67
  5218.7  785.97  5331.9  794.91  5454.5  800.79  5522.3  803.16  5600.7  804.62
#Mann=7,-1,0
  4628.1    0.13       0  4983.5   0.042       0  5019.2    0.13       0
  5082.2    0.08       0  5172.7    0.12       0  5454.5    0.08       0
  5522.3    0.12       0
Bank Sta=4983.5,5019.2
XS Rating Curve= 0
Exp/Cntr=0.5,0.3

Type RM Length L Ch R = 1,122880,152,145,146
BEGIN DESCRIPTION:
Broad St (FC) us
END DESCRIPTION:
XS GIS Cut Line= 3
      1455391.81       750032.26      1454704.79       749912.94
      1454137.09       749742.99
#Sta/Elev= 30
  4307.8  816.26  4441.2  804.74  4497.7  798.47  4544.3  798.19  4601.3  792.36
  4724.2  793.08  4751.0  791.14  4767.5  784.48  4793.5  777.67  4900.9  768.65
  4952.9  764.11  4983.5  764.65  4987.2  759.57  4990.4  757.43  5010.9  756.83
  5012.8  758.87  5026.6  764.63  5043.6  769.05  5052.2  768.32  5084.8  772.24
  5123.0  775.29  5135.9  780.63  5153.7  779.34  5166.3  781.96  5211.6  786.41
  5227.4  789.60  5263.7  791.64  5284.0  793.85  5437.6  802.02  5597.7  815.11
#Mann=6,-1,0
  4307.8    0.08       0  4900.9    0.13       0  4983.5   0.042       0
  5026.6    0.13       0  5084.8     0.1       0  5263.7    0.08       0
#XS Ineff=2,0
    0.00 4863.20  788.32 5118.60    0.00  789.17
Permanent Ineff=
       F       F
Bank Sta=4983.5,5026.6
XS Rating Curve= 0
Exp/Cntr=0.5,0.3

Type RM Length L Ch R =3,122809,,,
BEGIN DESCRIPTION:
Broad St (FC) TOR
Structure ID: I_FC_05
Detailed Survey Structure
END DESCRIPTION:
Bridge Culvert--1,0,-1,-1,0
Deck Dist Width WeirC Skew NumUp NumDn MinLoCord MaxHiCord MaxSubmerge Is_Ogee
52.5,37,3,,23,23,,,,0,1,1,,,
  4293.3  4410.4  4571.9  4669.7  4792.7  4844.3  4894.0  4915.2  4915.2  4915.4
  4915.7  4915.7  5066.1  5066.1  5067.3  5067.5  5067.5  5096.0  5148.6  5197.6
  5297.0  5475.8  5603.3
  814.01  806.63  796.75  792.18  789.60  788.61  787.86  787.73  787.58  788.74
  788.74  788.74  789.37  789.37  789.37  787.80  788.37  788.68  789.81  791.22
  794.63  804.79  814.77
  736.83  736.83  736.83  736.83  736.83  736.83  736.83  736.83  736.83  736.83
  736.83  784.03  784.66  736.83  736.83  736.83  736.83  736.83  736.83  736.83
  736.83  736.83  736.83
  4293.3  4410.4  4571.9  4669.7  4792.7  4844.3  4894.0  4915.2  4915.2  4915.4
  4915.7  4915.7  5066.1  5066.1  5067.3  5067.5  5067.5  5096.0  5148.6  5197.6
  5297.0  5475.8  5603.3
  814.01  806.63  796.75  792.18  789.60  788.61  787.86  787.73  787.58  788.74
  788.74  788.74  789.37  789.37  789.37  787.80  788.37  788.68  789.81  791.22
  794.63  804.79  814.77
  736.83  736.83  736.83  736.83  736.83  736.83  736.83  736.83  736.83  736.83
  736.83  784.03  784.66  736.83  736.83  736.83  736.83  736.83  736.83  736.83
  736.83  736.83  736.83
Pier Skew, UpSta & Num, DnSta & Num=,4963.6,2,4963.6,2,0,0,0,0,0
       1       1
  764.05  784.23
       1       1
  764.75  784.23
Pier Skew, UpSta & Num, DnSta & Num=,4969.1,2,4969.1,2,0,0,0,0,0
       1       1
  763.70  784.25
       1       1
  764.40  784.25
Pier Skew, UpSta & Num, DnSta & Num=,5014.8,2,5014.8,2,0,0,0,0,0
       1       1
  759.49  784.44
       1       1
  760.19  784.44
Pier Skew, UpSta & Num, DnSta & Num=,5017.4,2,5017.4,2,0,0,0,0,0
       1       1
  760.68  784.45
       1       1
  761.38  784.45
BR Coef=1,1,0,1.25,0,,,0.8,0,2,0,
WSPro=,,,, 1 ,,,, 0 ,,,, 0 ,,,,-1 ,-1 ,-1 , 0 , 0 , 0 , 0 , 0
BC Design=,,0,,0,,,,,,

Type RM Length L Ch R = 1,122735,422,375,371
BEGIN DESCRIPTION:
Broad St (FC) ds
END DESCRIPTION:
XS GIS Cut Line= 4
      1455428.06       749902.10      1454787.96       749782.76
      1454516.76       749724.90      1454223.80       749645.33
#Sta/Elev= 30
  4290.5  815.36  4322.2  810.07  4372.3  808.70  4581.5  794.63  4661.4  791.17
  4696.7  787.96  4704.9  785.94  4731.5  783.24  4822.2  776.15  4872.8  769.87
  4900.9  767.58  4952.2  764.75  4983.5  765.35  4986.9  761.44  4987.2  760.27
  4990.4  758.13  5010.9  757.53  5012.8  759.57  5025.2  764.00  5026.6  765.33
  5084.8  765.14  5196.0  769.32  5220.8  772.36  5238.1  772.76  5263.7  778.94
  5308.3  785.42  5440.1  808.75  5467.6  812.23  5496.4  813.04  5522.5  815.18
#Mann=6,-1,0
  4290.5    0.08       0  4900.9    0.13       0  4983.5   0.042       0
  5026.6    0.13       0  5084.8     0.1       0  5263.7    0.08       0
#XS Ineff=2,0
    0.00 4860.20  788.37 5121.60    0.00  789.23
Permanent Ineff=
       F       F
Bank Sta=4983.5,5026.6
XS Rating Curve= 0
Exp/Cntr=0.5,0.3

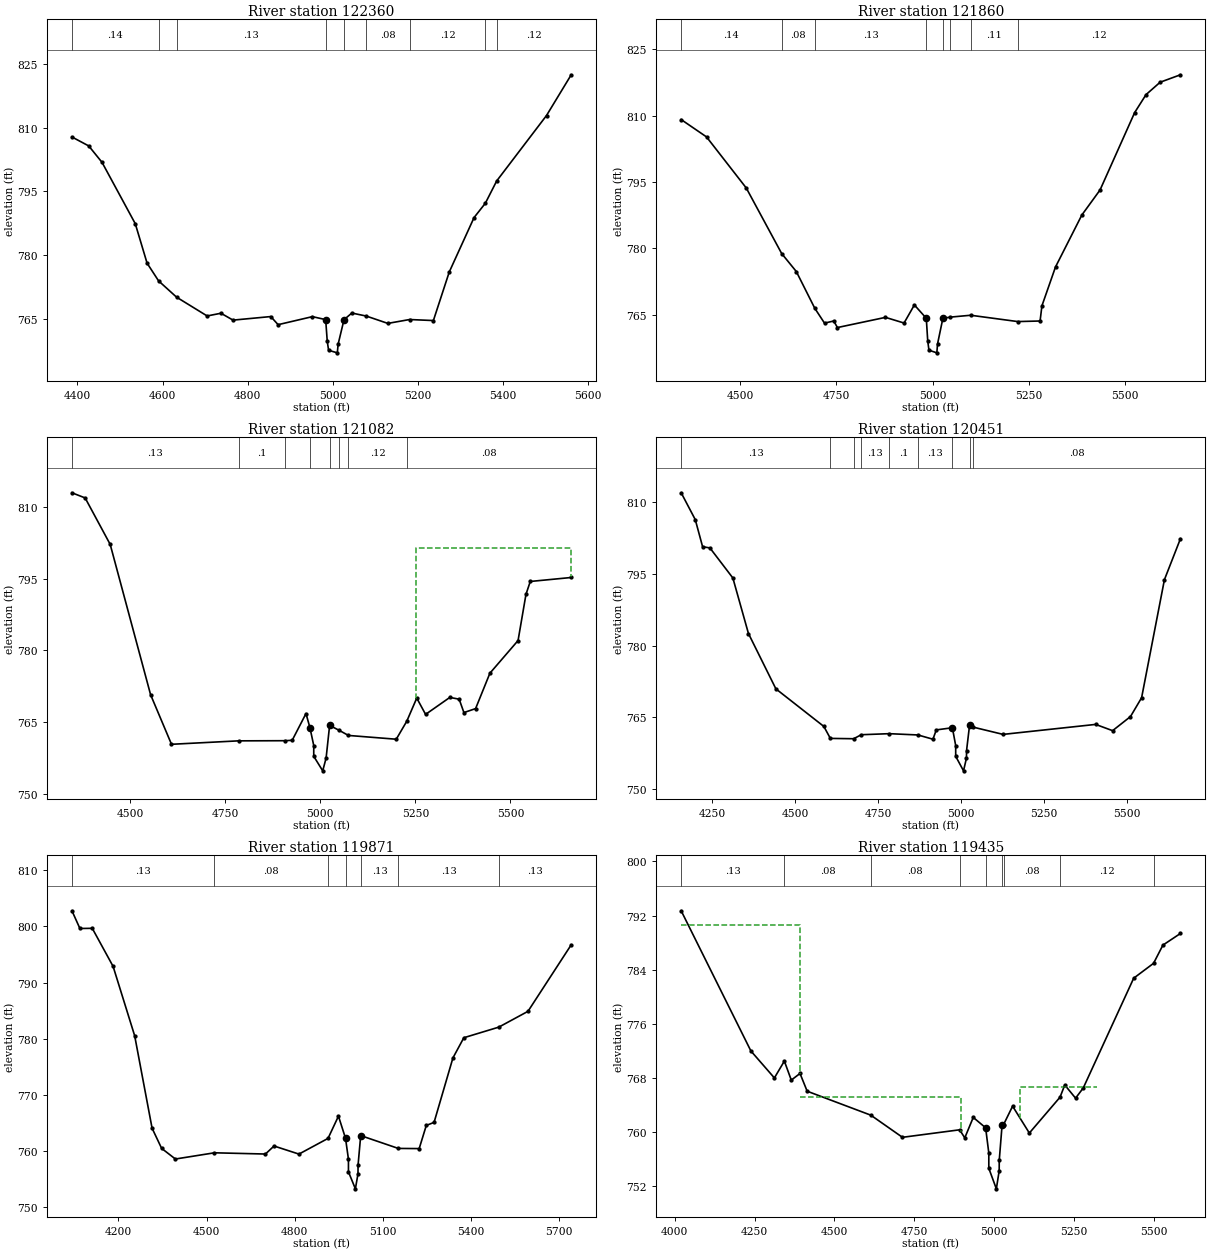
Type RM Length L Ch R = 1,122360,485,500,497
BEGIN DESCRIPTION:
Fourth Creek 188.0
END DESCRIPTION:
XS GIS Cut Line= 4
      1455395.44       749316.29      1455156.81       749403.07
      1454795.19       749403.07      1454238.30       749366.90
#Sta/Elev= 30
  4387.1  807.82  4426.6  805.71  4457.8  801.85  4536.0  787.40  4563.7  778.12
  4590.8  773.94  4633.1  770.11  4704.9  765.69  4737.3  766.33  4765.8  764.71
  4854.5  765.55  4871.7  763.64  4952.3  765.53  4983.5  764.83  4987.2  759.75
  4990.4  757.61  5010.9  757.01  5012.8  759.05  5026.6  764.81  5045.0  766.38
  5079.2  765.66  5129.6  763.94  5180.8  764.85  5236.7  764.61  5274.0  776.04
  5332.3  788.85  5358.8  792.22  5385.5  797.47  5502.6  812.87  5560.7  822.46
#Mann=9,-1,0
  4387.1    0.14       0  4590.8    0.08       0  4633.1    0.13       0
  4983.5   0.042       0  5026.6    0.13       0  5079.2    0.08       0
  5180.8    0.12       0  5358.8    0.08       0  5385.5    0.12       0
Bank Sta=4983.5,5026.6
XS Rating Curve= 0
Exp/Cntr=0.3,0.1

Type RM Length L Ch R = 1,121860,752,778,822
BEGIN DESCRIPTION:
Fourth Creek 187.0
END DESCRIPTION:
XS GIS Cut Line= 4
      1455413.55       749184.65      1455127.88       748938.76
      1454860.28       748906.21      1454209.36       748880.90
#Sta/Elev= 30
  4346.3  809.08  4412.2  805.16  4515.5  793.61  4607.6  778.78  4645.6  774.72
  4693.6  766.41  4718.9  763.05  4742.9  763.53  4752.5  762.05  4877.4  764.35
  4925.7  763.07  4952.5  767.16  4983.5  764.15  4987.2  759.07  4990.4  756.93
  5010.9  756.33  5012.8  758.37  5026.6  764.13  5046.3  764.41  5098.9  764.83
  5221.3  763.40  5279.3  763.53  5284.1  766.96  5319.4  775.75  5387.9  787.50
  5435.2  793.16  5525.2  810.67  5554.7  814.72  5591.3  817.52  5644.2  819.21
#Mann=8,-1,0
  4346.3    0.14       0  4607.6    0.08       0  4693.6    0.13       0
  4983.5   0.042       0  5026.6    0.13       0  5046.3    0.08       0
  5098.9    0.11       0  5221.3    0.12       0
Bank Sta=4983.5,5026.6
XS Rating Curve= 0
Exp/Cntr=0.3,0.1

Type RM Length L Ch R = 1,121082,570,631,656
BEGIN DESCRIPTION:
Fourth Creek 185.0
END DESCRIPTION:
XS GIS Cut Line= 5
      1455789.64       748343.91      1455431.63       748293.28
      1455160.42       748199.26      1454759.03       748051.00
      1454524.98       748025.00
#Sta/Elev= 30
  4347.7  812.96  4382.4  811.88  4448.2  802.17  4554.4  770.74  4609.3  760.38
  4785.5  761.10  4908.1  761.13  4926.5  761.22  4962.7  766.80  4973.1  763.85
  4983.1  760.12  4983.1  757.87  5006.7  754.83  5015.6  757.51  5024.8  764.33
  5049.6  763.31  5074.2  762.23  5199.9  761.44  5227.5  765.19  5253.8  770.04
  5277.0  766.63  5340.7  770.18  5365.2  769.81  5377.7  767.01  5408.4  767.84
  5446.0  775.24  5520.0  782.07  5540.8  791.73  5552.1  794.42  5659.7  795.25
#Mann=8,-1,0
  4347.7    0.13       0  4785.5     0.1       0  4908.1    0.13       0
  4973.1   0.042       0  5024.8    0.13       0  5049.6    0.13       0
  5074.2    0.12       0  5227.5    0.08       0
#XS Ineff=2,0
       0                 5253.10    0.00  801.47
Permanent Ineff=
       F       F
Bank Sta=4973.1,5024.8
XS Rating Curve= 0
Exp/Cntr=0.3,0.1

Type RM Length L Ch R = 1,120451,481,580,709
BEGIN DESCRIPTION:
Fourth Creek 184.0
END DESCRIPTION:
XS GIS Cut Line= 4
      1455959.57       748278.79      1455833.02       747971.45
      1455438.86       747631.54      1454863.92       747324.18
#Sta/Elev= 30
  4155.7  812.03  4198.2  806.41  4220.3  800.73  4242.3  800.49  4311.5  794.19
  4358.5  782.56  4441.2  770.98  4585.8  763.11  4605.3  760.61  4675.6  760.54
  4698.5  761.38  4782.7  761.60  4869.3  761.33  4914.5  760.44  4924.7  762.39
  4973.1  762.84  4983.1  759.11  4983.1  756.86  5006.7  753.82  5015.6  756.50
  5015.8  758.03  5024.8  763.32  5033.8  763.00  5125.9  761.45  5404.9  763.54
  5456.0  762.23  5509.9  765.18  5543.4  769.12  5612.2  793.84  5660.5  802.42
#Mann=9,-1,0
  4155.7    0.13       0  4605.3    0.08       0  4675.6    0.13       0
  4698.5    0.13       0  4782.7     0.1       0  4869.3    0.13       0
  4973.1   0.042       0  5024.8    0.13       0  5033.8    0.08       0
Bank Sta=4973.1,5024.8
XS Rating Curve= 0
Exp/Cntr=0.3,0.1

Type RM Length L Ch R = 1,119871,352,436,459
BEGIN DESCRIPTION:
Fourth Creek 183.0
END DESCRIPTION:
XS GIS Cut Line= 4
      1456256.11       748205.80      1455916.19       747305.73
      1455843.86       747081.53      1455728.16       746593.04
#Sta/Elev= 30
  4041.8  802.80  4068.9  799.64  4111.0  799.67  4181.9  792.88  4255.4  780.49
  4314.6  764.01  4347.1  760.41  4394.0  758.51  4526.9  759.62  4700.5  759.40
  4729.8  760.83  4814.6  759.39  4913.6  762.19  4949.1  766.16  4973.1  762.21
  4983.1  758.48  4983.1  756.23  5006.7  753.19  5015.6  755.87  5015.8  757.40
  5024.8  762.69  5152.9  760.40  5223.9  760.37  5248.1  764.50  5274.6  765.05
  5338.8  776.55  5375.9  780.15  5494.9  782.04  5594.3  784.86  5741.5  796.73
#Mann=7,-1,0
  4041.8    0.13       0  4526.9    0.08       0  4913.6    0.13       0
  4973.1   0.042       0  5024.8    0.13       0  5152.9    0.13       0
  5494.9    0.13       0
Bank Sta=4973.1,5024.8
XS Rating Curve= 0
Exp/Cntr=0.5,0.3

Type RM Length L Ch R = 1,119435,161,122,135
BEGIN DESCRIPTION:
Greenbriar Rd (FC) us
END DESCRIPTION:
XS GIS Cut Line= 4
      1456637.26       748262.94      1456362.41       747846.33
      1456319.02       747337.19      1456336.38       746784.65
#Sta/Elev= 30
  4020.1  792.70  4238.4  771.99  4311.9  768.01  4343.1  770.50  4364.8  767.69
  4392.1  768.67  4414.5  766.05  4613.8  762.51  4712.8  759.24  4891.8  760.35
  4907.9  759.16  4934.4  762.18  4973.1  760.65  4983.1  756.92  4983.1  754.67
  5006.7  751.63  5015.6  754.31  5015.8  755.84  5024.8  761.13  5029.1  761.10
  5057.6  763.84  5110.0  759.87  5206.1  765.17  5220.9  766.97  5254.7  765.02
  5278.8  766.53  5436.6  782.74  5498.8  784.94  5528.1  787.63  5583.0  789.35
#Mann=9,-1,0
  4020.1    0.13       0  4343.1    0.08       0  4613.8    0.08       0
  4891.8    0.13       0  4973.1   0.042       0  5024.8    0.13       0
  5029.1    0.08       0  5206.1    0.12       0  5498.8    0.13       0
#XS Ineff=3,-1
 4392.90 4896.80  765.20 5081.70 5321.00  766.74 4021.10 4392.80  790.56
Permanent Ineff=
       F       F       F
Bank Sta=4973.1,5024.8
XS Rating Curve= 0
Exp/Cntr=0.5,0.3

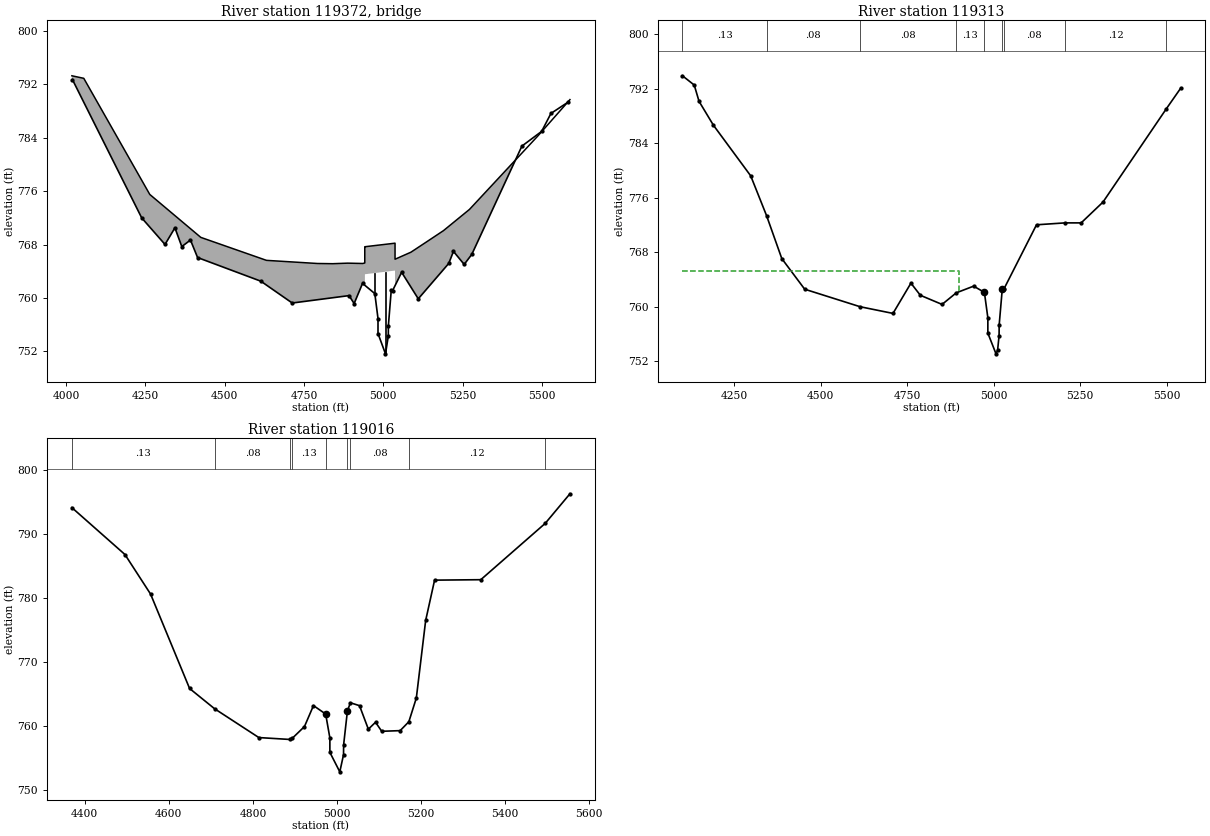
Type RM Length L Ch R =3,119372,,,
BEGIN DESCRIPTION:
Greenbriar Rd (FC) TOR
Structure ID: I_FC_03
Detailed Survey Structure
END DESCRIPTION:
Bridge Culvert--1,0,-1,-1,0
Deck Dist Width WeirC Skew NumUp NumDn MinLoCord MaxHiCord MaxSubmerge Is_Ogee
45,36,3,,23,23,,,,0,1,1,,,
  4018.4  4055.9  4263.9  4424.7  4631.6  4792.3  4840.3  4887.8  4935.2  4941.4
  4941.4  4941.8  4941.8  5036.7  5036.7  5036.8  5036.8  5086.8  5136.2  5189.4
  5271.4  5486.9  5588.0
  793.27  792.89  775.50  769.07  765.63  765.16  765.13  765.21  765.16  765.24
  767.67  767.67  767.67  768.20  768.20  768.20  765.80  766.85  768.40  770.08
  773.26  784.26  789.70
  731.63  731.63  731.63  731.63  731.63  731.63  731.63  731.63  731.63  731.63
  731.63  731.63  763.55  764.10  731.63  731.63  731.63  731.63  731.63  731.63
  731.63  731.63  731.63
  4018.4  4055.9  4263.9  4424.7  4631.6  4792.3  4840.3  4887.8  4935.2  4941.4
  4941.4  4941.8  4941.8  5036.7  5036.7  5036.8  5036.8  5086.8  5136.2  5189.4
  5271.4  5486.9  5588.0
  793.27  792.89  775.50  769.07  765.63  765.16  765.13  765.21  765.16  765.24
  767.67  767.67  767.67  768.20  768.20  768.20  765.80  766.85  768.40  770.08
  773.26  784.26  789.70
  731.63  731.63  731.63  731.63  731.63  731.63  731.63  731.63  731.63  731.63
  731.63  731.63  763.55  764.10  731.63  731.63  731.63  731.63  731.63  731.63
  731.63  731.63  731.63
Pier Skew, UpSta & Num, DnSta & Num=,4972,2,4972,2,0,0,0,0,0
       1       1
  760.93  763.73
       1       1
  762.39  763.73
Pier Skew, UpSta & Num, DnSta & Num=,5006.7,2,5006.7,2,0,0,0,0,0
       1       1
  751.63  763.92
       1       1
  753.09  763.92
BR Coef=1,1,0,1.25,0,,,0.8,0,2,0,
WSPro=,,,, 1 ,,,, 0 ,,,, 0 ,,,,-1 ,-1 ,-1 , 0 , 0 , 0 , 0 , 0
BC Design=,,0,,0,,,,,,

Type RM Length L Ch R = 1,119313,363,297,279
BEGIN DESCRIPTION:
Greenbriar Rd (FC) ds
END DESCRIPTION:
XS GIS Cut Line= 4
      1456697.99       748210.84      1456498.38       747834.76
      1456423.16       747192.54      1456405.81       746825.13
#Sta/Elev= 30
  4100.0  793.88  4134.1  792.52  4148.0  790.13  4189.5  786.63  4297.4  779.20
  4343.1  773.38  4387.3  767.06  4453.5  762.57  4613.8  760.00  4708.8  759.02
  4760.7  763.46  4787.9  761.68  4850.7  760.34  4891.8  762.04  4942.0  763.02
  4973.1  762.11  4983.1  758.38  4983.1  756.13  5006.7  753.09  5011.3  753.62
  5015.6  755.77  5015.8  757.30  5024.8  762.59  5029.1  762.56  5123.8  772.02
  5206.1  772.30  5252.9  772.30  5316.0  775.35  5498.8  789.01  5540.2  792.02
#Mann=9,-1,0
  4100.0    0.13       0  4343.1    0.08       0  4613.8    0.08       0
  4891.8    0.13       0  4973.1   0.042       0  5024.8    0.13       0
  5029.1    0.08       0  5206.1    0.12       0  5498.8    0.13       0
#XS Ineff=2,0
    0.00 4900.80  765.20 5077.70    0.00  760.01
Permanent Ineff=
       F       F
Bank Sta=4973.1,5024.8
XS Rating Curve= 0
Exp/Cntr=0.5,0.3

Type RM Length L Ch R = 1,119016,510,523,536
BEGIN DESCRIPTION:
Fourth Creek 181.0
END DESCRIPTION:
XS GIS Cut Line= 5
      1457254.73       747614.63      1456807.04       747405.24
      1456727.76       747288.66      1456625.17       747134.76
      1456485.25       746798.49
#Sta/Elev= 30
  4369.6  794.09  4495.8  786.77  4556.7  780.60  4649.5  765.86  4708.9  762.70
  4814.2  758.20  4889.1  757.90  4893.6  758.08  4922.7  759.92  4944.1  763.19
  4973.1  761.87  4983.1  758.14  4983.1  755.89  5006.7  752.85  5015.6  755.53
  5015.8  757.06  5024.8  762.35  5031.9  763.63  5053.6  763.18  5074.6  759.51
  5091.7  760.59  5106.4  759.18  5150.2  759.28  5170.9  760.67  5188.7  764.37
  5210.9  776.48  5232.1  782.77  5342.0  782.84  5495.2  791.63  5554.0  796.25
#Mann=9,-1,0
  4369.6    0.13       0  4708.9    0.08       0  4889.1    0.08       0
  4893.6    0.13       0  4973.1   0.042       0  5024.8    0.13       0
  5031.9    0.08       0  5170.9    0.12       0  5495.2    0.13       0
Bank Sta=4973.1,5024.8
XS Rating Curve= 0
Exp/Cntr=0.3,0.1