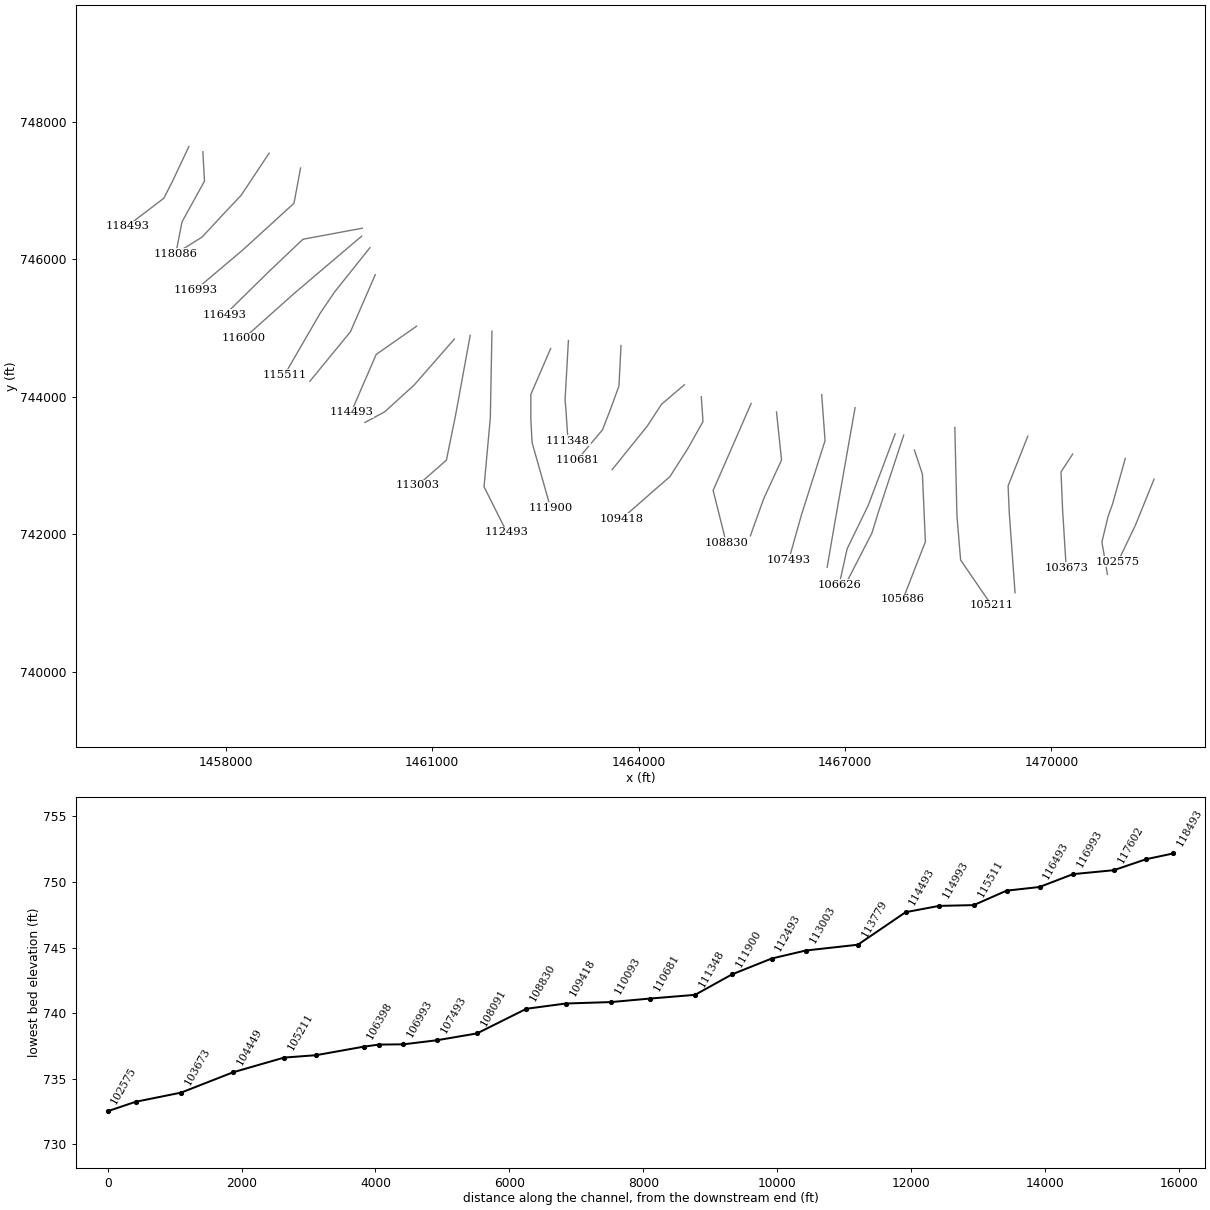
HEC-RAS study Fourth Creek.prj: Fourth Creek Detailed Study

--- Fourth Creek.g01 (geometry) --- (continued)

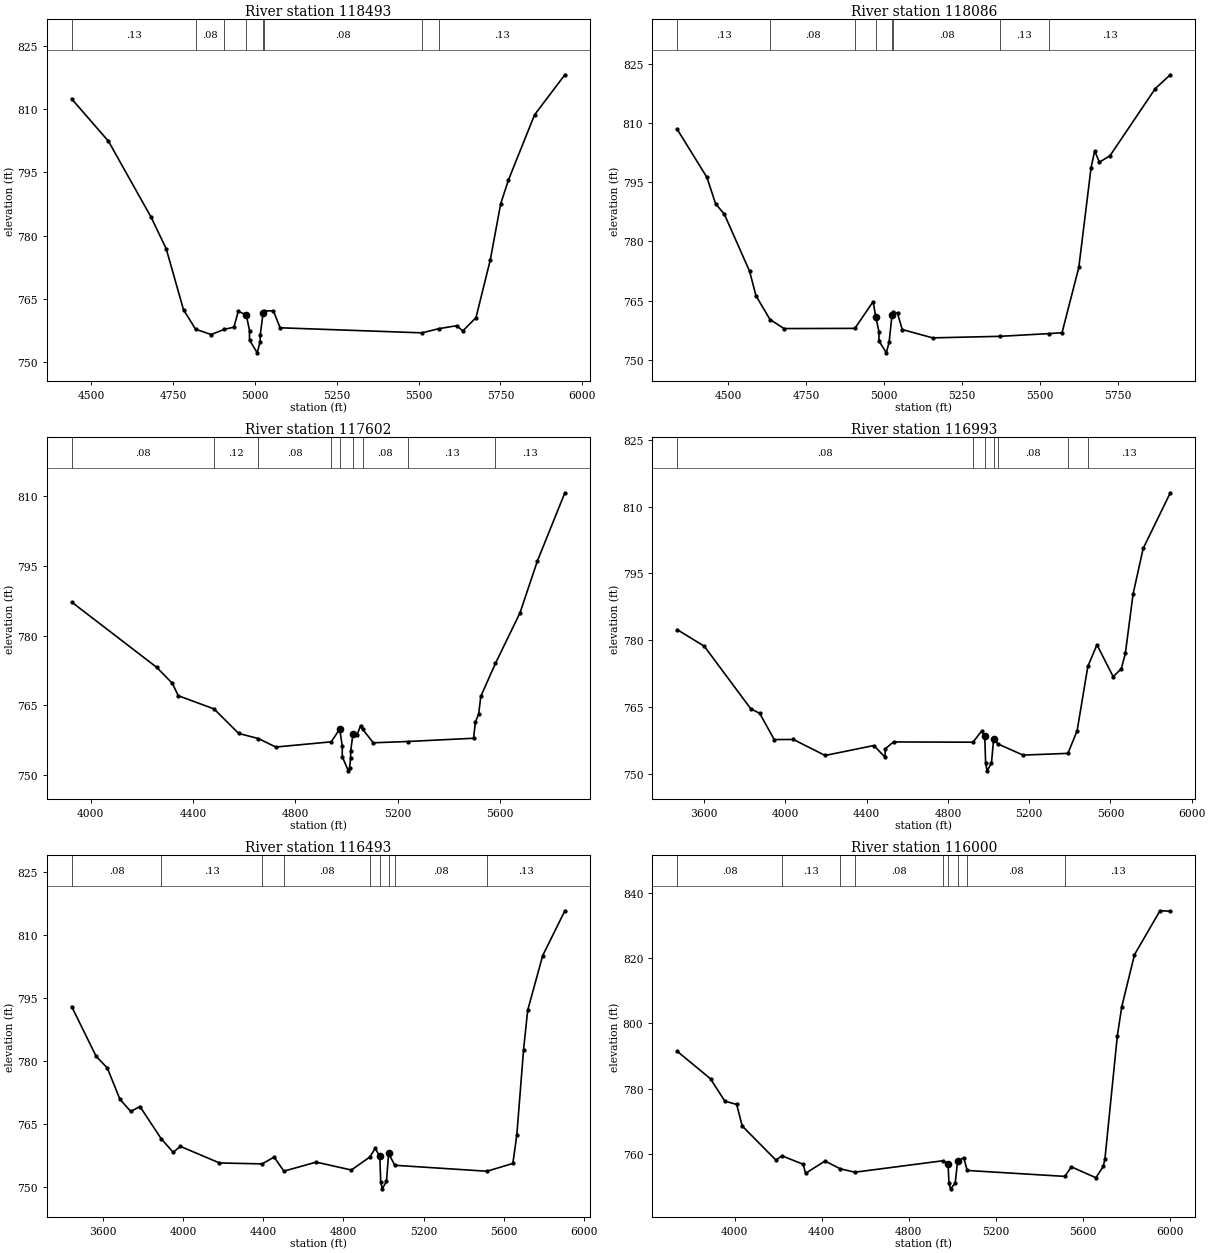
Type RM Length L Ch R = 1,118493,413,407,399
BEGIN DESCRIPTION:
Fourth Creek 180.0
END DESCRIPTION:
XS GIS Cut Line= 4
      1457466.36       747637.83      1457227.17       747130.93
      1457102.15       746885.76      1456567.64       746478.97
#Sta/Elev= 30
  4439.5  812.40  4552.0  802.36  4682.9  784.27  4728.7  776.82  4781.4  762.39
  4818.3  757.79  4865.7  756.52  4905.9  757.74  4935.4  758.27  4948.7  762.01
  4973.1  761.20  4983.1  757.47  4983.1  755.22  5006.7  752.18  5015.6  754.86
  5015.8  756.39  5024.8  761.68  5028.2  762.11  5055.9  762.15  5076.7  758.12
  5510.6  756.92  5561.6  757.91  5616.5  758.62  5634.9  757.36  5675.3  760.53
  5719.1  774.25  5750.6  787.47  5774.4  793.15  5854.4  808.63  5946.9  818.11
#Mann=8,-1,0
  4439.5    0.13       0  4818.3    0.08       0  4905.9    0.13       0
  4973.1   0.042       0  5024.8    0.13       0  5028.2    0.08       0
  5510.6    0.12       0  5561.6    0.13       0
Bank Sta=4973.1,5024.8
XS Rating Curve= 0
Exp/Cntr=0.3,0.1

Type RM Length L Ch R = 1,118086,521,484,437
BEGIN DESCRIPTION:
Fourth Creek 179.0
END DESCRIPTION:
XS GIS Cut Line= 5
      1457669.80       747563.32      1457693.11       747134.29
      1457571.86       746915.11      1457366.67       746542.02
      1457274.99       746074.97
#Sta/Elev= 30
  4335.6  808.52  4431.3  796.27  4459.0  789.59  4487.2  786.92  4568.1  772.45
  4588.6  766.22  4633.6  760.20  4678.6  757.90  4905.8  757.95  4964.3  764.73
  4973.1  760.76  4983.1  757.03  4983.1  754.78  5006.7  751.74  5015.6  754.42
  5024.8  761.24  5029.3  762.23  5042.6  761.73  5057.8  757.65  5155.1  755.54
  5371.0  755.93  5528.2  756.62  5570.2  756.84  5624.0  773.42  5663.4  798.76
  5674.9  803.00  5690.0  800.13  5724.0  801.76  5869.4  818.82  5917.5  822.31
#Mann=8,-1,0
  4335.6    0.13       0  4633.6    0.08       0  4905.8    0.13       0
  4973.1   0.042       0  5024.8    0.13       0  5029.3    0.08       0
  5371.0    0.13       0  5528.2    0.13       0
Bank Sta=4973.1,5024.8
XS Rating Curve= 0
Exp/Cntr=0.3,0.1

Type RM Length L Ch R = 1,117602,592,609,568
BEGIN DESCRIPTION:
Fourth Creek 178.0
END DESCRIPTION:
XS GIS Cut Line= 5
      1458632.30       747541.65      1458225.53       746929.00
      1457984.50       746672.90      1457658.10       746321.39
      1457351.74       746130.54
#Sta/Elev= 30
  3925.3  787.26  4257.9  773.19  4318.7  769.76  4342.1  767.08  4481.8  764.24
  4578.0  758.96  4655.5  757.85  4723.2  756.03  4940.0  757.15  4973.1  759.92
  4983.1  756.19  4983.1  753.94  5006.7  750.90  5011.3  751.43  5015.6  753.58
  5015.8  755.11  5024.8  758.81  5040.6  758.57  5054.7  760.65  5062.1  759.91
  5104.2  756.94  5238.2  757.22  5496.1  757.92  5503.5  761.46  5516.0  763.09
  5524.5  766.96  5581.9  774.07  5677.7  784.94  5745.7  796.11  5853.0  810.80
#Mann=9,-1,0
  3925.3    0.08       0  4481.8    0.12       0  4655.5    0.08       0
  4940.0    0.13       0  4973.1   0.042       0  5024.8    0.13       0
  5062.1    0.08       0  5238.2    0.13       0  5581.9    0.13       0
Bank Sta=4973.1,5024.8
XS Rating Curve= 0
Exp/Cntr=0.3,0.1

Type RM Length L Ch R = 1,116993,483,500,504
BEGIN DESCRIPTION:
Fourth Creek 177.0
END DESCRIPTION:
XS GIS Cut Line= 4
      1459089.25       747325.73      1458993.83       746813.50
      1458246.07       746130.91      1457562.71       745553.11
#Sta/Elev= 30
  3466.5  782.37  3600.1  778.64  3829.1  764.57  3873.1  763.53  3944.7  757.64
  4039.0  757.65  4195.2  754.06  4435.2  756.29  4490.5  753.67  4491.5  755.56
  4532.1  757.10  4923.5  757.04  4966.9  759.62  4981.3  758.33  4985.6  752.29
  4993.0  750.60  5014.4  752.35  5025.0  757.74  5046.6  756.64  5169.8  754.14
  5390.8  754.53  5436.1  759.61  5488.7  774.07  5533.7  778.95  5613.6  771.78
  5653.6  773.57  5673.6  777.02  5711.5  790.35  5761.3  800.62  5894.9  813.14
#Mann=7,-1,0
  3466.5    0.08       0  4923.5    0.13       0  4981.3   0.042       0
  5025.0    0.13       0  5046.6    0.08       0  5390.8    0.13       0
  5488.7    0.13       0
Bank Sta=4981.3,5025
XS Rating Curve= 0
Exp/Cntr=0.3,0.1

Type RM Length L Ch R = 1,116493,504,493,478
BEGIN DESCRIPTION:
Fourth Creek 176.0
END DESCRIPTION:
XS GIS Cut Line= 4
      1459987.09       746450.44      1459123.39       746289.75
      1458633.17       745823.29      1457988.49       745190.00
#Sta/Elev= 30
  3444.8  793.02  3566.7  781.19  3622.7  778.38  3685.4  770.96  3739.2  768.05
  3785.6  769.20  3890.9  761.57  3950.7  758.33  3987.3  759.72  4181.9  755.78
  4394.6  755.56  4454.2  757.18  4502.9  753.83  4663.9  755.98  4839.2  754.10
  4931.2  757.19  4958.1  759.24  4981.3  757.35  4985.6  751.31  4993.0  749.62
  5014.4  751.37  5025.0  758.04  5055.9  755.23  5515.2  753.81  5644.5  755.66
  5664.1  762.42  5697.9  782.76  5718.2  792.09  5793.2  805.14  5903.7  815.81
#Mann=9,-1,0
  3444.8    0.08       0  3890.9    0.13       0  4394.6    0.09       0
  4502.9    0.08       0  4931.2    0.13       0  4981.3   0.042       0
  5025.0    0.13       0  5055.9    0.08       0  5515.2    0.13       0
Bank Sta=4981.3,5025
XS Rating Curve= 0
Exp/Cntr=0.3,0.1

Type RM Length L Ch R = 1,116000,396,489,555
BEGIN DESCRIPTION:
Fourth Creek 175.0
END DESCRIPTION:
XS GIS Cut Line= 3
      1459977.06       746334.95      1459007.89       745511.41
      1458264.67       744848.53
#Sta/Elev= 30
  3735.6  791.48  3889.2  783.03  3955.1  776.19  4009.6  775.17  4034.8  768.59
  4190.2  758.12  4217.2  759.46  4315.3  756.86  4326.2  754.08  4415.7  757.85
  4485.4  755.49  4552.8  754.43  4957.0  757.93  4981.3  757.07  4985.6  751.03
  4993.0  749.34  5014.4  751.09  5025.0  757.76  5053.4  758.88  5069.5  754.97
  5518.5  753.15  5548.1  756.08  5661.0  752.74  5695.0  756.20  5702.7  758.49
  5759.8  796.24  5780.1  805.10  5838.5  821.02  5955.7  834.47  6003.3  834.34
#Mann=9,-1,0
  3735.6    0.08       0  4217.2    0.13       0  4485.4    0.09       0
  4552.8    0.08       0  4957.0    0.13       0  4981.3   0.042       0
  5025.0    0.13       0  5069.5    0.08       0  5518.5    0.13       0
Bank Sta=4981.3,5025
XS Rating Curve= 0
Exp/Cntr=0.3,0.1

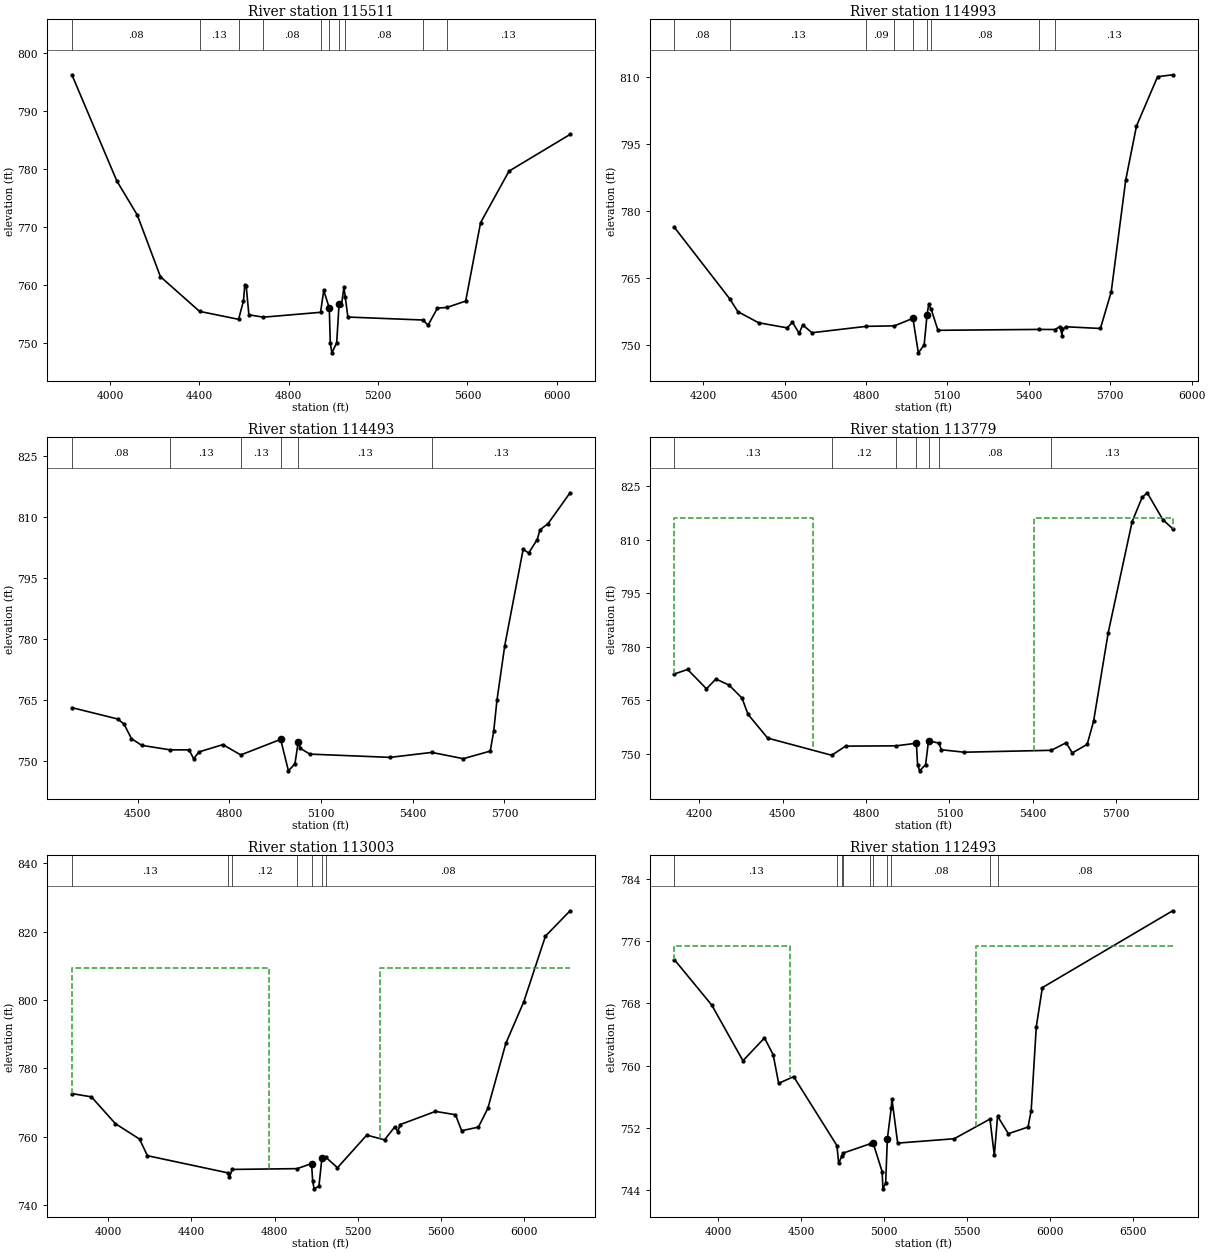
Type RM Length L Ch R = 1,115511,474,518,486
BEGIN DESCRIPTION:
Fourth Creek 174.0 (Survey)
END DESCRIPTION:
XS GIS Cut Line= 4
      1460097.57       746167.72      1459585.37       745524.97
      1459374.47       745213.63      1458857.26       744319.81
#Sta/Elev= 30
  3828.8  796.26  4029.8  777.94  4121.7  772.03  4225.2  761.39  4400.4  755.40
  4575.1  754.03  4597.0  757.21  4602.8  759.88  4609.1  759.83  4621.2  754.81
  4685.9  754.40  4942.2  755.24  4956.3  759.02  4981.3  755.97  4985.6  749.93
  4993.0  748.24  5014.4  749.99  5025.0  756.66  5035.7  756.52  5046.9  759.57
  5052.4  757.96  5064.5  754.42  5400.5  753.91  5423.4  753.01  5465.6  755.97
  5507.1  756.07  5591.9  757.18  5658.5  770.71  5785.9  779.62  6059.4  785.96
#Mann=10,-1,0
  3828.8    0.08       0  4400.4    0.13       0  4575.1    0.09       0
  4685.9    0.08       0  4942.2    0.13       0  4981.3   0.042       0
  5025.0    0.13       0  5052.4    0.08       0  5400.5     0.1       0
  5507.1    0.13       0
Bank Sta=4981.3,5025
XS Rating Curve= 0
Exp/Cntr=0.3,0.1

Type RM Length L Ch R = 1,114993,623,500,570
BEGIN DESCRIPTION:
Fourth Creek 173.0
END DESCRIPTION:
XS GIS Cut Line= 3
      1460175.01       745775.02      1459814.25       744944.38
      1459225.00       744225.01
#Sta/Elev= 30
  4094.4  776.30  4298.4  760.27  4328.2  757.41  4404.3  754.93  4509.8  753.78
  4529.2  755.03  4554.1  752.56  4566.9  754.44  4601.1  752.69  4801.6  754.12
  4905.0  754.23  4973.1  755.91  4993.0  748.18  5014.4  749.93  5025.0  756.60
  5031.0  759.02  5040.7  757.90  5065.3  753.23  5437.0  753.43  5496.0  753.41
  5515.1  754.08  5522.5  752.03  5524.1  753.57  5538.7  754.02  5663.8  753.64
  5703.6  761.82  5757.1  786.93  5796.7  799.02  5874.4  810.07  5929.9  810.51
#Mann=9,-1,0
  4094.4    0.08       0  4298.4    0.13       0  4801.6    0.09       0
  4905.0    0.13       0  4973.1   0.042       0  5025.0    0.13       0
  5040.7    0.08       0  5437.0     0.1       0  5496.0    0.13       0
Bank Sta=4973.1,5025
XS Rating Curve= 0
Exp/Cntr=0.3,0.1

Type RM Length L Ch R = 1,114493,657,714,622
BEGIN DESCRIPTION:
Fourth Creek 172.0
END DESCRIPTION:
XS GIS Cut Line= 3
      1460774.99       745024.99      1460188.71       744614.50
      1459825.00       743775.00
#Sta/Elev= 30
  4284.3  763.23  4434.8  760.43  4455.3  759.14  4479.2  755.61  4513.0  753.96
  4606.2  752.85  4667.7  752.85  4682.9  750.68  4700.7  752.36  4778.4  754.14
  4837.0  751.61  4967.6  755.43  4993.0  747.70  5014.4  749.45  5025.0  754.78
  5031.9  753.23  5063.1  751.81  5325.8  751.01  5462.0  752.23  5565.1  750.69
  5653.5  752.55  5664.8  757.40  5675.6  765.10  5701.1  778.49  5761.2  802.11
  5779.6  801.23  5807.2  804.53  5816.3  806.90  5843.0  808.47  5914.9  816.02
#Mann=6,-1,0
  4284.3    0.08       0  4606.2    0.13       0  4837.0    0.13       0
  4967.6   0.042       0  5025.0    0.13       0  5462.0    0.13       0
Bank Sta=4967.6,5025
XS Rating Curve= 0
Exp/Cntr=0.3,0.1

Type RM Length L Ch R = 1,113779,659,776,873
BEGIN DESCRIPTION:
Fourth Creek 170.0
END DESCRIPTION:
XS GIS Cut Line= 4
      1461324.18       744838.33      1460741.10       744170.85
      1460311.45       743779.56      1460025.00       743625.00
#Sta/Elev= 30
  4110.5  772.36  4158.0  773.61  4225.9  768.20  4259.6  770.94  4306.6  769.26
  4353.7  765.61  4375.3  761.05  4446.1  754.39  4676.7  749.58  4726.3  752.14
  4907.8  752.22  4981.3  752.95  4985.6  746.91  4993.0  745.22  5014.4  746.97
  5025.0  753.64  5062.8  752.97  5070.7  751.13  5153.1  750.44  5466.8  750.97
  5520.1  753.08  5542.4  750.24  5595.9  752.63  5618.8  759.08  5671.7  783.96
  5757.8  815.05  5793.7  821.80  5811.9  823.10  5868.5  815.54  5903.4  813.04
#Mann=7,-1,0
  4110.5    0.13       0  4676.7    0.12       0  4907.8    0.13       0
  4981.3   0.042       0  5025.0    0.13       0  5062.8    0.08       0
  5466.8    0.13       0
#XS Ineff=2,0
    0.00 4607.70  816.12 5403.20    0.00  816.12
Permanent Ineff=
       F       F
Bank Sta=4981.3,5025
XS Rating Curve= 0
Exp/Cntr=0.3,0.1

Type RM Length L Ch R = 1,113003,479,510,555
BEGIN DESCRIPTION:
Fourth Creek 169.0
END DESCRIPTION:
XS GIS Cut Line= 4
      1461554.35       744892.03      1461342.14       743732.98
      1461208.56       743076.72      1460794.77       742713.09
#Sta/Elev= 30
  3824.4  772.66  3918.5  771.69  4033.7  763.86  4150.1  759.34  4188.0  754.48
  4576.0  749.45  4582.7  748.15  4596.4  750.46  4909.4  750.69  4978.3  752.18
  4983.9  747.00  4990.8  744.78  5013.9  745.54  5028.1  753.66  5045.9  754.08
  5103.2  750.96  5244.1  760.50  5329.8  759.12  5379.9  762.97  5393.7  761.45
  5404.8  763.57  5574.8  767.44  5671.2  766.47  5701.1  761.79  5781.7  762.84
  5827.1  768.32  5913.9  787.36  6000.4  799.54  6104.6  818.74  6223.3  826.15
#Mann=7,-1,0
  3824.4    0.13       0  4576.0    0.05       0  4596.4    0.12       0
  4909.4    0.13       0  4978.3   0.042       0  5028.1    0.13       0
  5045.9    0.08       0
#XS Ineff=2,0
    0.00 4773.80  809.47 5307.40    0.00  809.47
Permanent Ineff=
       F       F
Bank Sta=4978.3,5028.1
XS Rating Curve= 0
Exp/Cntr=0.3,0.1

Type RM Length L Ch R = 1,112493,588,593,642
BEGIN DESCRIPTION:
Fourth Creek 168.0
END DESCRIPTION:
XS GIS Cut Line= 4
      1461870.45       744953.41      1461846.60       743689.24
      1461755.37       742690.10      1462085.28       742030.28
#Sta/Elev= 30
  3735.6  773.63  3961.3  767.78  4149.0  760.64  4278.8  763.57  4331.3  761.42
  4364.4  757.73  4454.8  758.60  4716.0  749.73  4726.4  747.45  4746.0  748.41
  4754.2  748.77  4913.1  749.94  4934.1  750.07  4988.5  746.39  4993.4  744.17
  5009.9  744.93  5020.1  750.59  5043.5  754.58  5047.7  755.73  5082.4  750.05
  5423.2  750.61  5639.0  753.14  5665.4  748.47  5685.0  753.51  5750.2  751.26
  5868.4  752.11  5887.6  754.20  5918.6  765.02  5955.1  770.04  6741.0  779.92
#Mann=10,-1,0
  3735.6    0.13       0  4716.0    0.05       0  4746.0    0.13       0
  4754.2    0.12       0  4913.1    0.13       0  4934.1   0.042       0
  5020.1    0.13       0  5043.5    0.08       0  5639.0    0.05       0
  5685.0    0.08       0
#XS Ineff=2,0
    0.00 4432.10  775.33 5552.70    0.00  775.33
Permanent Ineff=
       F       F
Bank Sta=4934.1,5020.1
XS Rating Curve= 0
Exp/Cntr=0.3,0.1

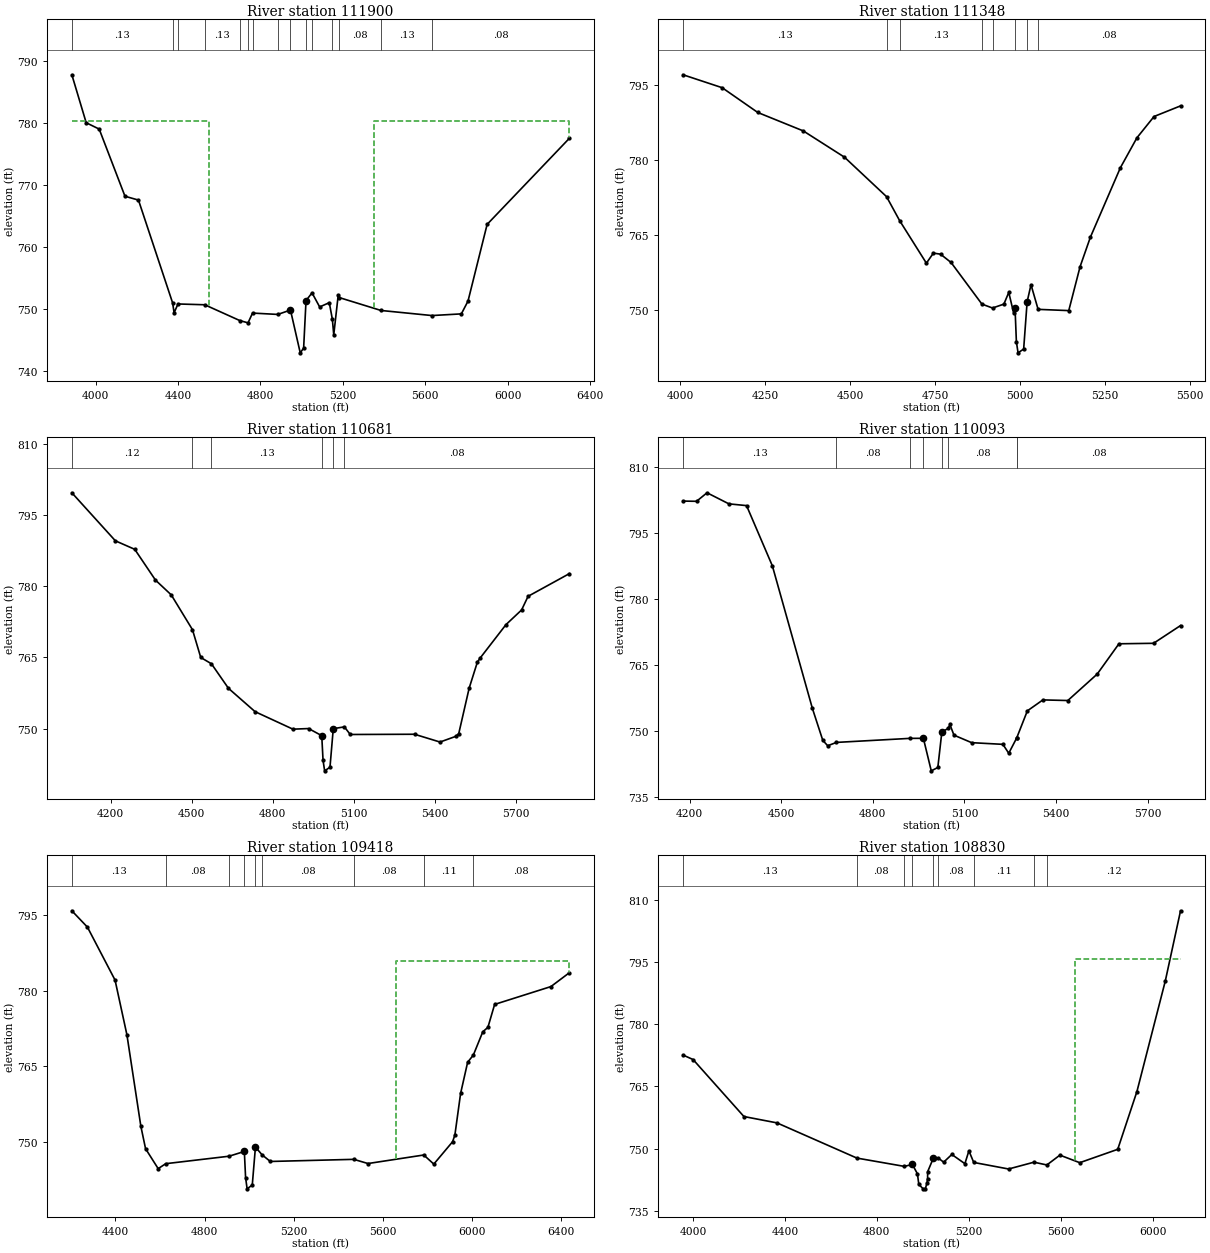
Type RM Length L Ch R = 1,111900,508,552,678
BEGIN DESCRIPTION:
Fourth Creek 167.0
END DESCRIPTION:
XS GIS Cut Line= 5
      1462723.62       744701.03      1462435.13       744031.98
      1462435.13       743675.99      1462453.54       743332.27
      1462722.07       742383.23
#Sta/Elev= 30
  3884.7  787.85  3954.3  780.11  4017.5  779.08  4142.6  768.24  4208.1  767.62
  4374.0  751.01  4381.0  749.43  4400.0  750.85  4529.9  750.72  4700.0  748.17
  4740.0  747.80  4761.9  749.38  4884.5  749.16  4946.0  749.87  4993.4  742.96
  5009.9  743.72  5021.5  751.40  5050.7  752.64  5087.7  750.37  5134.4  751.06
  5149.3  748.40  5156.1  745.87  5177.6  752.22  5184.0  751.87  5385.6  749.80
  5632.8  748.98  5775.6  749.25  5807.9  751.32  5900.7  763.70  6299.8  777.59
#Mann=15,-1,0
  3884.7    0.13       0  4374.0    0.05       0  4400.0    0.08       0
  4529.9    0.13       0  4700.0    0.05       0  4740.0    0.13       0
  4761.9    0.12       0  4884.5    0.13       0  4946.0   0.042       0
  5021.5    0.13       0  5050.7    0.08       0  5149.3    0.05       0
  5184.0    0.08       0  5385.6    0.13       0  5632.8    0.08       0
#XS Ineff=2,0
    0.00 4550.60  780.45 5349.70    0.00  780.45
Permanent Ineff=
       F       F
Bank Sta=4946,5021.5
XS Rating Curve= 0
Exp/Cntr=0.3,0.1

Type RM Length L Ch R = 1,111348,695,667,609
BEGIN DESCRIPTION:
Fourth Creek 165.0 (Survey)
END DESCRIPTION:
XS GIS Cut Line= 4
      1462981.39       744817.59      1462932.29       743946.05
      1462944.57       743823.29      1462975.26       743356.79
#Sta/Elev= 30
  4007.7  797.10  4122.8  794.51  4227.5  789.55  4361.6  785.85  4482.7  780.59
  4606.4  772.69  4644.9  767.89  4723.7  759.36  4744.3  761.38  4765.4  761.16
  4796.3  759.50  4887.1  751.16  4918.3  750.38  4951.7  751.16  4966.1  753.51
  4980.5  749.35  4984.5  750.40  4988.5  743.62  4993.4  741.40  5009.9  742.16
  5020.1  751.62  5031.5  755.05  5052.4  750.11  5142.6  749.86  5175.9  758.66
  5206.3  764.58  5294.5  778.48  5343.2  784.48  5393.5  788.74  5471.5  790.87
#Mann=8,-1,0
  4007.7    0.13       0  4606.4    0.12       0  4644.9    0.13       0
  4887.1    0.08       0  4918.3    0.13       0  4984.5   0.042       0
  5020.1    0.13       0  5052.4    0.08       0
Bank Sta=4984.5,5020.1
XS Rating Curve= 0
Exp/Cntr=0.3,0.1

Type RM Length L Ch R = 1,110681,614,588,550
BEGIN DESCRIPTION:
Fourth Creek 164.0
END DESCRIPTION:
XS GIS Cut Line= 5
      1463746.16       744743.92      1463715.47       744154.74
      1463592.72       743817.16      1463476.10       743516.40
      1463107.84       743080.63
#Sta/Elev= 30
  4056.0  799.64  4217.2  789.53  4288.9  787.74  4365.7  781.26  4424.1  778.15
  4502.7  770.82  4533.3  764.98  4572.9  763.65  4635.9  758.49  4734.6  753.57
  4874.7  749.89  4932.8  750.02  4981.4  748.52  4986.2  743.34  4992.1  741.12
  5011.9  741.88  5024.1  750.00  5065.2  750.37  5087.0  748.77  5325.0  748.82
  5419.4  747.18  5477.4  748.37  5488.7  748.95  5527.2  758.50  5557.6  763.98
  5568.0  764.86  5663.6  771.89  5721.5  774.98  5745.5  777.85  5898.3  782.62
#Mann=6,-1,0
  4056.0    0.12       0  4502.7    0.08       0  4572.9    0.13       0
  4981.4   0.042       0  5024.1    0.13       0  5065.2    0.08       0
Bank Sta=4981.4,5024.1
XS Rating Curve= 0
Exp/Cntr=0.3,0.1

Type RM Length L Ch R = 1,110093,669,675,692
BEGIN DESCRIPTION:
Fourth Creek 163.0
END DESCRIPTION:
XS GIS Cut Line= 4
      1464666.86       744173.17      1464335.39       743890.81
      1464126.71       743571.64      1463617.25       742939.43
#Sta/Elev= 30
  4178.8  802.23  4223.0  802.18  4257.3  804.12  4328.9  801.60  4386.7  801.20
  4471.2  787.49  4602.2  755.06  4636.3  747.79  4652.4  746.56  4681.0  747.32
  4921.8  748.24  4965.6  748.25  4991.4  740.85  5012.9  741.61  5026.1  749.73
  5047.0  750.49  5052.4  751.40  5065.7  748.97  5123.6  747.26  5225.9  746.88
  5245.1  744.85  5271.1  748.33  5271.6  748.42  5306.0  754.50  5356.9  756.99
  5438.5  756.85  5534.7  762.87  5605.8  769.76  5719.1  769.87  5807.5  773.91
#Mann=8,-1,0
  4178.8    0.13       0  4681.0    0.08       0  4921.8    0.13       0
  4965.6   0.042       0  5026.1    0.13       0  5047.0    0.08       0
  5271.1    0.11       0  5271.6    0.08       0
Bank Sta=4965.6,5026.1
XS Rating Curve= 0
Exp/Cntr=0.3,0.1

Type RM Length L Ch R = 1,109418,565,588,622
BEGIN DESCRIPTION:
Fourth Creek 162.0
END DESCRIPTION:
XS GIS Cut Line= 5
      1464912.34       743999.49      1464936.90       743637.32
      1464715.94       743244.50      1464458.15       742839.40
      1463752.29       742221.32
#Sta/Elev= 30
  4204.4  795.80  4274.3  792.56  4398.2  782.08  4451.5  771.23  4514.0  753.13
  4535.1  748.69  4591.7  744.74  4625.6  745.72  4909.7  747.20  4978.3  748.14
  4983.9  742.96  4990.8  740.74  5013.9  741.50  5028.1  749.02  5057.8  747.48
  5094.8  746.16  5469.4  746.58  5533.1  745.75  5783.3  747.44  5828.4  745.64
  5912.5  750.06  5922.9  751.38  5948.6  759.63  5980.2  765.81  6005.7  767.22
  6048.1  771.83  6071.1  772.72  6101.3  777.26  6353.8  780.79  6436.5  783.53
#Mann=9,-1,0
  4204.4    0.13       0  4625.6    0.08       0  4909.7    0.13       0
  4978.3   0.042       0  5028.1    0.13       0  5057.8    0.08       0
  5469.4    0.08       0  5783.3    0.11       0  6005.7    0.08       0
#XS Ineff=2,0
       0                 5659.40    0.00  785.92
Permanent Ineff=
       F       F
Bank Sta=4978.3,5028.1
XS Rating Curve= 0
Exp/Cntr=0.3,0.1

Type RM Length L Ch R = 1,108830,737,739,727
BEGIN DESCRIPTION:
Fourth Creek 160.0
END DESCRIPTION:
XS GIS Cut Line= 4
      1465636.59       743901.21      1465219.24       742943.75
      1465084.20       742636.86      1465274.48       741875.74
#Sta/Elev= 30
  3957.1  772.57  4000.8  771.49  4221.9  757.76  4365.7  756.23  4713.4  747.75
  4919.8  745.75  4954.8  746.22  4976.8  743.95  4982.7  741.41  5001.7  740.34
  5011.0  740.34  5018.6  741.81  5021.0  742.83  5021.2  744.47  5045.5  747.67
  5066.4  747.81  5090.8  746.76  5126.4  748.62  5183.2  746.40  5200.7  749.49
  5221.7  746.70  5373.3  745.12  5483.7  746.76  5539.9  746.09  5596.5  748.46
  5682.9  746.64  5848.1  749.86  5931.7  763.79  6054.9  790.37  6121.4  807.33
#Mann=9,-1,0
  3957.1    0.13       0  4713.4    0.08       0  4919.8    0.13       0
  4954.8   0.042       0  5045.5    0.13       0  5066.4    0.08       0
  5221.7    0.11       0  5483.7    0.08       0  5539.9    0.12       0
#XS Ineff=2,0
       0                 5663.80    0.00  795.64
Permanent Ineff=
       F       F
Bank Sta=4954.8,5045.5
XS Rating Curve= 0
Exp/Cntr=0.3,0.1

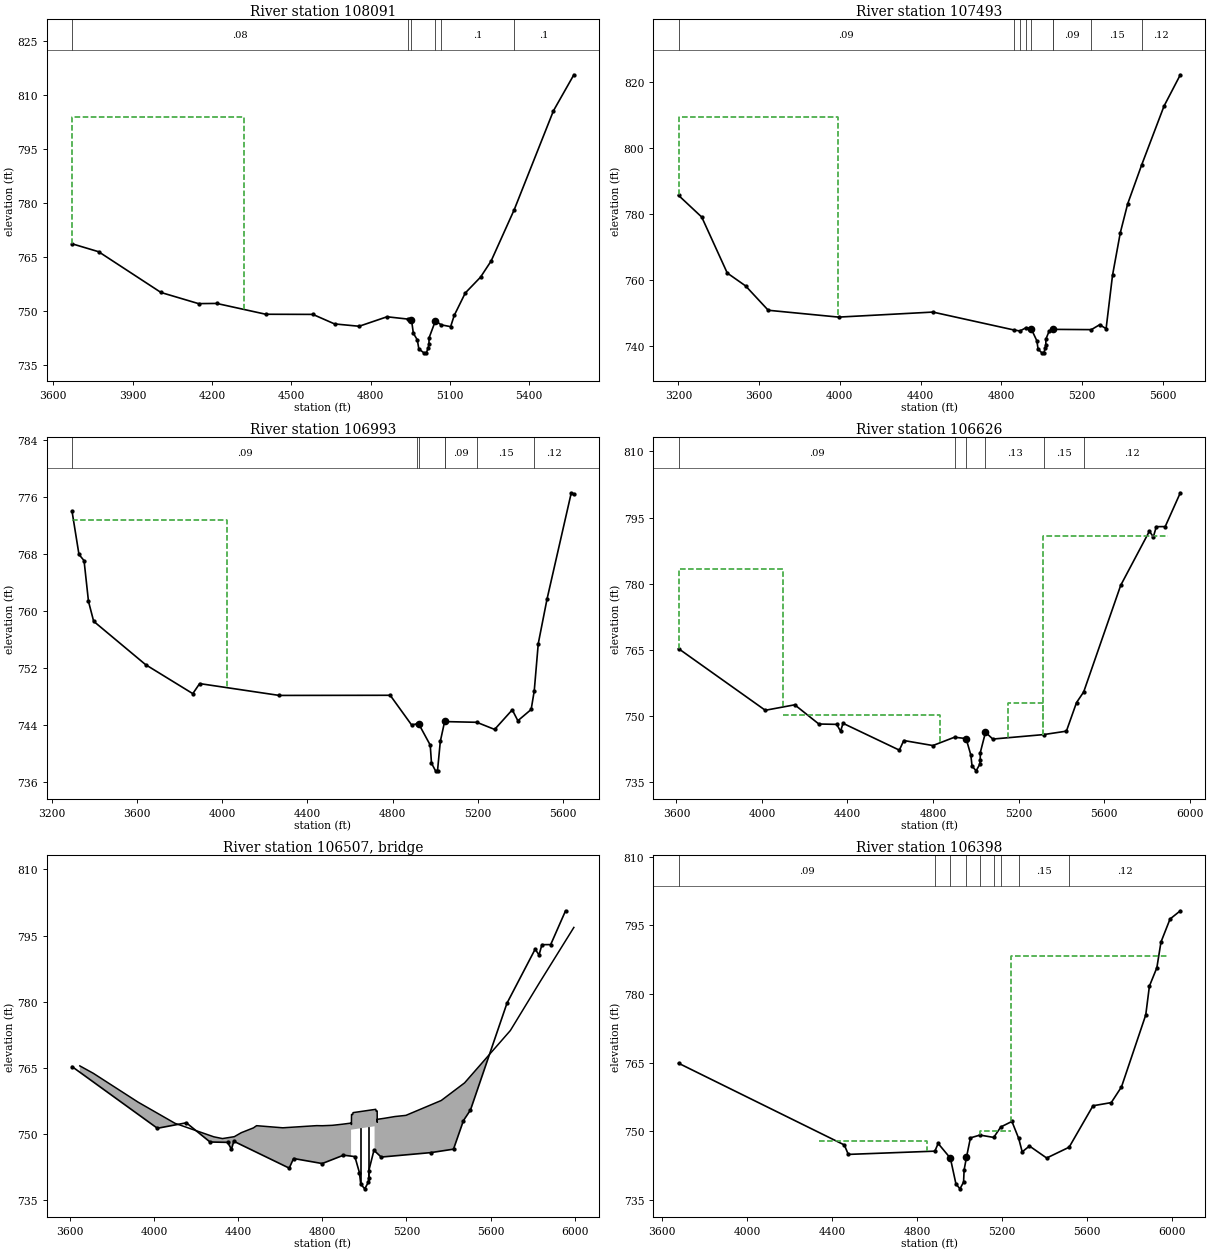
Type RM Length L Ch R = 1,108091,580,598,611
BEGIN DESCRIPTION:
Fourth Creek 159.0
END DESCRIPTION:
XS GIS Cut Line= 4
      1466004.87       743778.48      1466078.53       743078.78
      1465820.74       742520.24      1465625.01       741975.04
#Sta/Elev= 30
  3671.0  768.70  3771.4  766.50  4007.3  755.20  4149.3  752.11  4217.9  752.16
  4403.7  749.16  4581.8  749.12  4663.8  746.48  4756.8  745.83  4862.3  748.46
  4942.5  747.81  4954.8  747.64  4961.9  743.88  4976.8  742.07  4982.7  739.53
  5001.7  738.46  5011.0  738.46  5018.6  739.93  5021.0  740.95  5021.2  742.59
  5045.5  747.36  5066.9  746.23  5102.9  745.72  5116.4  748.82  5158.3  755.06
  5215.9  759.44  5256.0  763.92  5343.4  778.15  5491.9  805.60  5569.0  815.57
#Mann=6,-1,0
  3671.0    0.08       0  4942.5    0.13       0  4954.8   0.042       0
  5045.5    0.13       0  5066.9     0.1       0  5343.4     0.1       0
#XS Ineff=2,0
    0.00 4322.20  803.83               0
Permanent Ineff=
       F       F
Bank Sta=4954.8,5045.5
XS Rating Curve= 0
Exp/Cntr=0.3,0.1

Type RM Length L Ch R = 1,107493,440,500,514
BEGIN DESCRIPTION:
Fourth Creek 158.0
END DESCRIPTION:
XS GIS Cut Line= 4
      1466661.62       744030.16      1466710.72       743361.12
      1466369.21       742285.89      1466182.87       741624.12
#Sta/Elev= 30
  3201.0  785.58  3316.0  779.01  3442.5  762.08  3533.3  758.19  3645.5  750.82
  3994.1  748.75  4461.4  750.27  4861.1  744.88  4892.8  744.55  4923.2  745.56
  4948.3  745.25  4976.8  741.55  4982.7  739.01  5001.7  737.94  5011.0  737.94
  5018.6  739.41  5021.0  740.43  5021.2  742.07  5037.6  744.54  5054.7  745.18
  5057.1  745.04  5246.7  744.96  5287.8  746.45  5319.7  745.24  5351.5  761.40
  5390.0  774.25  5426.4  782.98  5495.9  794.78  5606.8  812.60  5687.5  822.06
#Mann=9,-1,0
  3201.0    0.09       0  4861.1    0.13       0  4892.8    0.09       0
  4923.2    0.13       0  4948.3   0.045       0  5054.7    0.13       0
  5057.1    0.09       0  5246.7    0.15       0  5495.9    0.12       0
#XS Ineff=2,0
    0.00 3991.20  809.26               0
Permanent Ineff=
       F       F
Bank Sta=4948.3,5054.7
XS Rating Curve= 0
Exp/Cntr=0.3,0.1

Type RM Length L Ch R = 1,106993,480,367,331
BEGIN DESCRIPTION:
Fourth Creek 157.0
END DESCRIPTION:
XS GIS Cut Line= 3
      1467147.06       743840.83      1466851.43       742161.66
      1466741.42       741519.82
#Sta/Elev= 30
  3295.0  774.02  3327.4  767.99  3351.3  767.12  3372.1  761.40  3396.4  758.61
  3640.6  752.52  3861.9  748.46  3894.0  749.87  4268.0  748.21  4788.8  748.23
  4889.0  744.08  4916.4  744.23  4921.8  744.27  4976.8  741.24  4982.7  738.70
  5001.7  737.63  5011.0  737.63  5024.1  741.76  5044.5  744.56  5045.7  744.54
  5195.4  744.44  5279.2  743.44  5362.0  746.19  5388.2  744.66  5450.7  746.24
  5465.2  748.85  5484.1  755.49  5525.3  761.74  5639.1  776.64  5651.2  776.49
#Mann=7,-1,0
  3295.0    0.09       0  4916.4    0.13       0  4921.8   0.045       0
  5044.5    0.13       0  5045.7    0.09       0  5195.4    0.15       0
  5465.2    0.12       0
#XS Ineff=2,0
    0.00 4022.20  772.79               0
Permanent Ineff=
       F       F
Bank Sta=4921.8,5044.5
XS Rating Curve= 0
Exp/Cntr=0.5,0.3

Type RM Length L Ch R = 1,106626,215,228,291
BEGIN DESCRIPTION:
Bell Farm Rd (FC) us
END DESCRIPTION:
XS GIS Cut Line= 4
      1467729.88       743459.64      1467339.82       742423.49
      1467031.07       741786.20      1466916.23       741267.03
#Sta/Elev= 30
  3609.8  765.30  4015.6  751.33  4153.3  752.57  4266.1  748.22  4349.5  748.14
  4367.7  746.58  4379.1  748.38  4642.6  742.30  4663.3  744.48  4799.5  743.34
  4900.7  745.23  4954.8  744.92  4976.8  741.22  4982.7  738.68  5001.7  737.61
  5018.6  739.08  5021.0  740.10  5021.2  741.74  5045.5  746.34  5079.8  744.81
  5316.9  745.82  5423.9  746.60  5471.3  753.08  5504.7  755.48  5678.1  779.66
  5812.1  791.90  5830.7  790.61  5844.5  792.93  5886.1  792.95  5956.8  800.61
#Mann=6,-1,0
  3609.8    0.09       0  4900.7    0.13       0  4954.8   0.045       0
  5045.5    0.13       0  5316.9    0.15       0  5504.7    0.12       0
#XS Ineff=4,-1
 4097.30 4832.20  750.30 5152.00 5315.30  753.00 3510.90 4097.20  783.45
 5315.40 5897.50  790.71
Permanent Ineff=
       F       F       F       F
Bank Sta=4954.8,5045.5
XS Rating Curve= 0
Exp/Cntr=0.5,0.3

Type RM Length L Ch R =3,106507,,,
BEGIN DESCRIPTION:
Bell Farm Rd (FC) TOR
Structure ID: I_FC_02
Detailed Survey Structure
END DESCRIPTION:
Bridge Culvert--1,0,-1,-1,0
Deck Dist Width WeirC Skew NumUp NumDn MinLoCord MaxHiCord MaxSubmerge Is_Ogee
103.5,33,3,,38,38,,,,0,1,1,,,
  3646.6  3710.7  3923.9  4099.7  4283.9  4325.0  4381.5  4414.4  4472.2  4487.3
  4611.8  4773.2  4800.8  4847.0  4895.1  4936.7  4936.7  4938.3  4938.3  4938.9
  4944.2  4946.4  5048.5  5048.5  5054.1  5056.1  5059.4  5060.9  5061.1  5061.1
  5094.6  5144.7  5197.7  5365.6  5476.6  5694.3  5835.2  5996.3
  765.47  763.79  757.25  752.45  749.40  749.00  749.43  750.33  751.42  751.92
  751.44  751.93  751.91  752.00  752.25  752.51  752.51  752.52  752.18  754.47
  754.45  754.88  755.59  755.59  755.63  755.20  755.27  755.24  752.69  753.36
  753.59  753.99  754.26  757.63  761.62  773.48  784.50  796.84
  717.61  717.61  717.61  717.61  717.61  717.61  717.61  717.61  717.61  717.61
  717.61  717.61  717.61  717.61  717.61  717.61  751.01  751.02  751.02  751.03
  751.06  751.08  751.78  717.61  717.61  717.61  717.61  717.61  717.61  717.61
  717.61  717.61  717.61  717.61  717.61  717.61  717.61  717.61
  3646.6  3710.7  3923.9  4099.7  4283.9  4325.0  4381.5  4414.4  4472.2  4487.3
  4611.8  4773.2  4800.8  4847.0  4895.1  4936.7  4936.7  4938.3  4938.3  4938.9
  4944.2  4946.4  5048.5  5048.5  5054.1  5056.1  5059.4  5060.9  5061.1  5061.1
  5094.6  5144.7  5197.7  5365.6  5476.6  5694.3  5835.2  5996.3
  765.47  763.79  757.25  752.45  749.40  749.00  749.43  750.33  751.42  751.92
  751.44  751.93  751.91  752.00  752.25  752.51  752.51  752.52  752.18  754.47
  754.45  754.88  755.59  755.59  755.63  755.20  755.27  755.24  752.69  753.36
  753.59  753.99  754.26  757.63  761.62  773.48  784.50  796.84
  717.61  717.61  717.61  717.61  717.61  717.61  717.61  717.61  717.61  717.61
  717.61  717.61  717.61  717.61  717.61  717.61  751.01  751.02  751.02  751.03
  751.06  751.08  751.78  717.61  717.61  717.61  717.61  717.61  717.61  717.61
  717.61  717.61  717.61  717.61  717.61  717.61  717.61  717.61
Pier Skew, UpSta & Num, DnSta & Num=,4982.7,2,4982.7,2,0,0,0,0,0
       3       3
  737.38  751.33
       3       3
  738.52  751.33
Pier Skew, UpSta & Num, DnSta & Num=,5018.6,2,5018.6,2,0,0,0,0,0
       3       3
  737.78  751.57
       3       3
  738.92  751.57
BR Coef=1,1,0,1.25,0,,,0.8,0,2,0,
WSPro=,,,, 1 ,,,, 0 ,,,, 0 ,,,,-1 ,-1 ,-1 , 0 , 0 , 0 , 0 , 0
BC Design=,,0,,0,,,,,,

Type RM Length L Ch R = 1,106398,639,712,819
BEGIN DESCRIPTION:
Bell Farm Rd (FC) ds
END DESCRIPTION:
XS GIS Cut Line= 4
      1467853.78       743441.41      1467484.08       742317.08
      1467392.02       742016.33      1466996.79       741247.88
#Sta/Elev= 30
  3676.8  764.88  4457.3  747.03  4475.9  744.97  4883.5  745.68  4898.9  747.36
  4956.5  744.15  4982.7  738.52  5001.7  737.45  5018.6  738.92  5021.2  741.58
  5032.4  744.37  5050.9  748.58  5095.7  749.19  5160.5  748.68  5193.9  750.96
  5246.2  752.17  5278.2  748.45  5294.6  745.53  5328.8  746.80  5409.8  744.18
  5515.5  746.54  5627.9  755.59  5713.8  756.28  5762.0  759.71  5876.2  775.42
  5893.5  781.73  5928.5  785.73  5947.9  791.34  5990.6  796.37  6039.0  798.17
#Mann=9,-1,0
  3676.8    0.09       0  4883.5    0.15       0  4956.5   0.045       0
  5032.4    0.15       0  5095.7    0.09       0  5160.5    0.12       0
  5193.9    0.09       0  5278.2    0.15       0  5515.5    0.12       0
#XS Ineff=3,-1
 4337.00 4844.20  748.00 5097.40 5243.70  750.12 5243.80 5979.00  788.31
Permanent Ineff=
       F       F       F
Bank Sta=4956.5,5032.4
XS Rating Curve= 0
Exp/Cntr=0.5,0.3

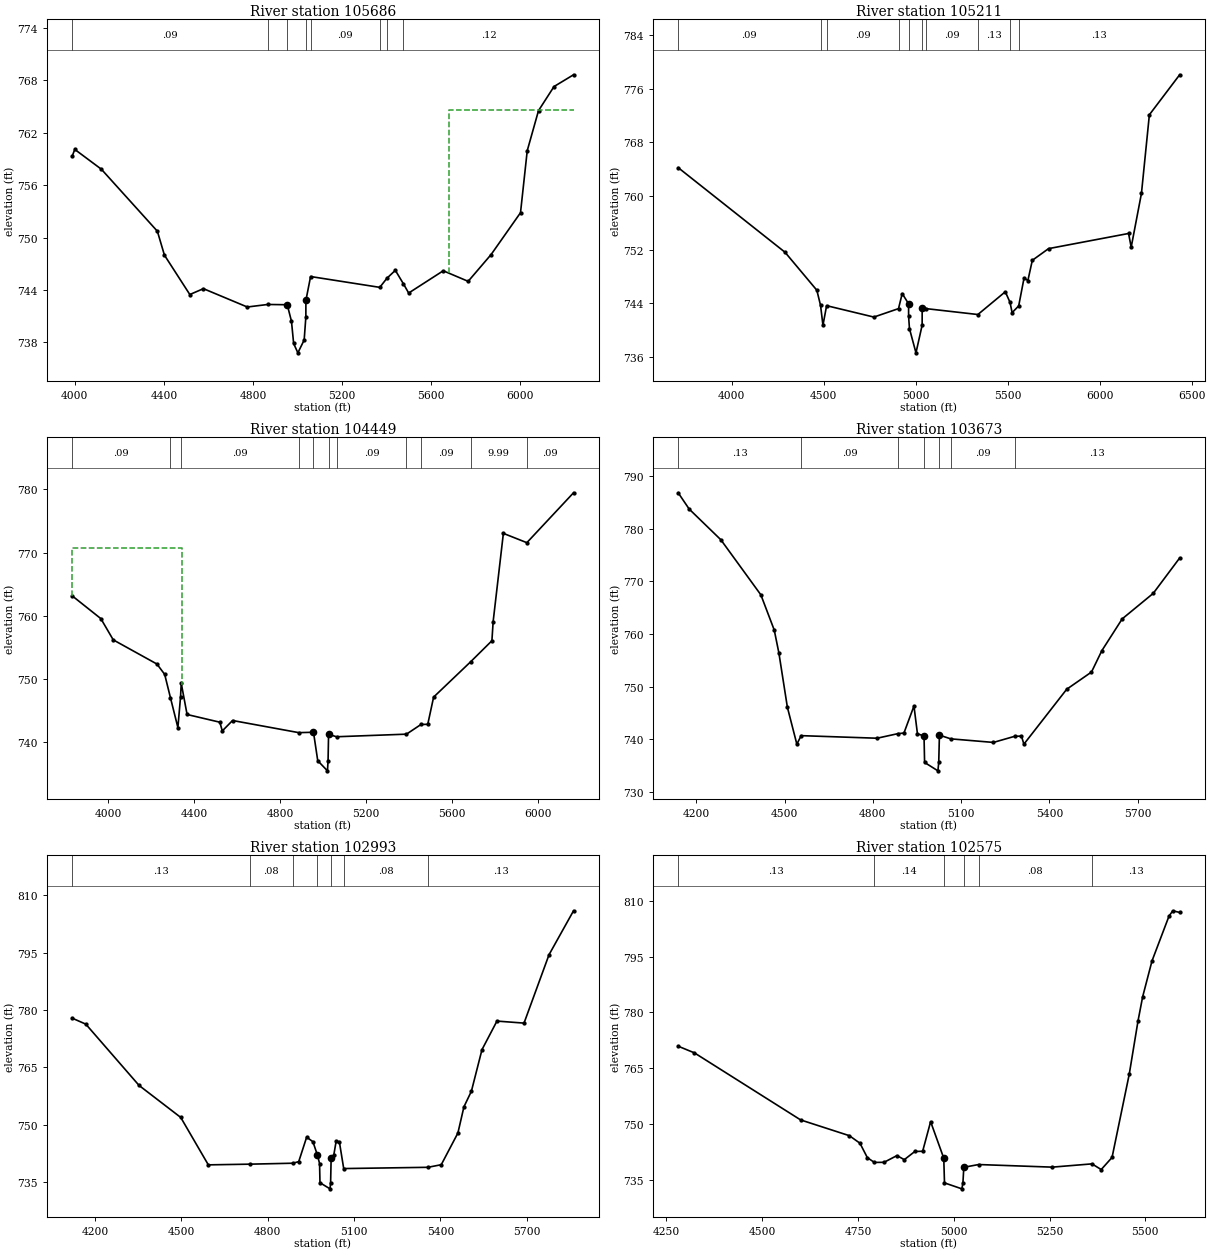
Type RM Length L Ch R = 1,105686,479,475,489
BEGIN DESCRIPTION:
Fourth Creek 154.0
END DESCRIPTION:
XS GIS Cut Line= 4
      1468008.56       743224.01      1468125.39       742873.52
      1468168.43       741889.65      1467842.53       741053.37
#Sta/Elev= 30
  3987.7  759.29  4000.0  760.10  4119.4  757.83  4370.8  750.73  4402.5  747.99
  4516.5  743.48  4577.6  744.15  4774.5  742.05  4866.3  742.34  4954.0  742.31
  4973.0  740.41  4982.7  737.87  5001.7  736.80  5030.0  738.27  5037.6  740.93
  5037.7  742.80  5058.8  745.54  5369.5  744.30  5401.8  745.35  5439.4  746.25
  5476.0  744.69  5499.2  743.65  5654.5  746.20  5766.4  744.99  5869.4  748.06
  6001.4  752.85  6031.6  759.95  6082.2  764.54  6151.8  767.30  6239.5  768.65
#Mann=8,-1,0
  3987.7    0.09       0  4866.3    0.15       0  4954.0   0.045       0
  5037.7    0.15       0  5058.8    0.09       0  5369.5    0.12       0
  5401.8    0.09       0  5476.0    0.12       0
#XS Ineff=2,0
       0                 5679.70    0.00  764.62
Permanent Ineff=
       F       F
Bank Sta=4954,5037.7
XS Rating Curve= 0
Exp/Cntr=0.3,0.1

Type RM Length L Ch R = 1,105211,758,762,774
BEGIN DESCRIPTION:
Fourth Creek 153.0
END DESCRIPTION:
XS GIS Cut Line= 4
      1468596.37       743552.26      1468627.04       742266.51
      1468680.29       741624.31      1469129.11       740967.90
#Sta/Elev= 30
  3709.2  764.22  4290.0  751.61  4462.9  745.95  4483.0  743.70  4496.1  740.73
  4516.0  743.65  4772.9  741.95  4906.8  743.21  4926.9  745.45  4961.6  743.93
  4961.7  742.04  4966.3  740.23  5001.7  736.62  5035.3  740.75  5035.4  743.25
  5056.4  743.21  5338.2  742.33  5487.2  745.72  5513.0  744.14  5524.2  742.61
  5560.0  743.61  5589.1  747.77  5610.0  747.40  5634.1  750.41  5722.3  752.15
  6157.3  754.41  6171.5  752.37  6227.3  760.39  6270.3  772.10  6434.9  778.06
#Mann=10,-1,0
  3709.2    0.09       0  4483.0    0.05       0  4516.0    0.09       0
  4906.8    0.15       0  4961.6   0.045       0  5035.4    0.15       0
  5056.4    0.09       0  5338.2    0.13       0  5513.0    0.05       0
  5560.0    0.13       0
Bank Sta=4961.6,5035.4
XS Rating Curve= 0
Exp/Cntr=0.3,0.1

Type RM Length L Ch R = 1,104449,777,776,776
BEGIN DESCRIPTION:
Fourth Creek 152.0
END DESCRIPTION:
XS GIS Cut Line= 4
      1469656.53       743425.30      1469370.40       742701.55
      1469386.70       742319.59      1469471.39       741147.41
#Sta/Elev= 30
  3831.6  763.19  3965.7  759.57  4023.5  756.21  4226.9  752.39  4263.0  750.76
  4290.0  747.05  4324.6  742.34  4337.0  747.24  4340.2  749.35  4367.4  744.41
  4519.9  743.19  4531.4  741.81  4579.2  743.46  4887.6  741.54  4956.2  741.60
  4976.0  737.10  5021.3  735.50  5024.1  737.11  5026.4  741.28  5063.4  740.89
  5389.3  741.30  5456.8  742.83  5488.4  742.86  5515.7  747.16  5688.6  752.76
  5787.2  756.07  5793.0  759.11  5840.6  773.05  5950.0  771.58  6167.4  779.47
#Mann=11,-1,0
  3831.6    0.09       0  4290.0    0.05       0  4337.0    0.09       0
  4887.6    0.15       0  4956.2   0.042       0  5026.4    0.15       0
  5063.4    0.09       0  5389.3    0.13       0  5456.8    0.09       0
  5688.6    9.99       0  5950.0    0.09       0
#XS Ineff=2,0
    0.00 4341.40  770.66               0
Permanent Ineff=
       F       F
Bank Sta=4956.2,5026.4
XS Rating Curve= 0
Exp/Cntr=0.3,0.1

Type RM Length L Ch R = 1,103673,741,680,631
BEGIN DESCRIPTION:
Fourth Creek 150.0
END DESCRIPTION:
XS GIS Cut Line= 4
      1470308.90       743164.77      1470139.04       742905.25
      1470162.63       742348.49      1470214.53       741513.33
#Sta/Elev= 30
  4138.6  786.89  4176.0  783.79  4283.7  777.94  4419.6  767.46  4465.1  760.75
  4480.8  756.41  4509.7  746.06  4541.9  739.03  4556.5  740.65  4814.5  740.16
  4886.0  741.04  4905.8  741.14  4939.9  746.29  4951.7  741.02  4974.1  740.57
  4976.0  735.55  5021.3  733.95  5024.1  735.56  5026.4  740.75  5064.9  740.04
  5209.9  739.36  5282.5  740.53  5305.2  740.56  5313.5  739.03  5458.9  749.48
  5543.2  752.76  5578.4  756.83  5647.5  762.88  5753.0  767.74  5842.8  774.47
#Mann=7,-1,0
  4138.6    0.13       0  4556.5    0.09       0  4886.0    0.15       0
  4974.1   0.042       0  5026.4    0.15       0  5064.9    0.09       0
  5282.5    0.13       0
Bank Sta=4974.1,5026.4
XS Rating Curve= 0
Exp/Cntr=0.3,0.1

Type RM Length L Ch R = 1,102993,425,418,391
BEGIN DESCRIPTION:
Fourth Creek 149.0 (Survey)
END DESCRIPTION:
XS GIS Cut Line= 5
      1471073.27       743103.41      1470889.26       742442.85
      1470823.64       742259.66      1470733.55       741886.09
      1470813.77       741414.24
#Sta/Elev= 30
  4119.7  777.89  4167.5  776.31  4352.7  760.28  4497.5  751.92  4593.4  739.52
  4736.9  739.70  4888.2  739.95  4907.7  740.38  4935.2  746.76  4956.9  745.58
  4972.7  742.06  4980.1  739.87  4981.5  734.85  5016.4  733.25  5018.5  734.86
  5020.3  741.19  5029.5  742.08  5037.8  745.72  5049.0  745.51  5064.0  738.55
  5356.8  738.88  5403.1  739.56  5460.9  747.83  5481.9  754.69  5507.9  758.78
  5544.7  769.65  5596.7  777.11  5690.8  776.58  5777.7  794.46  5862.9  805.95
#Mann=7,-1,0
  4119.7    0.13       0  4736.9    0.08       0  4888.2    0.14       0
  4972.7   0.042       0  5020.3    0.14       0  5064.0    0.08       0
  5356.8    0.13       0
Bank Sta=4972.7,5020.3
XS Rating Curve= 0
Exp/Cntr=0.3,0.1

Type RM Length L Ch R = 1,102575,595,585,600
BEGIN DESCRIPTION:
Fourth Creek 148.0
END DESCRIPTION:
XS GIS Cut Line= 3
      1471491.32       742800.52      1471222.37       742135.22
      1470967.60       741602.07
#Sta/Elev= 30
  4281.1  770.92  4323.6  769.12  4600.6  751.08  4727.7  746.84  4755.4  744.81
  4774.7  740.93  4793.0  739.64  4818.2  739.67  4852.0  741.48  4871.1  740.38
  4898.7  742.59  4919.0  742.64  4939.8  750.61  4974.1  740.78  4976.0  734.13
  5021.3  732.53  5024.1  734.14  5026.4  738.33  5065.1  739.07  5257.1  738.37
  5360.8  739.25  5384.9  737.72  5413.2  740.98  5458.0  763.34  5480.9  777.69
  5493.0  784.20  5517.4  793.86  5561.8  805.93  5571.7  807.37  5589.6  806.92
#Mann=6,-1,0
  4281.1    0.13       0  4793.0    0.14       0  4974.1   0.042       0
  5026.4    0.14       0  5065.1    0.08       0  5360.8    0.13       0
Bank Sta=4974.1,5026.4
XS Rating Curve= 0
Exp/Cntr=0.3,0.1