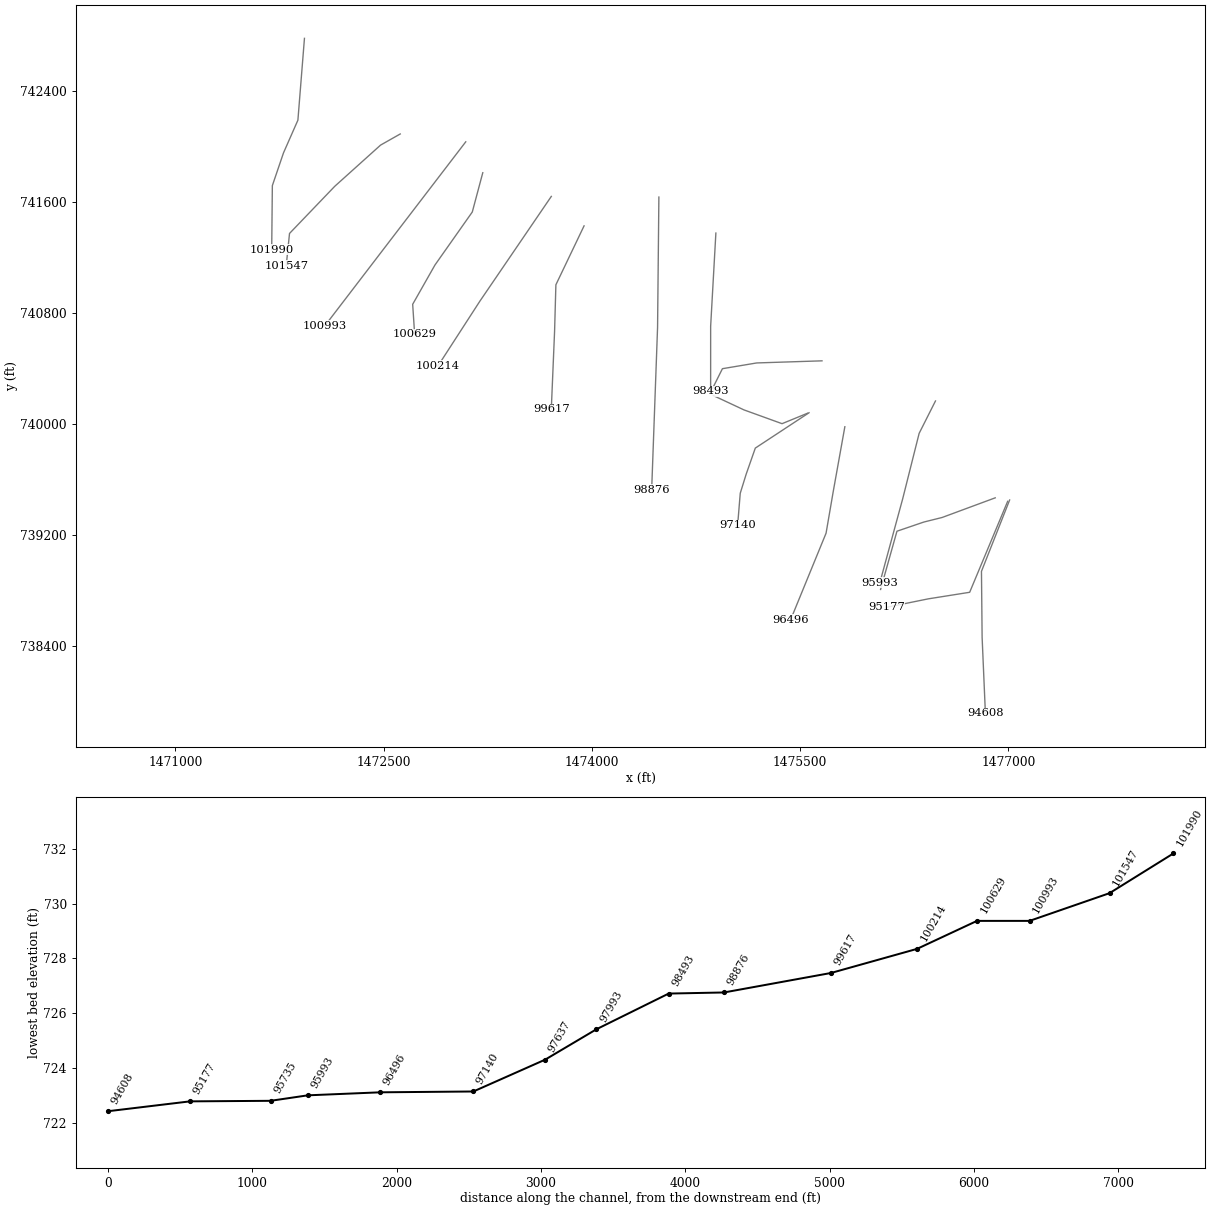
HEC-RAS study Fourth Creek.prj: Fourth Creek Detailed Study

--- Fourth Creek.g01 (geometry) --- (continued)

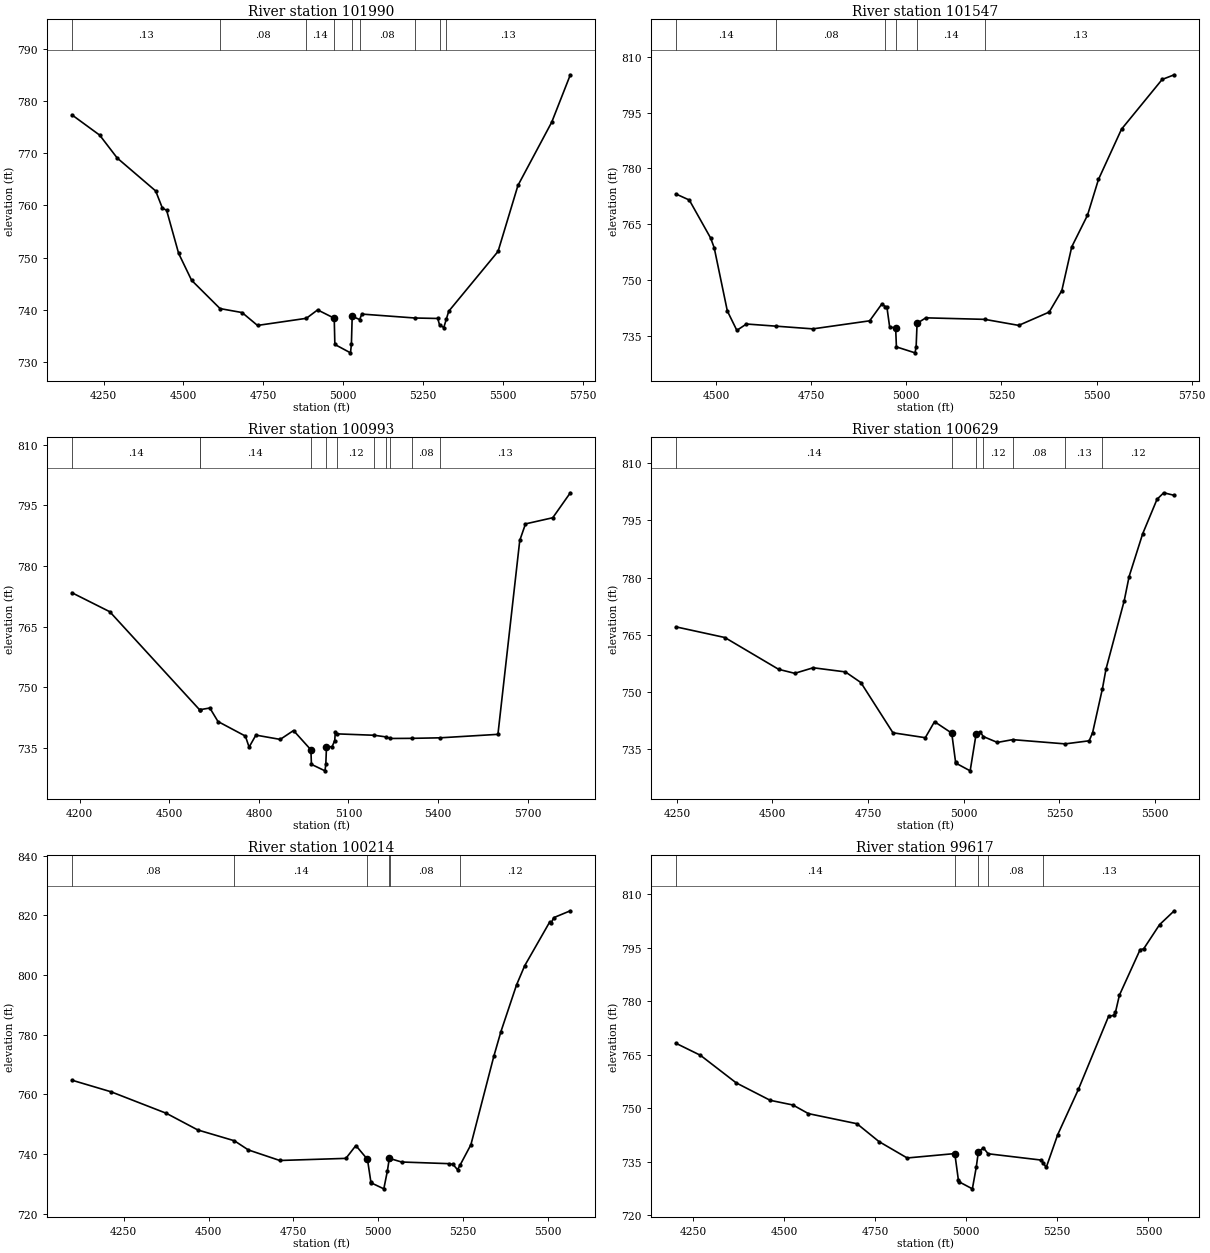
Type RM Length L Ch R = 1,101990,516,443,392
BEGIN DESCRIPTION:
Fourth Creek 147.0
END DESCRIPTION:
XS GIS Cut Line= 5
      1471930.13       742781.66      1471882.94       742191.84
      1471779.14       741955.92      1471698.93       741720.00
      1471694.21       741257.55
#Sta/Elev= 30
  4150.5  777.33  4237.5  773.45  4292.5  769.07  4412.9  762.78  4434.1  759.46
  4447.0  759.11  4484.8  750.84  4525.4  745.70  4614.5  740.29  4683.5  739.53
  4731.8  737.07  4884.8  738.43  4920.1  740.04  4972.1  738.45  4974.1  733.43
  5023.0  731.83  5025.9  733.44  5028.4  738.83  5051.7  738.19  5058.6  739.24
  5224.8  738.49  5296.3  738.40  5302.0  737.17  5315.2  736.66  5323.0  738.23
  5330.7  739.78  5485.2  751.22  5547.5  763.83  5653.4  775.94  5711.6  784.99
#Mann=9,-1,0
  4150.5    0.13       0  4614.5    0.08       0  4884.8    0.14       0
  4972.1   0.042       0  5028.4    0.14       0  5051.7    0.08       0
  5224.8    0.13       0  5302.0    0.05       0  5323.0    0.13       0
Bank Sta=4972.1,5028.4
XS Rating Curve= 0
Exp/Cntr=0.3,0.1

Type RM Length L Ch R = 1,101547,531,554,575
BEGIN DESCRIPTION:
Fourth Creek 146.0
END DESCRIPTION:
XS GIS Cut Line= 5
      1472619.95       742092.28      1472478.40       742012.07
      1472148.12       741714.81      1471822.55       741375.09
      1471798.96       741143.87
#Sta/Elev= 30
  4394.3  773.15  4429.7  771.51  4485.8  761.28  4495.2  758.66  4529.7  741.65
  4554.7  736.43  4579.9  738.14  4656.5  737.57  4754.5  736.83  4903.8  739.00
  4935.7  743.53  4944.6  742.84  4949.2  742.60  4956.3  737.38  4972.1  737.00
  4974.1  731.98  5023.0  730.38  5025.9  731.99  5028.4  738.32  5051.4  739.80
  5206.2  739.39  5295.5  737.77  5375.6  741.35  5408.8  747.13  5434.9  758.91
  5476.3  767.42  5505.1  777.04  5565.7  790.58  5672.5  803.96  5704.3  805.22
#Mann=6,-1,0
  4394.3    0.14       0  4656.5    0.08       0  4944.6    0.14       0
  4972.1   0.042       0  5028.4    0.14       0  5206.2    0.13       0
Bank Sta=4972.1,5028.4
XS Rating Curve= 0
Exp/Cntr=0.3,0.1

Type RM Length L Ch R = 1,100993,360,364,388
BEGIN DESCRIPTION:
Fourth Creek 145.0
END DESCRIPTION:
XS GIS Cut Line= 3
      1473091.80       742035.67      1472589.56       741379.52
      1472077.37       740709.84
#Sta/Elev= 30
  4173.7  773.39  4300.6  768.69  4601.5  744.45  4601.8  744.47  4635.7  744.90
  4663.0  741.56  4754.7  737.96  4767.2  735.23  4789.9  738.20  4871.4  737.14
  4916.0  739.33  4974.1  734.57  4976.0  730.97  5021.3  729.37  5024.1  730.98
  5026.4  735.29  5045.1  735.34  5054.0  736.84  5055.9  738.95  5060.6  738.51
  5186.6  738.16  5225.1  737.76  5240.3  737.37  5311.6  737.40  5407.0  737.53
  5600.6  738.39  5673.7  786.31  5692.9  790.40  5784.2  791.92  5843.1  798.09
#Mann=11,-1,0
  4173.7    0.14       0  4601.5    0.08       0  4601.8    0.14       0
  4974.1   0.042       0  5026.4    0.14       0  5060.6    0.12       0
  5186.6    0.13       0  5225.1    0.08       0  5240.3    0.13       0
  5311.6    0.08       0  5407.0    0.13       0
Bank Sta=4974.1,5026.4
XS Rating Curve= 0
Exp/Cntr=0.3,0.1

Type RM Length L Ch R = 1,100629,415,415,407
BEGIN DESCRIPTION:
Fourth Creek 144.0
END DESCRIPTION:
XS GIS Cut Line= 5
      1473214.45       741812.91      1473138.97       741529.85
      1472870.03       741147.66      1472709.60       740864.56
      1472723.76       740647.50
#Sta/Elev= 30
  4247.3  767.09  4375.5  764.29  4516.1  755.96  4558.3  754.91  4606.5  756.37
  4690.7  755.28  4731.1  752.50  4815.0  739.34  4899.6  738.05  4923.7  742.25
  4968.7  739.25  4978.6  731.79  4980.4  731.34  5016.9  729.37  5032.4  739.00
  5043.9  739.43  5051.3  738.35  5088.0  736.81  5128.0  737.54  5265.2  736.43
  5328.1  737.24  5337.1  739.39  5362.8  750.93  5372.1  756.04  5419.7  773.93
  5432.5  780.27  5467.9  791.45  5505.5  800.50  5523.0  802.20  5550.5  801.53
#Mann=7,-1,0
  4247.3    0.14       0  4968.7   0.042       0  5032.4    0.14       0
  5051.3    0.12       0  5128.0    0.08       0  5265.2    0.13       0
  5362.8    0.12       0
Bank Sta=4968.7,5032.4
XS Rating Curve= 0
Exp/Cntr=0.3,0.1

Type RM Length L Ch R = 1,100214,513,597,653
BEGIN DESCRIPTION:
Fourth Creek 143.0
END DESCRIPTION:
XS GIS Cut Line= 3
      1473708.00       741642.14      1473193.70       740887.21
      1472891.73       740420.09
#Sta/Elev= 30
  4097.2  764.76  4212.6  760.87  4375.7  753.66  4468.4  748.08  4576.2  744.46
  4617.4  741.39  4710.1  737.85  4905.2  738.56  4934.5  742.86  4968.7  738.23
  4978.6  730.77  4980.4  730.32  5016.9  728.35  5027.6  734.43  5033.3  738.70
  5036.6  738.45  5069.4  737.34  5208.7  736.79  5221.2  736.51  5234.2  734.76
  5242.6  736.47  5273.7  743.13  5341.3  772.77  5362.2  781.02  5408.3  796.68
  5432.1  803.06  5505.9  817.73  5511.1  817.57  5517.8  819.21  5566.9  821.52
#Mann=6,-1,0
  4097.2    0.08       0  4576.2    0.14       0  4968.7   0.042       0
  5033.3    0.14       0  5036.6    0.08       0  5242.6    0.12       0
Bank Sta=4968.7,5033.3
XS Rating Curve= 0
Exp/Cntr=0.3,0.1

Type RM Length L Ch R = 1,99617,740,741,765
BEGIN DESCRIPTION:
Fourth Creek 142.0
END DESCRIPTION:
XS GIS Cut Line= 4
      1473943.93       741429.84      1473741.03       741005.17
      1473731.60       740670.17      1473708.00       740108.65
#Sta/Elev= 30
  4203.1  768.28  4270.6  764.90  4368.8  757.17  4462.1  752.28  4524.4  750.97
  4567.0  748.55  4700.2  745.72  4760.6  740.72  4838.0  736.12  4968.7  737.35
  4978.6  729.89  4980.4  729.44  5016.9  727.47  5027.6  733.55  5033.3  737.82
  5047.2  738.94  5060.2  737.30  5206.0  735.53  5210.6  734.83  5219.6  733.47
  5251.1  742.65  5307.8  755.33  5390.9  775.88  5405.6  776.07  5409.6  776.97
  5420.4  781.74  5477.3  794.52  5486.8  794.71  5530.6  801.51  5570.9  805.40
#Mann=5,-1,0
  4203.1    0.14       0  4968.7   0.042       0  5033.3    0.14       0
  5060.2    0.08       0  5210.6    0.13       0
Bank Sta=4968.7,5033.3
XS Rating Curve= 0
Exp/Cntr=0.3,0.1

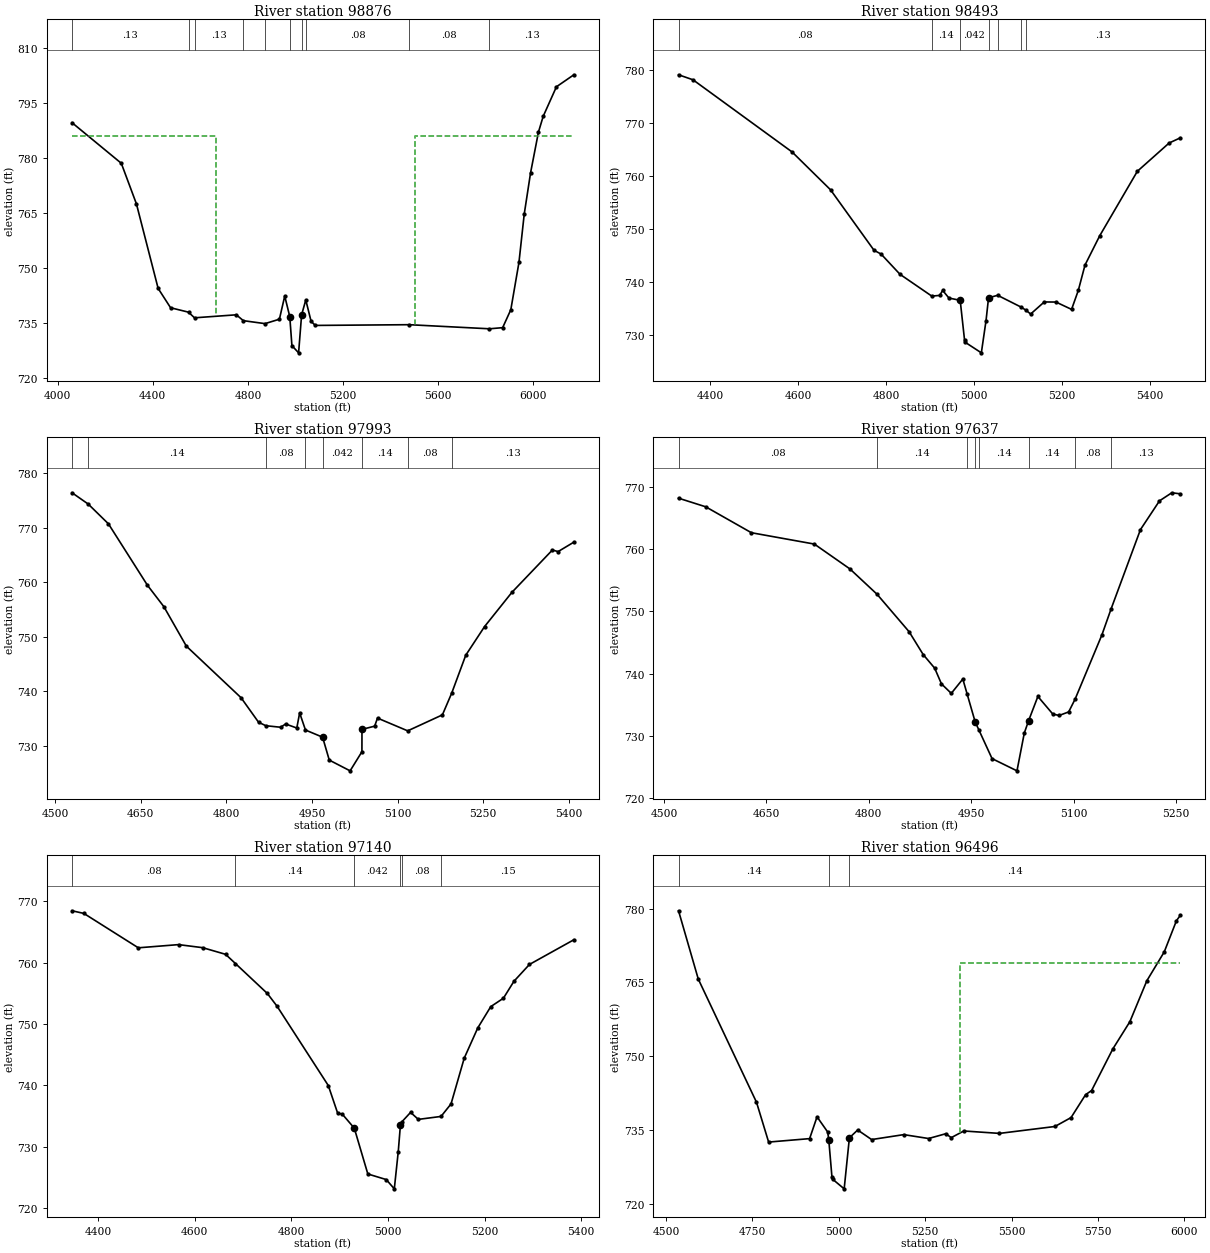
Type RM Length L Ch R = 1,98876,390,383,465
BEGIN DESCRIPTION:
Fourth Creek 141.0 (Survey)
END DESCRIPTION:
XS GIS Cut Line= 3
      1474482.76       741637.44      1474473.32       740698.48
      1474430.86       739528.36
#Sta/Elev= 30
  4060.5  789.63  4267.5  778.55  4331.1  767.46  4422.4  744.36  4474.7  739.08
  4550.1  737.87  4575.3  736.33  4751.1  737.15  4780.7  735.55  4871.8  734.74
  4932.3  735.95  4954.7  742.28  4975.9  736.64  4984.9  728.73  5013.0  726.76
  5025.6  737.11  5043.2  741.21  5065.6  735.36  5083.4  734.25  5477.6  734.45
  5815.6  733.33  5871.0  733.64  5905.3  738.54  5939.5  751.45  5961.7  764.65
  5988.4  775.95  6021.6  787.09  6041.6  791.40  6097.1  799.45  6170.4  802.73
#Mann=10,-1,0
  4060.5    0.13       0  4550.1    0.08       0  4575.3    0.13       0
  4780.7    0.08       0  4871.8    0.14       0  4975.9   0.042       0
  5025.6    0.14       0  5043.2    0.08       0  5477.6    0.08       0
  5815.6    0.13       0
#XS Ineff=2,0
    0.00 4666.90  786.05 5503.50    0.00  786.05
Permanent Ineff=
       F       F
Bank Sta=4975.9,5025.6
XS Rating Curve= 0
Exp/Cntr=0.3,0.1

Type RM Length L Ch R = 1,98493,638,500,352
BEGIN DESCRIPTION:
Fourth Creek 140.0
END DESCRIPTION:
XS GIS Cut Line= 3
      1474893.26       741377.96      1474855.60       740706.21
      1474855.51       740236.11
#Sta/Elev= 30
  4327.2  779.01  4360.1  778.07  4585.9  764.49  4673.4  757.38  4772.4  746.01
  4788.6  745.29  4831.6  741.49  4904.0  737.39  4922.0  737.52  4928.8  738.46
  4943.1  737.02  4968.7  736.60  4978.6  729.14  4980.4  728.69  5016.9  726.72
  5027.6  732.80  5033.3  737.07  5054.0  737.54  5107.7  735.31  5117.5  734.79
  5129.2  734.02  5160.2  736.29  5186.9  736.27  5222.4  734.89  5237.7  738.45
  5253.0  743.23  5286.6  748.75  5372.2  760.86  5444.6  766.18  5470.1  767.15
#Mann=7,-1,0
  4327.2    0.08       0  4904.0    0.14       0  4968.7   0.042       0
  5033.3    0.14       0  5054.0    0.08       0  5107.7    0.08       0
  5117.5    0.13       0
Bank Sta=4968.7,5033.3
XS Rating Curve= 0
Exp/Cntr=0.3,0.1

Type RM Length L Ch R = 1,97993,386,356,312
BEGIN DESCRIPTION:
Fourth Creek 139.0
END DESCRIPTION:
XS GIS Cut Line= 4
      1475657.61       740456.90      1475187.66       740441.72
      1474940.44       740400.28      1474869.68       740258.75
#Sta/Elev= 30
  4529.8  776.39  4558.1  774.32  4593.5  770.70  4661.9  759.43  4690.7  755.50
  4730.0  748.28  4825.9  738.82  4856.5  734.33  4869.3  733.69  4895.2  733.41
  4903.9  734.01  4923.5  733.27  4928.5  736.04  4938.7  732.90  4968.7  731.59
  4980.4  727.39  5016.9  725.42  5037.6  728.92  5037.7  733.02  5059.9  733.61
  5064.9  735.09  5117.8  732.75  5178.6  735.68  5195.0  739.69  5219.5  746.61
  5252.5  751.87  5300.3  758.13  5371.3  765.90  5381.3  765.61  5408.9  767.34
#Mann=8,-1,0
  4529.8    0.08       0  4558.1    0.14       0  4869.3    0.08       0
  4938.7    0.14       0  4968.7   0.042       0  5037.7    0.14       0
  5117.8    0.08       0  5195.0    0.13       0
Bank Sta=4968.7,5037.7
XS Rating Curve= 0
Exp/Cntr=0.3,0.1

Type RM Length L Ch R = 1,97637,418,497,584
BEGIN DESCRIPTION:
Fourth Creek 138.0
END DESCRIPTION:
XS GIS Cut Line= 4
      1475553.80       740079.42      1475369.81       740003.93
      1475096.15       740103.02      1474874.36       740206.83
#Sta/Elev= 30
  4521.3  768.27  4561.1  766.88  4628.0  762.70  4720.2  760.87  4772.2  756.87
  4811.9  752.79  4859.0  746.73  4879.6  743.05  4896.4  740.86  4906.3  738.33
  4920.7  736.80  4937.6  739.11  4943.9  736.70  4955.7  732.19  4961.0  730.93
  4980.4  726.28  5016.9  724.31  5027.6  730.39  5033.8  732.36  5047.5  736.30
  5069.4  733.46  5078.7  733.24  5092.6  733.81  5102.1  735.89  5141.2  746.21
  5154.7  750.41  5197.7  763.20  5225.6  767.84  5243.6  769.14  5256.1  768.97
#Mann=8,-1,0
  4521.3    0.08       0  4811.9    0.14       0  4943.9    0.08       0
  4955.7   0.042       0  4961.0    0.14       0  5033.8    0.14       0
  5102.1    0.08       0  5154.7    0.13       0
Bank Sta=4955.7,5033.8
XS Rating Curve= 0
Exp/Cntr=0.3,0.1

Type RM Length L Ch R = 1,97140,635,644,667
BEGIN DESCRIPTION:
Fourth Creek 137.0
END DESCRIPTION:
XS GIS Cut Line= 5
      1475564.21       740082.73      1475177.30       739827.94
      1475111.25       739639.20      1475068.78       739502.37
      1475049.90       739271.13
#Sta/Elev= 30
  4346.1  768.43  4370.5  768.00  4483.2  762.40  4566.5  762.92  4616.5  762.42
  4663.8  761.34  4684.2  759.84  4750.3  754.96  4770.5  752.87  4876.4  739.97
  4895.8  735.46  4905.3  735.32  4930.2  733.03  4958.2  725.57  4996.3  724.66
  5013.0  723.15  5021.2  729.23  5025.6  733.50  5028.4  734.04  5046.7  735.60
  5062.7  734.46  5109.7  734.94  5130.4  736.98  5157.7  744.43  5185.7  749.35
  5212.6  752.82  5238.8  754.19  5260.6  756.95  5292.7  759.69  5384.6  763.71
#Mann=6,-1,0
  4346.1    0.08       0  4684.2    0.14       0  4930.2   0.042       0
  5025.6    0.14       0  5028.4    0.08       0  5109.7    0.15       0
Bank Sta=4930.2,5025.6
XS Rating Curve= 0
Exp/Cntr=0.3,0.1

Type RM Length L Ch R = 1,96496,516,503,522
BEGIN DESCRIPTION:
Fourth Creek 136.0
END DESCRIPTION:
XS GIS Cut Line= 4
      1475822.18       739981.77      1475738.79       739516.53
      1475686.89       739214.55      1475432.09       738591.71
#Sta/Elev= 30
  4536.3  779.54  4593.5  765.67  4761.9  740.69  4797.0  732.61  4915.6  733.31
  4937.1  737.73  4968.0  734.64  4971.1  733.00  4980.2  725.54  4981.9  725.09
  5015.6  723.12  5030.7  733.47  5054.7  735.06  5095.0  733.12  5188.1  734.12
  5259.9  733.33  5309.5  734.30  5325.5  733.51  5361.8  734.86  5465.0  734.37
  5625.4  735.77  5672.1  737.58  5714.2  742.23  5731.6  743.07  5793.0  751.51
  5842.2  757.02  5891.4  765.34  5941.8  771.20  5977.1  777.53  5988.3  778.61
#Mann=3,-1,0
  4536.3    0.14       0  4971.1   0.042       0  5030.7    0.14       0
#XS Ineff=2,0
       0                 5350.00    0.00  769.00
Permanent Ineff=
       F       F
Bank Sta=4971.1,5030.7
XS Rating Curve= 0
Exp/Cntr=0.3,0.1

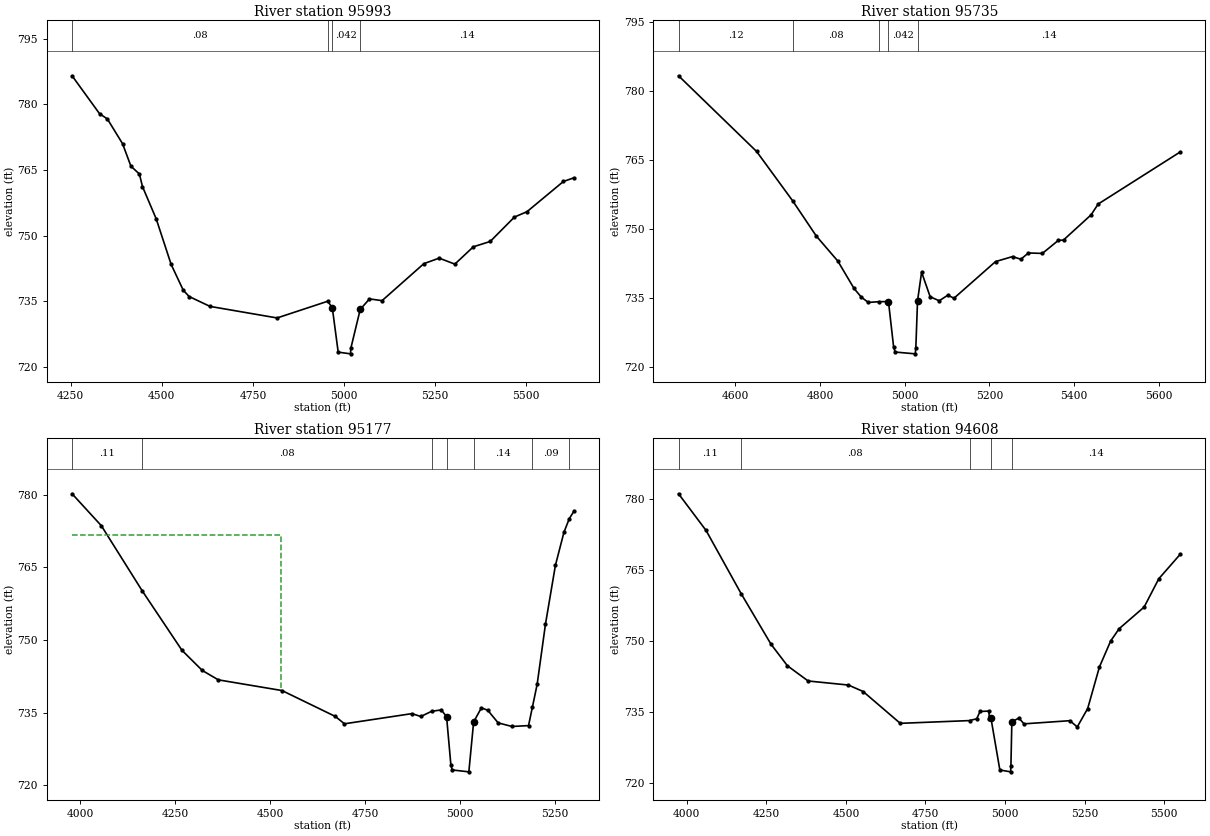
Type RM Length L Ch R = 1,95993,371,258,178
BEGIN DESCRIPTION:
Fourth Creek 135.0
END DESCRIPTION:
XS GIS Cut Line= 4
      1476474.85       740167.65      1476357.19       739934.04
      1476239.21       739464.19      1476073.80       738855.98
#Sta/Elev= 30
  4254.0  786.55  4329.4  777.88  4350.8  776.69  4392.5  771.03  4415.4  765.89
  4438.7  764.10  4447.1  761.23  4484.7  753.87  4525.8  743.43  4558.9  737.56
  4575.0  736.11  4632.3  733.85  4816.3  731.21  4954.9  735.02  4967.7  733.59
  4983.9  723.40  5017.7  723.01  5018.7  724.31  5044.3  733.15  5069.7  735.56
  5104.3  735.17  5218.9  743.62  5260.9  744.88  5303.9  743.51  5354.6  747.47
  5400.9  748.69  5467.4  754.27  5501.7  755.49  5601.6  762.40  5630.3  763.23
#Mann=4,-1,0
  4254.0    0.08       0  4954.9    0.14       0  4967.7   0.042       0
  5044.3    0.14       0
Bank Sta=4967.7,5044.3
XS Rating Curve= 0
Exp/Cntr=0.3,0.1

Type RM Length L Ch R = 1,95735,561,558,557
BEGIN DESCRIPTION:
Fourth Creek 134.0
END DESCRIPTION:
XS GIS Cut Line= 5
      1476905.18       739469.35      1476522.98       739327.79
      1476390.87       739294.76      1476197.41       739228.71
      1476079.44       738808.73
#Sta/Elev= 30
  4466.1  783.34  4650.4  766.86  4735.7  756.09  4791.3  748.45  4842.1  743.00
  4880.3  737.05  4897.3  735.17  4914.0  734.00  4939.0  734.16  4961.6  734.19
  4973.8  724.28  4977.5  723.20  5024.8  722.81  5026.2  724.11  5030.2  734.33
  5039.8  740.59  5060.0  735.24  5081.4  734.36  5101.6  735.57  5116.3  734.92
  5214.3  742.89  5254.4  743.98  5274.2  743.40  5291.8  744.77  5324.9  744.67
  5362.3  747.49  5374.8  747.59  5439.7  753.05  5456.6  755.42  5650.5  766.77
#Mann=5,-1,0
  4466.1    0.12       0  4735.7    0.08       0  4939.0    0.14       0
  4961.6   0.042       0  5030.2    0.14       0
Bank Sta=4961.6,5030.2
XS Rating Curve= 0
Exp/Cntr=0.3,0.1

Type RM Length L Ch R = 1,95177,311,569,691
BEGIN DESCRIPTION:
Fourth Creek 133.0
END DESCRIPTION:
XS GIS Cut Line= 4
      1476994.82       739444.34      1476721.15       738788.48
      1476423.89       738741.30      1476121.90       738679.96
#Sta/Elev= 30
  3979.4  780.16  4056.4  773.57  4164.1  760.11  4268.5  747.86  4322.0  743.70
  4364.0  741.77  4531.6  739.56  4671.8  734.22  4695.8  732.70  4873.2  734.80
  4896.7  734.21  4925.1  735.28  4950.5  735.57  4964.4  734.17  4975.7  724.26
  4979.1  723.18  5023.0  722.79  5035.6  733.09  5056.1  736.01  5073.0  735.47
  5100.1  732.89  5136.5  732.15  5180.0  732.33  5190.2  736.16  5202.6  740.82
  5224.6  753.30  5250.7  765.40  5273.1  772.21  5287.2  775.03  5299.2  776.53
#Mann=7,-1,0
  3979.4    0.11       0  4164.1    0.08       0  4925.1    0.14       0
  4964.4   0.042       0  5035.6    0.14       0  5190.2    0.09       0
  5287.2    0.14       0
#XS Ineff=2,0
    0.00 4528.00  771.74               0
Permanent Ineff=
       F       F
Bank Sta=4964.4,5035.6
XS Rating Curve= 0
Exp/Cntr=0.3,0.1

Type RM Length L Ch R = 1,94608,678,743,795
BEGIN DESCRIPTION:
Fourth Creek 132.0
END DESCRIPTION:
XS GIS Cut Line= 4
      1477008.97       739453.78      1476806.08       738939.47
      1476810.80       738462.92      1476834.39       737915.59
#Sta/Elev= 30
  3973.9  781.13  4060.5  773.38  4170.5  760.07  4264.6  749.37  4316.2  744.82
  4381.3  741.61  4508.0  740.75  4554.1  739.39  4670.8  732.67  4888.7  733.25
  4911.2  733.64  4921.6  735.17  4949.3  735.26  4951.2  733.68  4955.8  733.82
  4983.9  722.82  5017.7  722.43  5018.7  723.73  5021.6  732.96  5043.8  733.80
  5059.7  732.56  5204.0  733.23  5227.2  731.91  5260.0  735.80  5297.0  744.59
  5332.4  750.07  5359.1  752.66  5437.4  757.21  5483.5  763.19  5551.2  768.38
#Mann=5,-1,0
  3973.9    0.11       0  4170.5    0.08       0  4888.7    0.14       0
  4955.8   0.042       0  5021.6    0.14       0
Bank Sta=4955.8,5021.6
XS Rating Curve= 0
Exp/Cntr=0.3,0.1