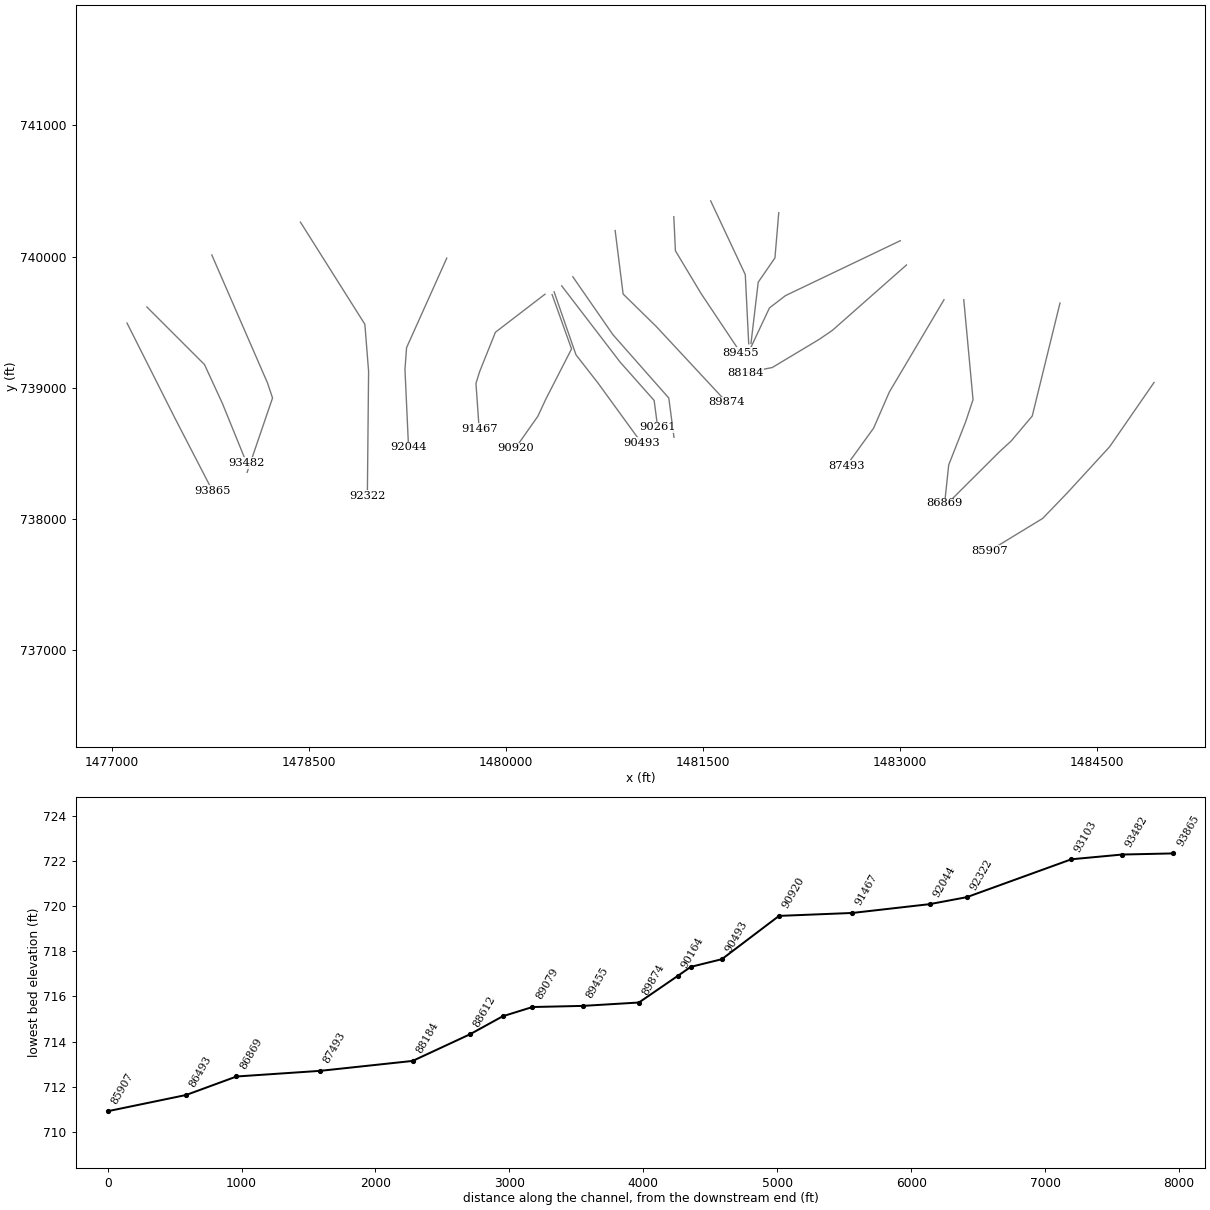
HEC-RAS study Fourth Creek.prj: Fourth Creek Detailed Study

--- Fourth Creek.g01 (geometry) --- (continued)

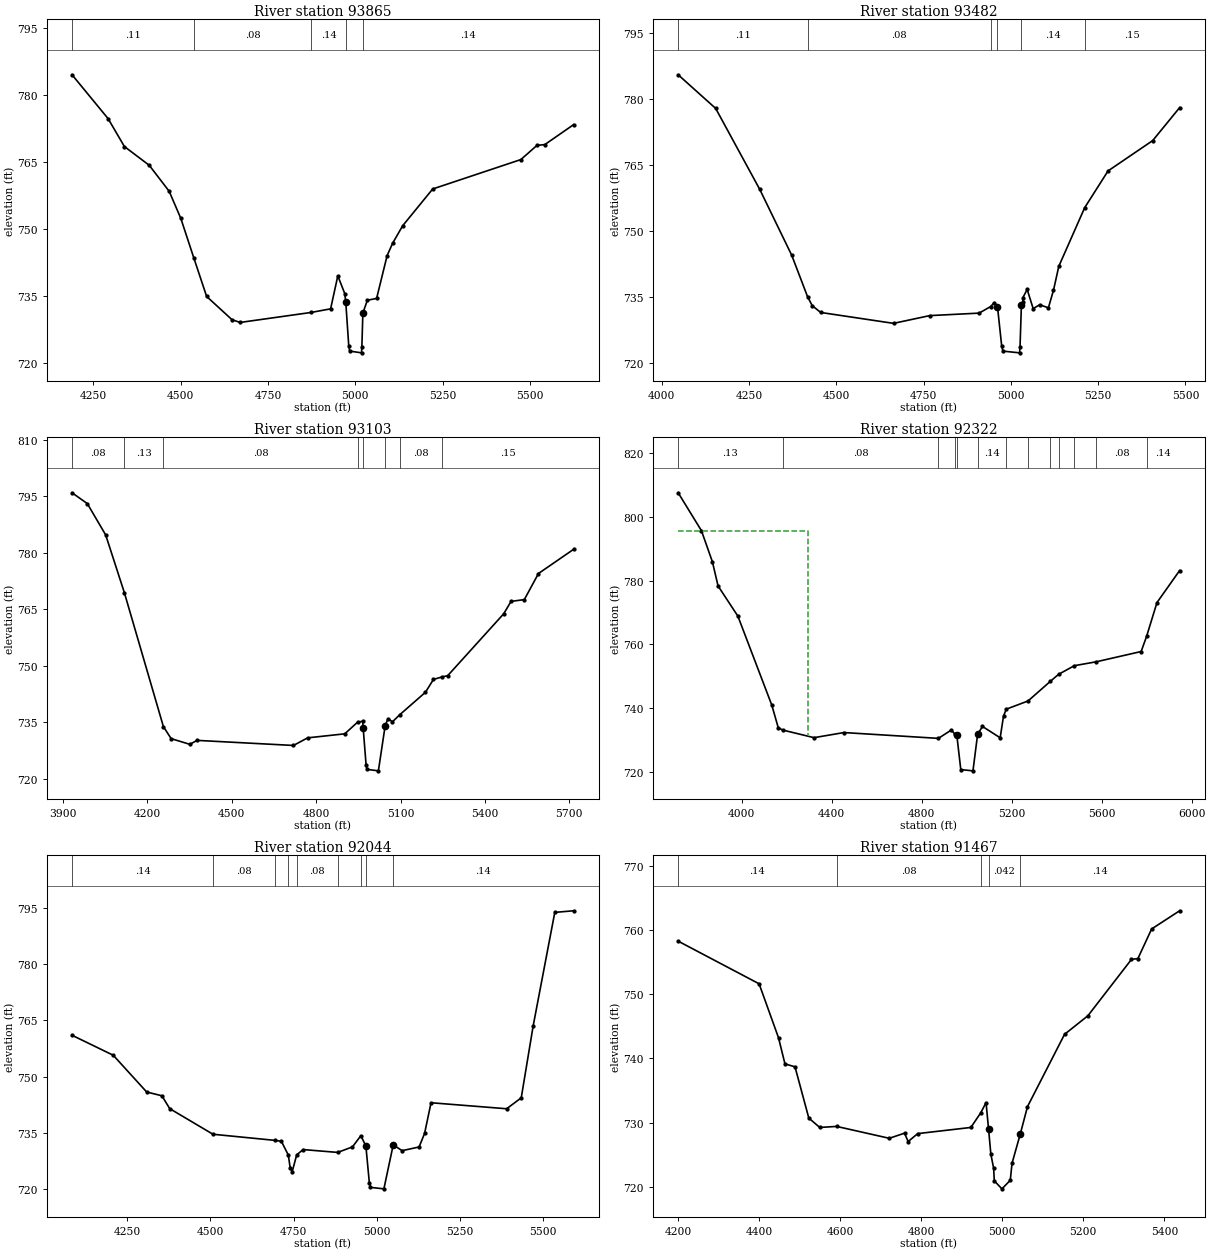
Type RM Length L Ch R = 1,93865,381,383,386
BEGIN DESCRIPTION:
Fourth Creek 131.0 (Survey)
END DESCRIPTION:
XS GIS Cut Line= 3
      1477113.70       739492.97      1477477.03       738771.03
      1477764.86       738214.24
#Sta/Elev= 30
  4189.4  784.45  4292.5  774.66  4339.2  768.42  4410.2  764.24  4467.3  758.43
  4500.7  752.36  4537.8  743.55  4574.5  734.94  4647.1  729.74  4670.4  729.13
  4874.2  731.37  4929.3  732.17  4949.9  739.54  4969.8  735.57  4972.6  733.72
  4981.3  723.81  4983.9  722.73  5017.7  722.34  5018.7  723.64  5021.6  731.23
  5034.5  734.10  5060.9  734.49  5091.0  744.06  5106.8  746.83  5135.7  750.75
  5221.4  758.94  5473.7  765.51  5519.7  768.67  5542.3  768.86  5624.4  773.30
#Mann=5,-1,0
  4189.4    0.11       0  4537.8    0.08       0  4874.2    0.14       0
  4972.6   0.042       0  5021.6    0.14       0
Bank Sta=4972.6,5021.6
XS Rating Curve= 0
Exp/Cntr=0.3,0.1

Type RM Length L Ch R = 1,93482,386,379,377
BEGIN DESCRIPTION:
Fourth Creek 130.0
END DESCRIPTION:
XS GIS Cut Line= 4
      1477264.73       739615.59      1477703.51       739176.81
      1477840.35       738879.55      1478024.37       738426.57
#Sta/Elev= 30
  4046.8  785.57  4154.3  777.91  4280.6  759.48  4372.2  744.49  4417.5  735.06
  4430.9  733.03  4455.1  731.48  4663.8  729.00  4767.4  730.76  4909.0  731.33
  4942.0  732.82  4952.5  733.73  4961.6  732.83  4973.8  723.76  4977.5  722.68
  5024.8  722.29  5026.2  723.59  5030.2  733.27  5034.4  733.80  5034.6  734.88
  5046.7  736.72  5063.9  732.35  5082.5  733.23  5107.5  732.54  5122.1  736.53
  5137.3  741.98  5211.5  755.33  5278.4  763.69  5406.4  770.60  5483.5  778.10
#Mann=6,-1,0
  4046.8    0.11       0  4417.5    0.08       0  4942.0    0.14       0
  4961.6   0.042       0  5030.2    0.14       0  5211.5    0.15       0
Bank Sta=4961.6,5030.2
XS Rating Curve= 0
Exp/Cntr=0.3,0.1

Type RM Length L Ch R = 1,93103,867,781,760
BEGIN DESCRIPTION:
Fourth Creek 129.0
END DESCRIPTION:
XS GIS Cut Line= 4
      1477759.21       740011.91      1478183.84       739035.25
      1478221.59       738922.01      1478028.13       738355.79
#Sta/Elev= 30
  3932.2  795.93  3986.4  793.06  4051.7  784.74  4118.2  769.39  4256.9  733.83
  4284.5  730.63  4351.1  729.12  4376.4  730.17  4719.3  728.82  4769.6  730.84
  4901.6  731.91  4947.6  735.03  4965.4  735.23  4967.1  733.46  4977.6  723.55
  4980.7  722.47  5021.2  722.08  5045.4  734.12  5055.5  735.96  5071.1  735.09
  5096.5  736.94  5188.5  742.95  5217.0  746.36  5246.0  746.99  5267.6  747.35
  5466.8  763.80  5492.8  767.08  5540.0  767.56  5590.3  774.49  5714.9  780.90
#Mann=8,-1,0
  3932.2    0.08       0  4118.2    0.13       0  4256.9    0.08       0
  4947.6    0.14       0  4967.1   0.042       0  5045.4    0.14       0
  5096.5    0.08       0  5246.0    0.15       0
Bank Sta=4967.1,5045.4
XS Rating Curve= 0
Exp/Cntr=0.3,0.1

Type RM Length L Ch R = 1,92322,339,278,281
BEGIN DESCRIPTION:
Fourth Creek 128.0
END DESCRIPTION:
XS GIS Cut Line= 4
      1478433.92       740262.02      1478924.62       739483.50
      1478952.93       739124.90      1478943.50       738176.52
#Sta/Elev= 30
  3718.3  807.49  3821.7  795.62  3870.5  785.86  3895.6  778.30  3983.6  768.86
  4134.5  740.96  4162.9  733.94  4182.1  733.19  4322.2  730.79  4455.0  732.39
  4874.6  730.57  4932.3  733.19  4946.8  731.98  4956.2  731.78  4974.2  720.79
  5028.3  720.40  5049.0  731.86  5070.6  734.30  5149.2  730.75  5164.2  737.59
  5176.5  739.72  5273.0  742.28  5371.7  748.40  5408.5  750.61  5478.5  753.33
  5576.6  754.56  5775.6  757.77  5799.7  762.48  5846.0  773.11  5946.7  783.14
#Mann=13,-1,0
  3718.3    0.13       0  4182.1    0.08       0  4874.6    0.13       0
  4946.8    0.14       0  4956.2   0.042       0  5049.0    0.14       0
  5176.5     0.1       0  5273.0    0.15       0  5371.7     0.1       0
  5408.5    0.15       0  5478.5    0.14       0  5576.6    0.08       0
  5799.7    0.14       0
#XS Ineff=2,0
    0.00 4294.90  795.67               0
Permanent Ineff=
       F       F
Bank Sta=4956.2,5049
XS Rating Curve= 0
Exp/Cntr=0.3,0.1

Type RM Length L Ch R = 1,92044,606,577,556
BEGIN DESCRIPTION:
Fourth Creek 127.0
END DESCRIPTION:
XS GIS Cut Line= 4
      1479548.18       739987.55      1479241.96       739305.35
      1479229.88       739139.27      1479257.06       738547.08
#Sta/Elev= 30
  4084.0  760.99  4207.8  755.67  4308.3  745.88  4353.9  744.88  4377.6  741.45
  4507.5  734.63  4693.6  733.00  4713.0  732.77  4734.0  729.08  4739.4  725.75
  4745.4  724.60  4759.2  729.16  4778.6  730.55  4882.3  729.79  4926.7  731.26
  4952.0  734.25  4967.1  731.47  4977.6  721.56  4980.7  720.48  5021.2  720.09
  5049.2  731.79  5076.1  730.26  5127.0  731.24  5143.5  734.86  5162.9  743.02
  5390.1  741.42  5434.0  744.33  5469.7  763.43  5534.8  793.72  5591.1  794.15
#Mann=9,-1,0
  4084.0    0.14       0  4507.5    0.08       0  4693.6    0.13       0
  4734.0    0.05       0  4759.2    0.08       0  4882.3    0.13       0
  4952.0    0.14       0  4967.1   0.042       0  5049.2    0.14       0
Bank Sta=4967.1,5049.2
XS Rating Curve= 0
Exp/Cntr=0.3,0.1

Type RM Length L Ch R = 1,91467,561,547,543
BEGIN DESCRIPTION:
Fourth Creek 126.0
END DESCRIPTION:
XS GIS Cut Line= 5
      1480295.82       739712.69      1479918.39       739422.82
      1479797.60       739120.85      1479770.42       739033.27
      1479794.57       738689.05
#Sta/Elev= 30
  4199.9  758.27  4399.7  751.63  4447.7  743.21  4463.5  739.16  4488.3  738.70
  4522.4  730.72  4549.4  729.26  4591.1  729.42  4721.1  727.57  4758.7  728.37
  4767.6  727.06  4791.2  728.30  4922.5  729.26  4947.1  731.57  4959.9  733.13
  4966.1  729.05  4971.8  725.08  4978.6  722.93  4980.3  720.94  4999.1  719.70
  5019.7  721.03  5024.1  723.69  5044.2  728.18  5062.2  732.50  5153.7  743.76
  5211.3  746.65  5318.9  755.43  5334.8  755.56  5368.7  760.17  5437.8  763.00
#Mann=5,-1,0
  4199.9    0.14       0  4591.1    0.08       0  4947.1    0.14       0
  4966.1   0.042       0  5044.2    0.14       0
Bank Sta=4966.1,5044.2
XS Rating Curve= 0
Exp/Cntr=0.3,0.1

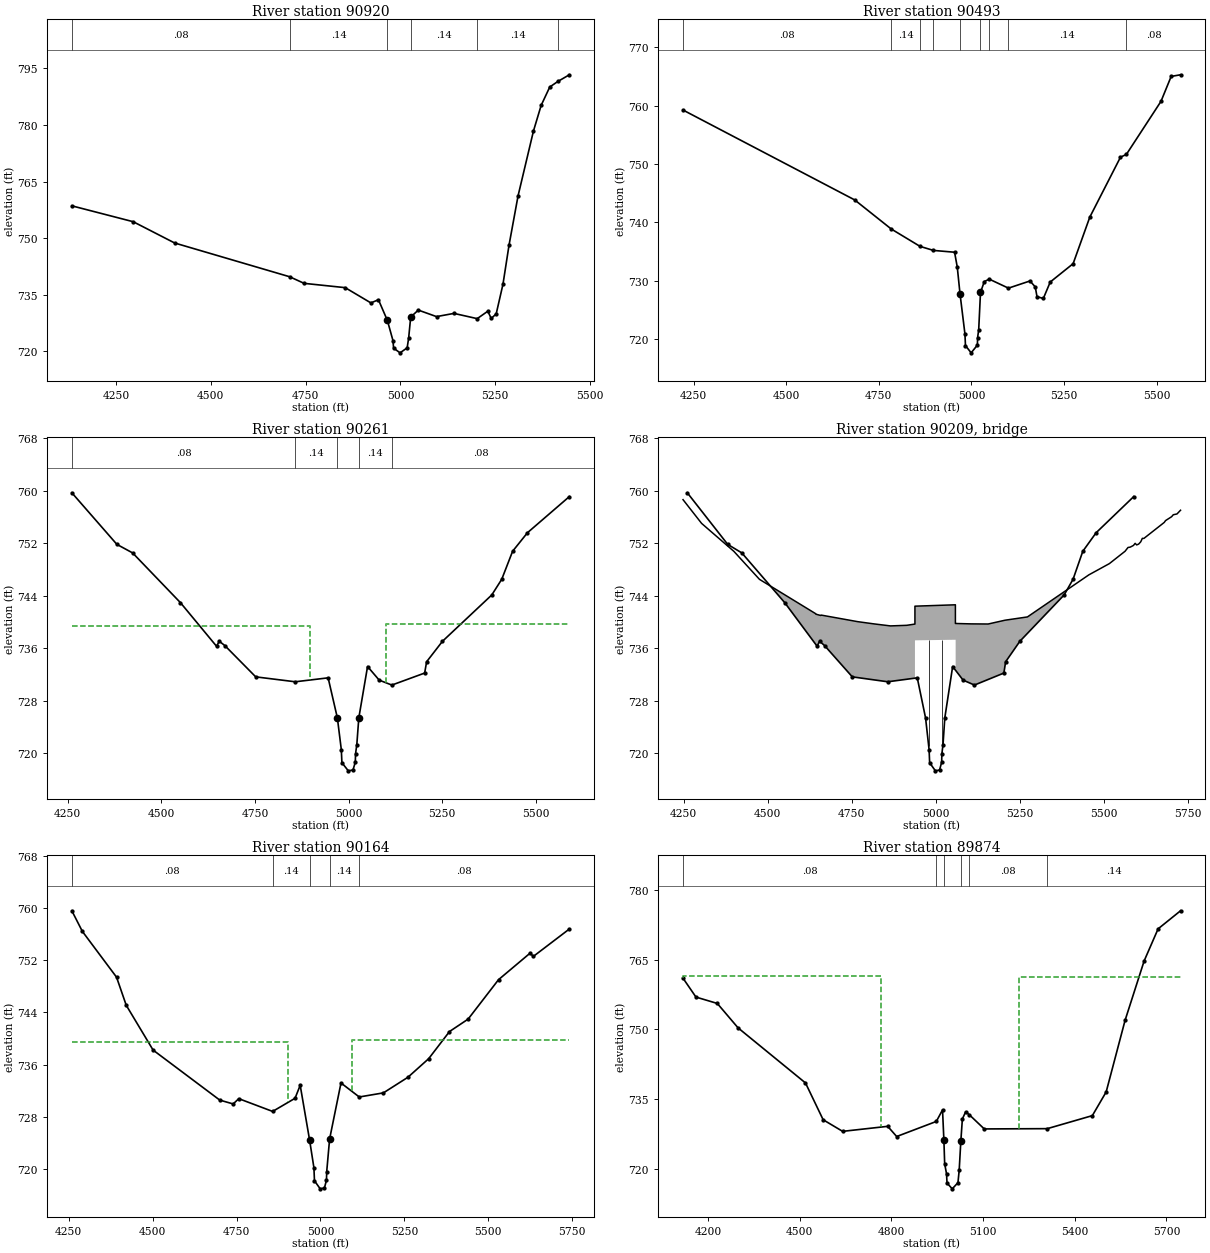
Type RM Length L Ch R = 1,90920,339,427,537
BEGIN DESCRIPTION:
Fourth Creek 125.0
END DESCRIPTION:
XS GIS Cut Line= 5
      1480350.22       739709.68      1480498.18       739295.99
      1480301.89       738912.48      1480241.50       738782.63
      1480069.36       738538.01
#Sta/Elev= 30
  4133.3  758.56  4295.1  754.35  4404.6  748.70  4707.9  739.75  4746.0  738.00
  4854.4  736.86  4922.3  732.81  4942.1  733.66  4965.7  728.16  4980.5  722.80
  4982.1  720.81  4999.2  719.57  5017.9  720.90  5021.9  723.56  5027.2  729.05
  5047.2  730.91  5095.3  729.18  5141.4  730.03  5202.7  728.64  5230.6  730.61
  5239.7  728.69  5252.8  729.91  5270.7  737.79  5286.7  748.17  5310.5  761.23
  5351.1  778.41  5371.4  785.21  5394.1  790.08  5415.8  791.57  5445.8  793.32
#Mann=6,-1,0
  4133.3    0.08       0  4707.9    0.14       0  4965.7   0.042       0
  5027.2    0.14       0  5202.7    0.14       0  5415.8    0.08       0
Bank Sta=4965.7,5027.2
XS Rating Curve= 0
Exp/Cntr=0.3,0.1

Type RM Length L Ch R = 1,90493,234,232,250
BEGIN DESCRIPTION:
Fourth Creek 124.0
END DESCRIPTION:
XS GIS Cut Line= 4
      1480365.30       739730.86      1480532.00       739250.69
      1480698.48       739037.34      1481030.28       738580.28
#Sta/Elev= 30
  4221.1  759.23  4684.7  743.84  4783.2  738.87  4861.3  735.88  4897.5  735.19
  4954.5  734.88  4961.8  732.33  4969.1  727.81  4982.5  720.88  4983.9  718.89
  4999.3  717.65  5016.1  718.98  5016.7  720.25  5019.7  721.64  5024.5  727.99
  5034.8  729.86  5048.2  730.27  5100.0  728.73  5158.2  729.96  5172.5  728.93
  5177.1  727.27  5194.2  726.96  5212.9  729.78  5274.7  732.92  5319.7  740.89
  5402.6  751.16  5418.5  751.63  5512.0  760.72  5539.5  764.99  5564.8  765.27
#Mann=9,-1,0
  4221.1    0.08       0  4783.2    0.14       0  4861.3    0.08       0
  4897.5    0.14       0  4969.1   0.042       0  5024.5    0.14       0
  5048.2    0.08       0  5100.0    0.14       0  5418.5    0.08       0
Bank Sta=4969.1,5024.5
XS Rating Curve= 0
Exp/Cntr=0.5,0.3

Type RM Length L Ch R = 1,90261,139,97,122
BEGIN DESCRIPTION:
Elmwood Rd (FC) us
END DESCRIPTION:
XS GIS Cut Line= 4
      1480423.31       739776.10      1480867.19       739196.34
      1481126.89       738903.42      1481154.07       738698.05
#Sta/Elev= 30
  4260.8  759.71  4381.1  751.84  4423.1  750.54  4550.9  742.95  4647.2  736.31
  4654.6  737.07  4669.4  736.41  4751.9  731.64  4857.5  730.89  4945.3  731.49
  4970.0  725.37  4980.5  720.54  4982.1  718.55  4999.2  717.31  5011.7  717.44
  5017.9  718.64  5018.5  719.91  5021.9  721.30  5027.2  725.37  5050.6  733.22
  5081.7  731.14  5115.5  730.39  5203.1  732.22  5208.3  733.94  5250.6  737.06
  5382.4  744.13  5409.0  746.52  5438.0  750.79  5477.7  753.62  5589.6  759.13
#Mann=5,-1,0
  4260.8    0.08       0  4857.5    0.14       0  4970.0   0.042       0
  5027.2    0.14       0  5115.5    0.08       0
#XS Ineff=2,0
    0.00 4896.90  739.47 5101.00    0.00  739.73
Permanent Ineff=
       F       F
Bank Sta=4970,5027.2
XS Rating Curve= 0
Exp/Cntr=0.5,0.3

Type RM Length L Ch R =3,90209,,,
BEGIN DESCRIPTION:
Elmwood Rd (FC) TOR
Structure ID: I_FC_01
Detailed Survey Structure
END DESCRIPTION:
Bridge Culvert--1,0,-1,-1,0
Deck Dist Width WeirC Skew NumUp NumDn MinLoCord MaxHiCord MaxSubmerge Is_Ogee
41.5,21,3,,43,43,,,,0,1,1,,,
  4248.1  4303.4  4399.4  4475.6  4643.0  4643.5  4657.7  4659.4  4767.8  4816.2
  4865.5  4913.8  4938.3  4938.3  4938.4  4938.4  5058.8  5058.8  5059.5  5059.5
  5105.7  5156.2  5206.6  5273.2  5454.5  5454.8  5517.1  5563.7  5572.6  5579.0
  5588.8  5593.7  5598.3  5604.1  5610.5  5615.2  5619.8  5680.4  5684.3  5702.3
  5707.3  5718.3  5728.9
  758.66  755.04  750.78  746.51  741.27  741.20  741.00  741.06  740.06  739.72
  739.41  739.50  739.69  742.42  742.42  742.42  742.63  739.78  739.78  739.78
  739.72  739.70  740.28  740.78  747.14  747.16  748.91  750.79  751.37  751.42
  751.68  752.00  751.76  751.88  752.24  752.76  752.75  755.19  755.47  756.06
  756.36  756.48  757.05
  697.31  697.31  697.31  697.31  697.31  697.31  697.31  697.31  697.31  697.31
  697.31  697.31  697.31  697.31  697.31  737.21  737.30  737.30  737.30  697.31
  697.31  697.31  697.31  697.31  697.31  697.31  697.31  697.31  697.31  697.31
  697.31  697.31  697.31  697.31  697.31  697.31  697.31  697.31  697.31  697.31
  697.31  697.31  697.31
  4248.1  4303.4  4399.4  4475.6  4643.0  4643.5  4657.7  4659.4  4767.8  4816.2
  4865.5  4913.8  4938.3  4938.3  4938.4  4938.4  5058.8  5058.8  5059.5  5059.5
  5105.7  5156.2  5206.6  5273.2  5454.5  5454.8  5517.1  5563.7  5572.6  5579.0
  5588.8  5593.7  5598.3  5604.1  5610.5  5615.2  5619.8  5680.4  5684.3  5702.3
  5707.3  5718.3  5728.9
  758.66  755.04  750.78  746.51  741.27  741.20  741.00  741.06  740.06  739.72
  739.41  739.50  739.69  742.42  742.42  742.42  742.63  739.78  739.78  739.78
  739.72  739.70  740.28  740.78  747.14  747.16  748.91  750.79  751.37  751.42
  751.68  752.00  751.76  751.88  752.24  752.76  752.75  755.19  755.47  756.06
  756.36  756.48  757.05
  697.31  697.31  697.31  697.31  697.31  697.31  697.31  697.31  697.31  697.31
  697.31  697.31  697.31  697.31  697.31  737.21  737.30  737.30  737.30  697.31
  697.31  697.31  697.31  697.31  697.31  697.31  697.31  697.31  697.31  697.31
  697.31  697.31  697.31  697.31  697.31  697.31  697.31  697.31  697.31  697.31
  697.31  697.31  697.31
Pier Skew, UpSta & Num, DnSta & Num=,4979.4,2,4979.4,2,0,0,0,0,0
     0.8     0.8
  720.70  737.24
     0.8     0.8
  720.30  737.24
Pier Skew, UpSta & Num, DnSta & Num=,5018.5,2,5018.5,2,0,0,0,0,0
     0.8     0.8
  719.91  737.27
     0.8     0.8
  719.51  737.27
BR Coef=1,0,0,1.25,0,,,0.8,0,2,1,
WSPro=,,,, 1 ,,,, 0 ,,,, 0 ,,,,-1 ,-1 ,-1 , 0 , 0 , 0 , 0 , 0
BC Design=,,0,,0,,,,,,

Type RM Length L Ch R = 1,90164,290,290,311
BEGIN DESCRIPTION:
Elmwood Rd (FC) ds
END DESCRIPTION:
XS GIS Cut Line= 4
      1480507.86       739845.56      1480812.84       739404.70
      1481238.62       738921.54      1481277.88       738622.57
#Sta/Elev= 30
  4259.6  759.62  4290.8  756.46  4392.7  749.42  4421.6  745.10  4501.6  738.22
  4700.1  730.54  4740.0  729.95  4756.7  730.76  4857.5  728.80  4924.3  730.82
  4939.6  732.82  4967.6  724.40  4980.5  720.14  4982.1  718.15  4999.2  716.91
  5011.7  717.04  5017.9  718.24  5018.5  719.51  5027.2  724.56  5061.1  733.17
  5115.5  731.02  5187.4  731.65  5260.5  734.05  5322.2  736.90  5384.2  741.07
  5439.7  742.98  5530.3  749.04  5624.0  753.10  5634.2  752.62  5741.2  756.82
#Mann=5,-1,0
  4259.6    0.08       0  4857.5    0.14       0  4967.6   0.045       0
  5027.2    0.14       0  5115.5    0.08       0
#XS Ineff=2,0
    0.00 4903.90  739.48 5094.00    0.00  739.74
Permanent Ineff=
       F       F
Bank Sta=4967.6,5027.2
XS Rating Curve= 0
Exp/Cntr=0.5,0.3

Type RM Length L Ch R = 1,89874,446,419,416
BEGIN DESCRIPTION:
Fourth Creek 123.0
END DESCRIPTION:
XS GIS Cut Line= 4
      1480830.12       740197.76      1480890.73       739714.25
      1481142.75       739466.96      1481678.66       738890.45
#Sta/Elev= 30
  4118.5  760.98  4160.8  756.93  4230.6  755.56  4298.6  750.31  4519.1  738.48
  4576.9  730.57  4640.6  728.08  4788.1  729.16  4817.4  726.97  4947.1  730.21
  4967.4  732.69  4971.9  726.13  4974.4  721.11  4980.5  718.96  4982.1  716.97
  4999.2  715.73  5017.9  717.06  5021.9  719.72  5027.2  725.91  5032.3  730.74
  5043.1  732.29  5055.3  731.63  5103.9  728.60  5310.0  728.66  5457.5  731.46
  5502.7  736.55  5564.6  751.94  5627.0  764.71  5672.6  771.59  5746.0  775.47
#Mann=6,-1,0
  4118.5    0.08       0  4947.1    0.14       0  4971.9   0.045       0
  5027.2    0.14       0  5055.3    0.08       0  5310.0    0.14       0
#XS Ineff=2,0
    0.00 4767.00  761.43 5218.70    0.00  761.21
Permanent Ineff=
       F       F
Bank Sta=4971.9,5027.2
XS Rating Curve= 0
Exp/Cntr=0.3,0.1

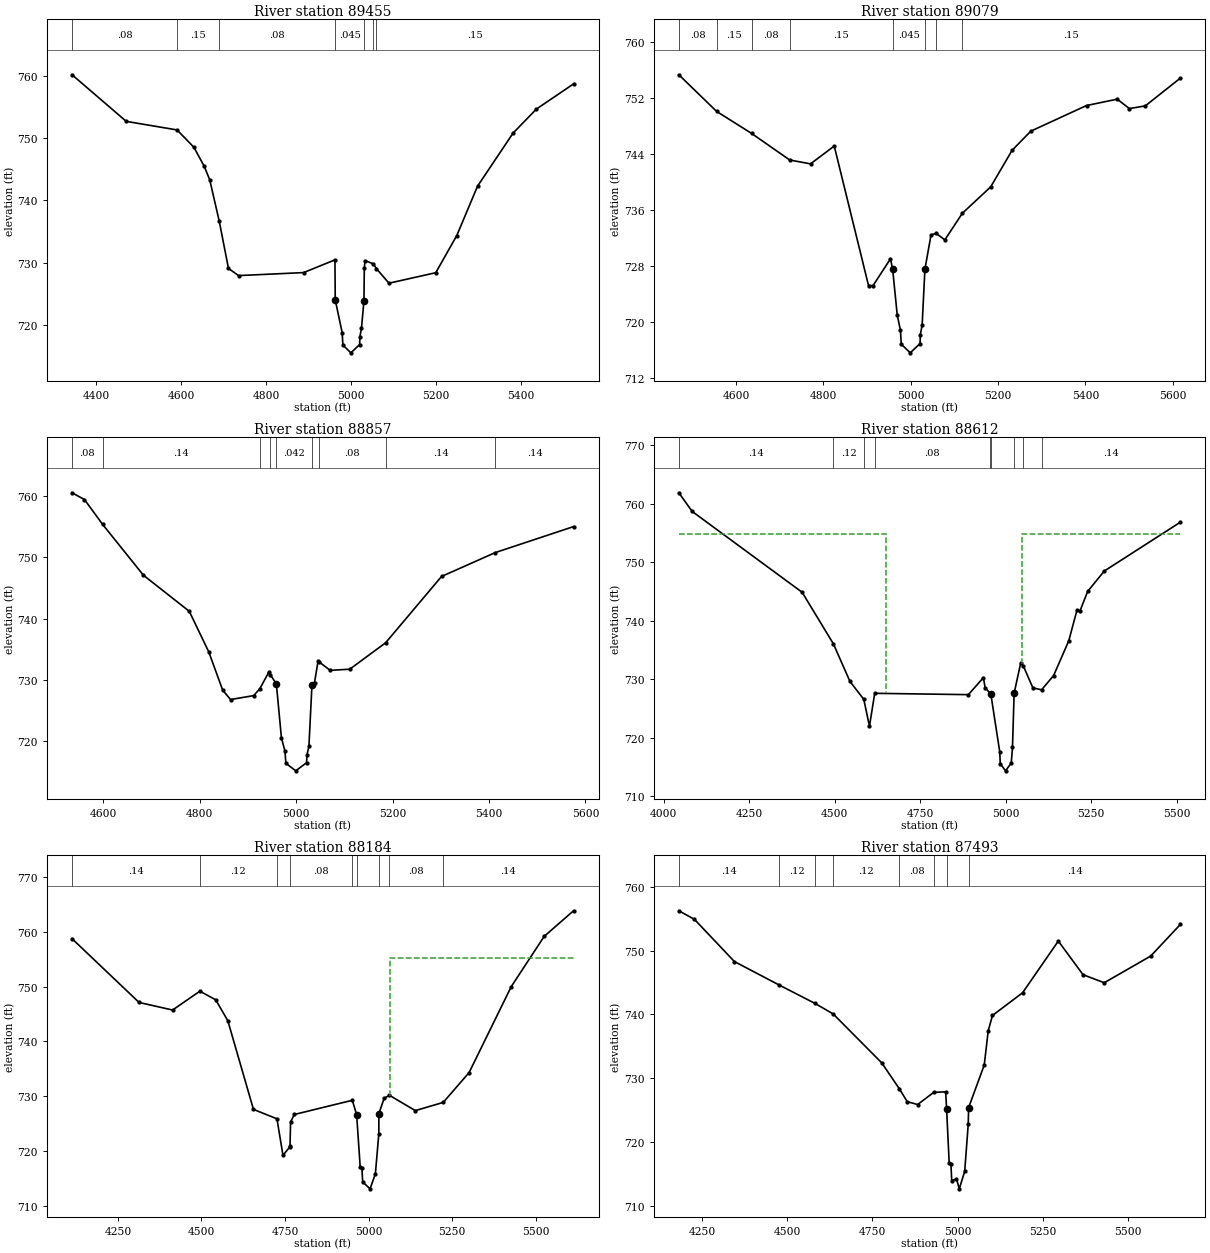
Type RM Length L Ch R = 1,89455,377,376,375
BEGIN DESCRIPTION:
Fourth Creek 122.0
END DESCRIPTION:
XS GIS Cut Line= 4
      1481276.73       740303.33      1481288.91       740043.49
      1481483.80       739718.68      1481784.27       739267.97
#Sta/Elev= 30
  4342.7  760.14  4470.4  752.67  4590.0  751.30  4629.7  748.51  4653.9  745.47
  4666.9  743.29  4689.2  736.68  4710.9  729.11  4734.6  727.96  4887.8  728.44
  4961.6  730.48  4962.3  724.07  4978.6  718.81  4980.3  716.82  4999.1  715.58
  5019.7  716.91  5020.4  718.18  5024.1  719.57  5029.9  723.90  5030.7  729.13
  5032.4  730.37  5052.2  729.83  5059.4  729.06  5088.8  726.74  5198.9  728.42
  5248.4  734.37  5297.3  742.29  5380.9  750.79  5436.0  754.65  5523.3  758.68
#Mann=7,-1,0
  4342.7    0.08       0  4590.0    0.15       0  4689.2    0.08       0
  4962.3   0.045       0  5029.9    0.08       0  5052.2    0.08       0
  5059.4    0.15       0
Bank Sta=4962.3,5029.9
XS Rating Curve= 0
Exp/Cntr=0.3,0.1

Type RM Length L Ch R = 1,89079,270,222,173
BEGIN DESCRIPTION:
Fourth Creek 121.5
END DESCRIPTION:
XS GIS Cut Line= 3
      1481557.35       740423.91      1481820.89       739862.08
      1481846.95       739334.99
#Sta/Elev= 30
  4469.2  755.33  4555.8  750.08  4635.9  746.93  4723.1  743.13  4770.8  742.58
  4825.0  745.13  4903.5  725.16  4913.8  725.15  4953.8  728.99  4958.8  727.47
  4969.3  720.91  4976.6  718.76  4978.5  716.77  4999.0  715.53  5021.5  716.86
  5022.2  718.13  5026.3  719.52  5032.6  727.47  5046.6  732.41  5058.3  732.63
  5078.3  731.70  5118.4  735.51  5183.3  739.29  5232.3  744.52  5275.1  747.26
  5402.7  750.93  5473.0  751.84  5500.8  750.49  5537.3  750.88  5617.5  754.85
#Mann=8,-1,0
  4469.2    0.08       0  4555.8    0.15       0  4635.9    0.08       0
  4723.1    0.15       0  4958.8   0.045       0  5032.6    0.15       0
  5058.3    0.08       0  5118.4    0.15       0
Bank Sta=4958.8,5032.6
XS Rating Curve= 0
Exp/Cntr=0.3,0.1

Type RM Length L Ch R = 1,88857,318,245,231
BEGIN DESCRIPTION:
Fourth Creek 121.0
END DESCRIPTION:
XS GIS Cut Line= 4
      1482075.72       740334.10      1482046.76       739989.49
      1481919.35       739804.16      1481864.33       739337.92
#Sta/Elev= 30
  4535.0  760.57  4560.7  759.47  4598.5  755.39  4683.1  747.09  4778.1  741.20
  4818.6  734.56  4847.4  728.32  4863.7  726.77  4911.9  727.42  4924.7  728.57
  4942.9  731.22  4946.6  730.81  4958.8  729.31  4969.3  720.50  4976.6  718.35
  4978.5  716.36  4999.0  715.12  5021.5  716.45  5022.2  717.72  5026.3  719.11
  5032.6  729.14  5037.9  729.52  5045.4  733.12  5047.0  732.95  5070.3  731.55
  5111.0  731.73  5185.4  736.05  5301.4  746.89  5413.0  750.80  5575.2  755.04
#Mann=9,-1,0
  4535.0    0.08       0  4598.5    0.14       0  4924.7    0.08       0
  4946.6    0.14       0  4958.8   0.042       0  5032.6    0.14       0
  5047.0    0.08       0  5185.4    0.14       0  5413.0    0.14       0
Bank Sta=4958.8,5032.6
XS Rating Curve= 0
Exp/Cntr=0.3,0.1

Type RM Length L Ch R = 1,88612,397,428,416
BEGIN DESCRIPTION:
Fourth Creek 120.0
END DESCRIPTION:
XS GIS Cut Line= 4
      1483001.13       740120.33      1482126.96       739702.04
      1482004.76       739608.04      1481859.05       739297.82
#Sta/Elev= 30
  4044.4  761.84  4083.2  758.66  4404.7  744.84  4496.1  736.03  4544.6  729.60
  4585.0  726.54  4601.6  721.94  4617.0  727.57  4890.8  727.34  4934.5  730.24
  4939.9  728.54  4953.2  727.63  4956.5  727.41  4982.5  717.55  4983.9  715.56
  4999.3  714.32  5016.1  715.65  5019.7  718.31  5024.5  727.58  5044.0  732.82
  5051.6  732.22  5079.4  728.49  5104.8  728.17  5139.9  730.60  5184.1  736.52
  5208.3  741.79  5216.8  741.61  5239.4  744.97  5287.9  748.46  5510.4  756.81
#Mann=9,-1,0
  4044.4    0.14       0  4496.1    0.12       0  4585.0    0.05       0
  4617.0    0.08       0  4953.2    0.14       0  4956.5   0.042       0
  5024.5    0.14       0  5051.6    0.08       0  5104.8    0.14       0
#XS Ineff=2,0
    0.00 4651.30  754.81 5047.00    0.00  754.81
Permanent Ineff=
       F       F
Bank Sta=4956.5,5024.5
XS Rating Curve= 0
Exp/Cntr=0.3,0.1

Type RM Length L Ch R = 1,88184,631,691,758
BEGIN DESCRIPTION:
Fourth Creek 119.0
END DESCRIPTION:
XS GIS Cut Line= 5
      1483048.16       739935.62      1482484.17       739437.42
      1482380.76       739366.92      1482026.18       739154.18
      1481821.44       739113.12
#Sta/Elev= 30
  4113.1  758.73  4313.6  747.11  4413.8  745.73  4495.4  749.16  4542.9  747.59
  4579.0  743.78  4655.7  727.62  4726.0  725.90  4744.0  719.24  4764.0  720.76
  4765.0  720.89  4766.8  725.34  4777.9  726.69  4951.4  729.28  4964.3  726.67
  4974.9  717.19  4980.0  717.01  4982.4  714.40  5004.5  713.14  5020.4  715.88
  5030.7  723.22  5030.8  726.85  5046.6  729.64  5062.4  730.19  5139.8  727.40
  5223.3  728.89  5300.8  734.34  5426.7  749.99  5525.5  759.17  5613.1  763.82
#Mann=9,-1,0
  4113.1    0.14       0  4495.4    0.12       0  4726.0    0.05       0
  4764.0    0.08       0  4951.4    0.14       0  4964.3   0.042       0
  5030.8    0.14       0  5062.4    0.08       0  5223.3    0.14       0
#XS Ineff=2,0
       0                 5065.60    0.00  755.28
Permanent Ineff=
       F       F
Bank Sta=4964.3,5030.8
XS Rating Curve= 0
Exp/Cntr=0.3,0.1

Type RM Length L Ch R = 1,87493,609,624,642
BEGIN DESCRIPTION:
Fourth Creek 118.0
END DESCRIPTION:
XS GIS Cut Line= 4
      1483333.92       739670.52      1482917.45       738967.06
      1482798.13       738692.93      1482591.31       738406.21
#Sta/Elev= 30
  4182.5  756.24  4228.2  754.90  4345.3  748.29  4476.0  744.63  4581.4  741.74
  4635.0  740.08  4777.5  732.41  4829.1  728.34  4852.0  726.35  4882.5  725.90
  4929.9  727.82  4964.6  727.88  4967.3  725.27  4974.9  716.75  4980.0  716.57
  4982.4  713.96  4996.3  714.26  5004.5  712.70  5020.4  715.44  5030.7  722.78
  5031.9  725.42  5077.7  732.09  5089.3  737.43  5101.8  739.85  5190.2  743.41
  5294.8  751.50  5367.3  746.23  5429.4  744.97  5565.9  749.16  5652.5  754.10
#Mann=8,-1,0
  4182.5    0.14       0  4476.0    0.12       0  4581.4    0.08       0
  4635.0    0.12       0  4829.1    0.08       0  4929.9    0.14       0
  4967.3   0.042       0  5031.9    0.14       0
Bank Sta=4967.3,5031.9
XS Rating Curve= 0
Exp/Cntr=0.3,0.1

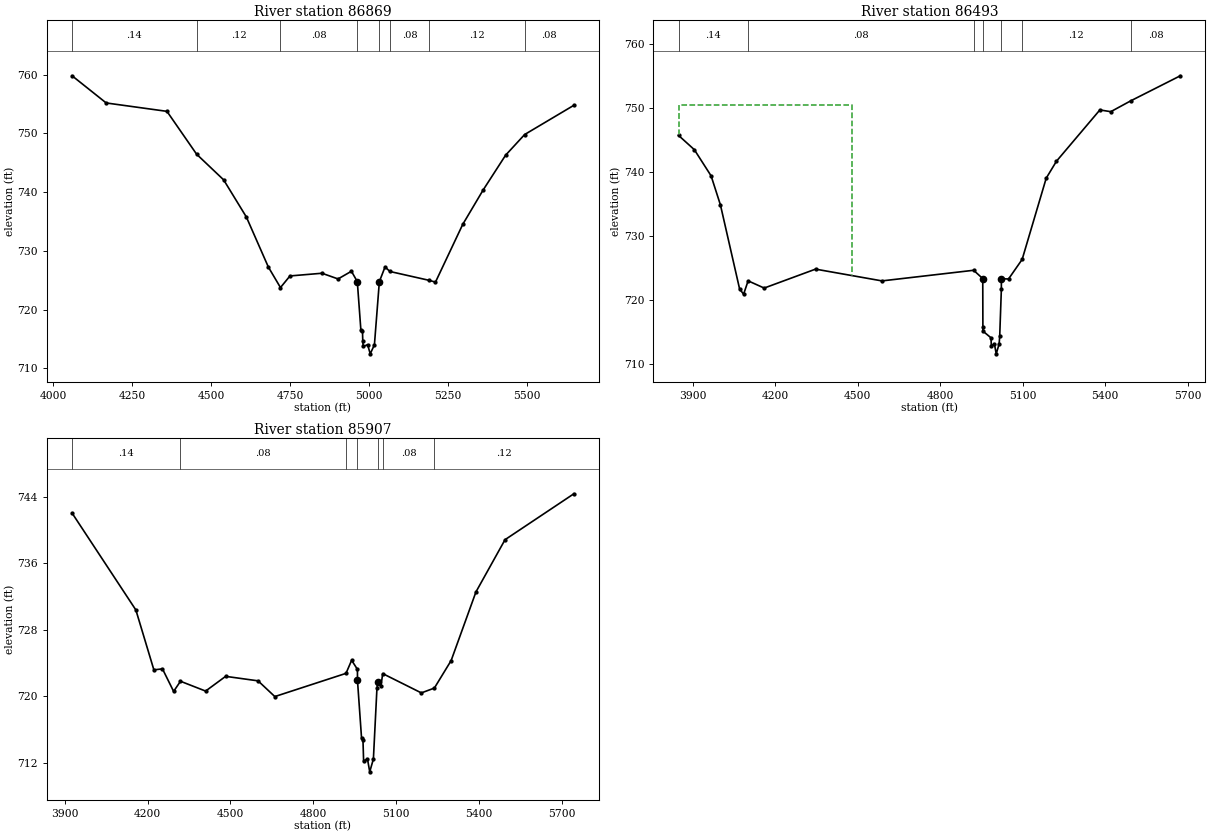
Type RM Length L Ch R = 1,86869,437,376,352
BEGIN DESCRIPTION:
Fourth Creek 117.0 (Survey)
END DESCRIPTION:
XS GIS Cut Line= 5
      1483484.35       739670.52      1483554.85       738909.13
      1483498.45       738739.93      1483369.58       738411.70
      1483338.65       738119.56
#Sta/Elev= 30
  4060.1  759.82  4168.2  755.19  4360.6  753.76  4454.6  746.46  4540.2  742.09
  4612.2  735.76  4681.9  727.23  4720.2  723.74  4750.3  725.72  4851.7  726.18
  4902.6  725.21  4945.0  726.52  4963.6  724.75  4974.9  716.50  4980.0  716.32
  4980.9  714.57  4982.4  713.71  4996.3  714.01  5004.5  712.45  5017.8  713.99
  5033.4  724.75  5051.5  727.26  5066.8  726.48  5190.4  724.98  5211.2  724.67
  5297.5  734.50  5361.9  740.34  5433.3  746.29  5493.6  749.81  5649.5  754.79
#Mann=8,-1,0
  4060.1    0.14       0  4454.6    0.12       0  4720.2    0.08       0
  4963.6   0.042       0  5033.4    0.08       0  5066.8    0.08       0
  5190.4    0.12       0  5493.6    0.08       0
Bank Sta=4963.6,5033.4
XS Rating Curve= 0
Exp/Cntr=0.3,0.1

Type RM Length L Ch R = 1,86493,601,586,589
BEGIN DESCRIPTION:
Fourth Creek 116.0
END DESCRIPTION:
XS GIS Cut Line= 5
      1484216.98       739645.57      1484005.60       738784.59
      1483844.89       738593.94      1483757.54       738513.88
      1483352.76       738110.14
#Sta/Elev= 30
  3847.5  745.77  3905.0  743.54  3966.0  739.45  4000.0  734.90  4069.8  721.76
  4084.3  720.95  4100.7  723.04  4159.2  721.91  4346.1  724.87  4587.8  723.03
  4921.4  724.69  4954.6  723.39  4955.1  715.84  4955.2  715.18  4984.5  714.14
  4985.9  712.89  4997.0  713.19  5003.6  711.63  5014.2  713.17  5016.3  714.37
  5022.3  721.71  5022.4  723.37  5048.4  723.33  5098.0  726.39  5185.6  739.09
  5222.9  741.74  5380.8  749.75  5420.6  749.48  5493.0  751.17  5673.6  755.09
#Mann=7,-1,0
  3847.5    0.14       0  4100.7    0.08       0  4921.4    0.13       0
  4954.6   0.042       0  5022.4    0.13       0  5098.0    0.12       0
  5493.0    0.08       0
#XS Ineff=2,0
    0.00 4480.20  750.46               0
Permanent Ineff=
       F       F
Bank Sta=4954.6,5022.4
XS Rating Curve= 0
Exp/Cntr=0.3,0.1

Type RM Length L Ch R = 1,85907,0,0,0
BEGIN DESCRIPTION:
Fourth Creek 115.0 (Tie-in)
END DESCRIPTION:
XS GIS Cut Line= 5
      1484933.13       739040.43      1484594.59       738550.27
      1484274.33       738200.90      1484085.08       738004.37
      1483680.13       737757.43
#Sta/Elev= 30
  3926.8  742.02  4157.8  730.37  4223.0  723.17  4254.1  723.29  4294.5  720.58
  4319.3  721.80  4410.3  720.62  4482.8  722.39  4600.2  721.85  4660.9  719.96
  4918.6  722.75  4939.0  724.32  4960.0  723.23  4960.2  721.90  4974.9  714.96
  4980.0  714.78  4982.4  712.17  4996.3  712.47  5004.5  710.91  5017.8  712.45
  5030.7  720.99  5034.4  721.66  5045.1  721.22  5051.5  722.72  5191.4  720.40
  5238.5  720.98  5299.3  724.29  5389.1  732.54  5494.4  738.82  5743.6  744.34
#Mann=7,-1,0
  3926.8    0.14       0  4319.3    0.08       0  4918.6    0.13       0
  4960.2   0.042       0  5034.4    0.13       0  5051.5    0.08       0
  5238.5    0.12       0
Bank Sta=4960.2,5034.4
XS Rating Curve= 0
Exp/Cntr=0.3,0.1

Chan Stop Cuts=-1